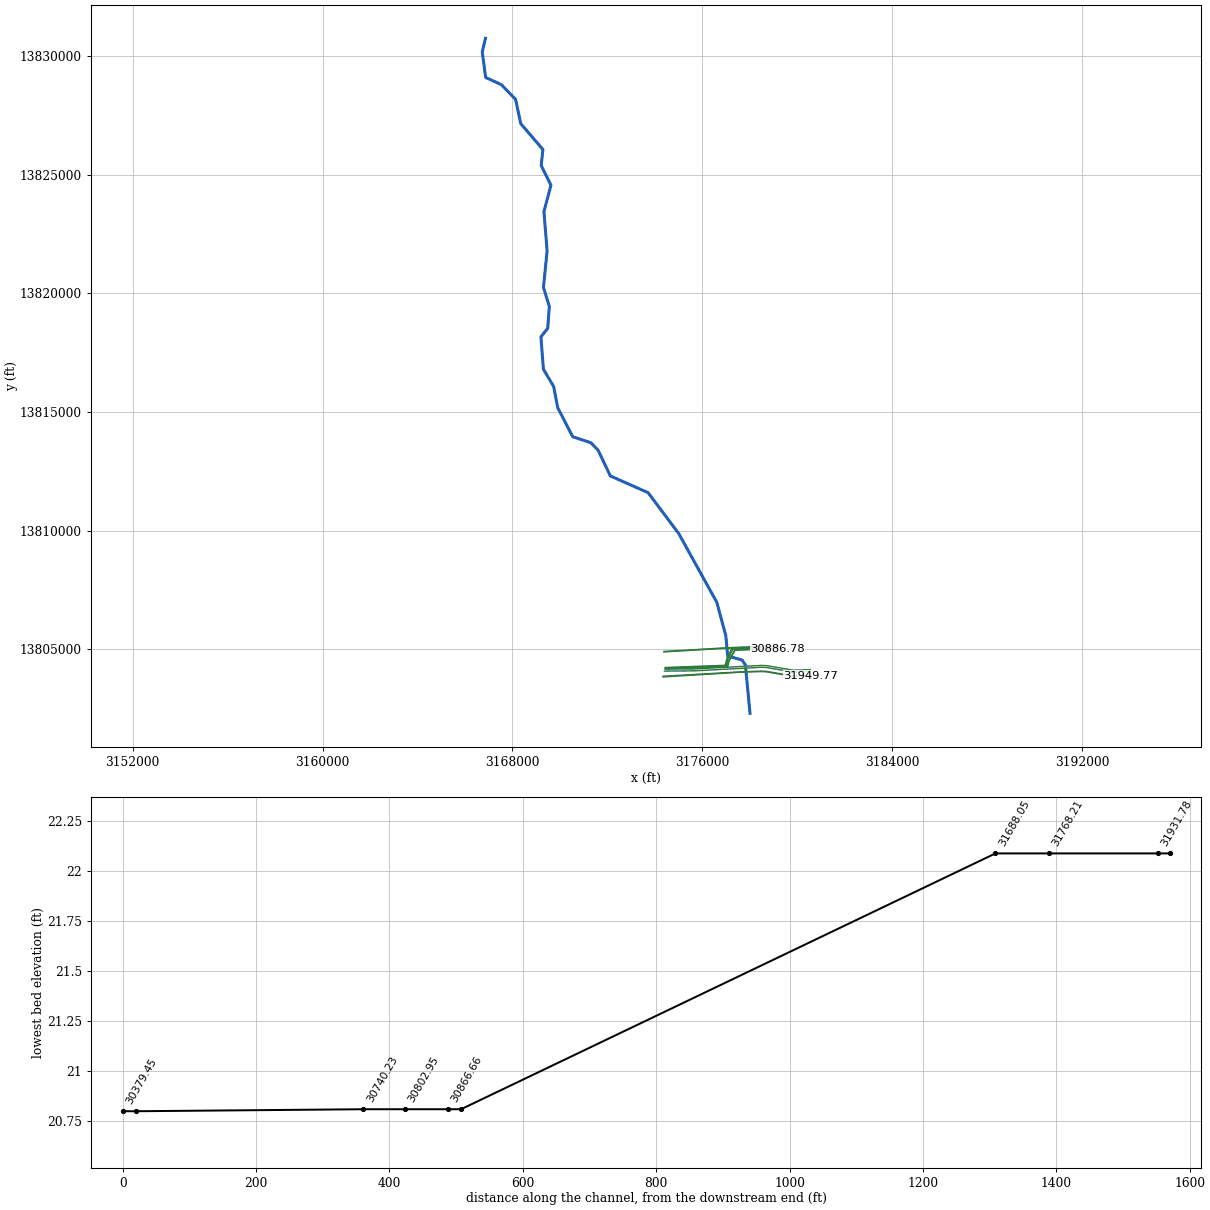
--- I100-00-00.prj (project) ---

Proj Title=I100-00-00
Current Plan=p01
Default Exp/Contr=.3,.1
English Units
Geom File=g03
Geom File=g01
Flow File=f01
Flow File=f04
Plan File=p04
Plan File=p01
Y Axis Title=Elevation
X Axis Title(PF)=Main Channel Distance
X Axis Title(XS)=Station
BEGIN DESCRIPTION:
Vince Bayou
Vince Bayou
HCFCD Unit I100-00-00
Flood Hazard Model
10, 2, 1, 0.2% Event
Filename: I100-00-00.prj
Prepared by: Matthew Fischer Date: 6/1/04
Reviewd by:		Date:
Status Final Subittal
END DESCRIPTION:
DSS Export Rating Curves= 0
DSS Export Rating Curve Sorted= 0
DSS Export Volume Flow Curves= 0
DXF OffsetX= 0
DXF OffsetY= 0
DXF ScaleX= 1
DXF ScaleY= 10

--- I100-00-00.p01 (plan) ---

Plan Title=Floodway
Version=Version 3.0.1  Mar 2001
Short Identifier=Floodway0607
Geom File=g01
Flow File=f01
Subcritical Flow
K Sum by GR= 0
Std Step Tol= 0.01
Critical Tol= 0.01
Num of Std Step Trials= 20
Max Error Tol= 0.3
Flow Tol Ratio= 0.001
Split Flow NTrial= 30
Split Flow Tol= 0.02
Split Flow Ratio= 0.02
Log Output Level= 0
Friction Slope Method= 0
Unsteady Friction Slope Method= 2
Secant Critical Depth
Global Vel Dist= 0 , 0 , 0
Global Log Level= 0
CheckData=True
Encroach Param=-1 ,0,0, 2
Encroach River=I100-00-00
Encroach Reach=I100-00-00
Encroach Node=31949.77
       1 4912.79 5087.21
Encroach Node=31931.78
       1 4912.79 5087.21
Encroach Node=31850
       1 4912.79 5087.21
Encroach Node=31768.21
       1 4912.79 5087.21
Encroach Node=31688.05
       1 4912.79 5087.21
Encroach Node=30886.78
       1 4972.64 5073.28
Encroach Node=30866.66
       1 4972.64 5073.28
Encroach Node=30834
       1 4972.64 5073.28
Encroach Node=30802.95
       1 4972.64 5073.28
Encroach Node=30740.23
       1 4972.64 5073.28
Encroach Node=30399.47
       1  4928.8  5071.2
Encroach Node=30379.45
       1 4915.24  5071.2
Encroach Node=30349
       1 4915.24  5071.2
Encroach Node=30319.38
       1  4928.8  5071.2
Encroach Node=30239.3
       1  4926.5  5071.2
Encroach Node=29519.8
       1 4944.37 5055.63
Encroach Node=29497.92
       1 4944.37 5055.63
Encroach Node=29465
       1 4944.37 5055.63
Encroach Node=29432.26
       1 4944.37 5055.63
Encroach Node=29340.04
       1 4944.37 5055.63
Encroach Node=28656.45
       1 4934.47 5065.53
Encroach Node=28636.38
       1 4934.47 5065.53
Encroach Node=28585
       1 4934.47 5065.53
Encroach Node=28533
       1 4934.47 5065.53
Encroach Node=28451.33
       1 4934.47 5065.53
Encroach Node=27097.22
       1 4947.82 5052.18
Encroach Node=26751.03
       1 4946.08 5053.92
Encroach Node=26262.9
       1 4932.01 5067.99
Encroach Node=26218.88
       1 4932.01 5067.99
Encroach Node=26136
       1    4800    5200
Encroach Node=26054.71
       1    4885    5100
Encroach Node=25864.96
       1    4906    5086
Encroach Node=25392.72
       1 4946.61 5078.71
Encroach Node=24331.07
       1  4936.7    5051
Encroach Node=23523.97
       1 4942.28 5057.72
Encroach Node=22206.24
       1 4939.12 5060.88
Encroach Node=21479.79
       1 4926.29 5073.71
Encroach Node=21459.79
       1 4926.29 5073.71
Encroach Node=21409
       1    4900    5100
Encroach Node=21359.64
       1    4900    5100
Encroach Node=21279.38
       1    4928 5073.71
Encroach Node=20373.4
       1    4900 5045.26
Encroach Node=20352.16
       1    4900 5045.26
Encroach Node=20304
       1 4954.74 5045.26
Encroach Node=20256.61
       1 4932.28 5045.26
Encroach Node=20171.67
       1 4929.92 5045.26
Encroach Node=19792.1
       1 4917.32 5045.26
Encroach Node=18416.74
       1 4922.24 5051.95
Encroach Node=18395.75
       1 4922.24 5051.95
Encroach Node=18364
       1 4922.24 5051.95
Encroach Node=18333.97
       1 4922.24 5051.95
Encroach Node=18251.64
       1 4958.05 5051.95
Encroach Node=17132.05
       1 4944.54 5049.05
Encroach Node=17112.04
       1 4949.19 5049.05
Encroach Node=17077
       1    4800    5200
Encroach Node=17041.88
       1 4938.22 5049.05
Encroach Node=16941.22
       1 4905.42 5049.05
Encroach Node=16097.19
       1 4919.66 5050.25
Encroach Node=15226.85
       1 4922.68 5153.24
Encroach Node=14416.41
       1 4955.79 5067.39
Encroach Node=14162.07
       1 4920.42 5042.08
Encroach Node=14142.5
       1    4908 5042.08
Encroach Node=14099
       1    4908 5042.08
Encroach Node=14055
       1    4908 5042.08
Encroach Node=13970.87
       1    4916    5050
Encroach Node=13138.31
       1 4935.72  5056.3
Encroach Node=12631.77
       1 4943.04 5045.69
Encroach Node=12324
       1 4928.76 5048.04
Encroach Node=12303.98
       1 4927.96 5049.56
Encroach Node=12295
       1 4927.96 5049.56
Encroach Node=12287.96
       1 4915.15 5088.35
Encroach Node=12234.91
       1 4873.96 5108.62
Encroach Node=12101.17
       1 4905.41 5094.59
Encroach Node=11357.13
       1    4800    5086
Encroach Node=11336.82
       1    4700 5096.12
Encroach Node=11280
       1    4690    5856
Encroach Node=11225.22
       1    4716    5159
Encroach Node=11144.42
       1 4765.58 5219.58
Encroach Node=9952.692
       1    4800    5200
Encroach Node=8674.735
       1 4940.76 5059.24
Encroach Node=8654.613
       1    4938    5065
Encroach Node=8614
       1    4850    5150
Encroach Node=8574.103
       1    4928    5056
Encroach Node=8493.352
       1    4912    5056
Encroach Node=7862.905
       1    4926    5060
Encroach Node=7431.416
       1    4850  5041.6
Encroach Node=7411.38
       1    4815  5041.6
Encroach Node=7396
       1    4800    5200
Encroach Node=7381
       1    4800 5056.79
Encroach Node=7299.108
       1    4880    5070
Encroach Node=6848.763
       1 4974.88 5110.21
Encroach Node=6838.733
       1 4974.88 5110.21
Encroach Node=6823
       1    4900 5110.21
Encroach Node=6808.516
       1 4974.88    5087
Encroach Node=6698.381
       1    4897    5120
Encroach Node=6677.703
       1    4914 5127.14
Encroach Node=6489
       1  4876.3 5127.14
Encroach Node=6300.465
       1  4876.3  5123.7
Encroach Node=6217.734
       1 4899.46 5060.19
Encroach Node=5850.572
       1 4957.76 5042.24
Encroach Node=5830.502
       1 4957.76 5042.24
Encroach Node=5793
       1    4800    5200
Encroach Node=5755.901
       1 4957.76 5042.24
Encroach Node=5656.821
       1 4957.76 5042.24
Encroach Node=4816.264
       1 4945.76 5047.02
Encroach Node=4795.767
       1 4928.23 5072.29
Encroach Node=4749
       1 4928.23 5072.29
Encroach Node=4703.81
       1    4938 5047.02
Encroach Node=4622.833
       1 4945.76 5047.02
Encroach Node=4587.805
       1 4945.76 5047.02
Encroach Node=4269.685
       1 4926.75 5150.39
Encroach Node=4249.476
       1 4926.75    5140
Encroach Node=4151
       1    4900    5160
Encroach Node=4053.025
       1 4926.75    5131
Encroach Node=4013.035
       1 4926.75    5081
Encroach Node=3258.957
       1 4919.88 5133.51
Encroach Node=3232.411
       1 4919.88 5133.51
Encroach Node=3175
       1    4900    5150
Encroach Node=3117.381
       1 4919.88 5133.51
Encroach Node=2977.702
       1 4919.88 5133.51
Encroach Node=2212.434
       1    4700    5100
Encroach Node=2186
       1    4700    5200
Encroach Node=2159.418
       1 4695.11    5070
Encroach Node=765.1
       1 4904.64 5095.36
Encroach Reach=I100-00-00_0008
Encroach Node=31949.77
       1 4912.79 5087.21
Encroach Node=31931.78
       1 4912.79 5087.21
Encroach Node=31850
       1 4912.79 5087.21
Encroach Node=31768.21
       1 4912.79 5087.21
Encroach Node=31688.05
       1 4912.79 5087.21
Encroach Node=30886.78
       1 4972.64 5073.28
Encroach Node=30866.66
       1 4972.64 5073.28
Encroach Node=30834
       1 4972.64 5073.28
Encroach Node=30802.95
       1 4972.64 5073.28
Encroach Node=30740.23
       1 4972.64 5073.28
Encroach Node=30399.47
       1  4928.8  5071.2
Encroach Node=30379.45
       1 4915.24  5071.2
Encroach Node=30349
       1 4915.24  5071.2
Encroach Node=30319.38
       1  4928.8  5071.2
Encroach Node=30239.3
       1  4926.5  5071.2
Encroach Node=29519.8
       1 4944.37 5055.63
Encroach Node=29497.92
       1 4944.37 5055.63
Encroach Node=29465
       1 4944.37 5055.63
Encroach Node=29432.26
       1 4944.37 5055.63
Encroach Node=29340.04
       1 4944.37 5055.63
Encroach Node=28656.45
       1 4934.47 5065.53
Encroach Node=28636.38
       1 4934.47 5065.53
Encroach Node=28585
       1 4934.47 5065.53
Encroach Node=28533
       1 4934.47 5065.53
Encroach Node=28451.33
       1 4934.47 5065.53
Encroach Node=27097.22
       1 4947.82 5052.18
Encroach Node=26751.03
       1 4946.08 5053.92
Encroach Node=26262.9
       1 4932.01 5067.99
Encroach Node=26218.88
       1 4932.01 5067.99
Encroach Node=26136
       1    4800    5200
Encroach Node=26054.71
       1    4885    5100
Encroach Node=25864.96
       1    4906    5086
Encroach Node=25392.72
       1 4946.61 5078.71
Encroach Node=24331.07
       1  4936.7    5051
Encroach Node=23523.97
       1 4942.28 5057.72
Encroach Node=22206.24
       1 4939.12 5060.88
Encroach Node=21479.79
       1 4926.29 5073.71
Encroach Node=21459.79
       1 4926.29 5073.71
Encroach Node=21409
       1    4900    5100
Encroach Node=21359.64
       1    4900    5100
Encroach Node=21279.38
       1    4928 5073.71
Encroach Node=20373.4
       1    4900 5045.26
Encroach Node=20352.16
       1    4900 5045.26
Encroach Node=20304
       1 4954.74 5045.26
Encroach Node=20256.61
       1 4932.28 5045.26
Encroach Node=20171.67
       1 4929.92 5045.26
Encroach Node=19792.1
       1 4917.32 5045.26
Encroach Node=18416.74
       1 4922.24 5051.95
Encroach Node=18395.75
       1 4922.24 5051.95
Encroach Node=18364
       1 4922.24 5051.95
Encroach Node=18333.97
       1 4922.24 5051.95
Encroach Node=18251.64
       1 4958.05 5051.95
Encroach Node=17132.05
       1 4944.54 5049.05
Encroach Node=17112.04
       1 4949.19 5049.05
Encroach Node=17077
       1    4800    5200
Encroach Node=17041.88
       1 4938.22 5049.05
Encroach Node=16941.22
       1 4905.42 5049.05
Encroach Node=16097.19
       1 4919.66 5050.25
Encroach Node=15226.85
       1 4922.68 5153.24
Encroach Node=14416.41
       1 4955.79 5067.39
Encroach Node=14162.07
       1 4920.42 5042.08
Encroach Node=14142.5
       1    4908 5042.08
Encroach Node=14099
       1    4908 5042.08
Encroach Node=14055
       1    4908 5042.08
Encroach Node=13970.87
       1    4916    5050
Encroach Node=13138.31
       1 4935.72  5056.3
Encroach Node=12631.77
       1 4943.04 5045.69
Encroach Node=12324
       1 4928.76 5048.04
Encroach Node=12303.98
       1 4927.96 5049.56
Encroach Node=12295
       1 4927.96 5049.56
Encroach Node=12287.96
       1 4915.15 5088.35
Encroach Node=12234.91
       1 4873.96 5108.62
Encroach Node=12101.17
       1 4905.41 5094.59
Encroach Node=11357.13
       1    4800    5086
Encroach Node=11336.82
       1    4700 5096.12
Encroach Node=11280
       1    4690    5856
Encroach Node=11225.22
       1    4716    5159
Encroach Node=11144.42
       1 4765.58 5219.58
Encroach Node=9952.692
       1    4800    5200
Encroach Node=8674.735
       1 4940.76 5059.24
Encroach Node=8654.613
       1    4938    5065
Encroach Node=8614
       1    4850    5150
Encroach Node=8574.103
       1    4928    5056
Encroach Node=8493.352
       1    4912    5056
Encroach Node=7862.905
       1    4926    5060
Encroach Node=7431.416
       1    4850  5041.6
Encroach Node=7411.38
       1    4815  5041.6
Encroach Node=7396
       1    4800    5200
Encroach Node=7381
       1    4800 5056.79
Encroach Node=7299.108
       1    4880    5070
Encroach Node=6848.763
       1 4974.88 5110.21
Encroach Node=6838.733
       1 4974.88 5110.21
Encroach Node=6823
       1    4900 5110.21
Encroach Node=6808.516
       1 4974.88    5087
Encroach Node=6698.381
       1    4897    5120
Encroach Node=6677.703
       1    4914 5127.14
Encroach Node=6489
       1  4876.3 5127.14
Encroach Node=6300.465
       1  4876.3  5123.7
Encroach Node=6217.734
       1 4899.46 5060.19
Encroach Node=5850.572
       1 4957.76 5042.24
Encroach Node=5830.502
       1 4957.76 5042.24
Encroach Node=5793
       1    4800    5200
Encroach Node=5755.901
       1 4957.76 5042.24
Encroach Node=5656.821
       1 4957.76 5042.24
Encroach Node=4816.264
       1 4945.76 5047.02
Encroach Node=4795.767
       1 4928.23 5072.29
Encroach Node=4749
       1 4928.23 5072.29
Encroach Node=4703.81
       1    4938 5047.02
Encroach Node=4622.833
       1 4945.76 5047.02
Encroach Node=4587.805
       1 4945.76 5047.02
Encroach Node=4269.685
       1 4926.75 5150.39
Encroach Node=4249.476
       1 4926.75    5140
Encroach Node=4151
       1    4900    5160
Encroach Node=4053.025
       1 4926.75    5131
Encroach Node=4013.035
       1 4926.75    5081
Encroach Node=3258.957
       1 4919.88 5133.51
Encroach Node=3232.411
       1 4919.88 5133.51
Encroach Node=3175
       1    4900    5150
Encroach Node=3117.381
       1 4919.88 5133.51
Encroach Node=2977.702
       1 4919.88 5133.51
Encroach Node=2212.434
       1    4700    5100
Encroach Node=2186
       1    4700    5200
Encroach Node=2159.418
       1 4695.11    5070
Encroach Node=765.1
       1 4904.64 5095.36
Computation Interval=1HOUR
Output Interval=1HOUR
Run HTab= 0
Run UNet= 0
Run PostProcess= 0
UNET Theta= 1
UNET ZTol= 0.02
UNET ZSATol= 0.1
UNET MxIter= 20
UNET MaxInSteps= 20
UNET DtIC= 0
UNET DtMin= 0
UNET MaxCRTS= 20
UNET WFStab= 2
UNET SFStab= 1
UNET WFX= 1
UNET SFX= 1
UNET Convert EG Bridges=-1
UNET Use Existing IB Tables=-1
Instantaneous Interval=1HOUR
Write IC File= 0
IC Time=0
Write Velocity= 0
Write Detailed= 0

--- I100-00-00.p03 (plan) ---

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Plan Title=I100-00-00 Floodway Plan
Short Identifier=FW I100-00
Geom File=g03
Flow File=f04

--- I100-00-00.p04 (plan) ---

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Plan Title=FEMA Effective June 2007
Short Identifier=FEMAeff0607
Geom File=g03
Flow File=f04

--- I100-00-00.f01 (steady flow) ---

Flow Title=Floodway
Program Version=3.13
Number of Profiles= 2
Profile Names=1PCT_100yr,1PCTFloodway_100yrFW
River Rch & RM=I100-00-00,I100-00-00_0008 ,31949.77
    1419    1419
River Rch & RM=I100-00-00,I100-00-00_0008 ,31688.05
    1676    1676
River Rch & RM=I100-00-00,I100-00-00_0008 ,30886.78
    1728    1728
River Rch & RM=I100-00-00,I100-00-00_0008 ,30740.23
    1813    1813
River Rch & RM=I100-00-00,I100-00-00_0008 ,30379.45
    1847    1847
River Rch & RM=I100-00-00,I100-00-00_0008 ,30239.3
    2033    2033
River Rch & RM=I100-00-00,I100-00-00_0008 ,29519.8
    2082    2082
River Rch & RM=I100-00-00,I100-00-00_0008 ,29340.04
    2281    2281
River Rch & RM=I100-00-00,I100-00-00_0008 ,28656.45
    2344    2344
River Rch & RM=I100-00-00,I100-00-00_0008 ,28451.33
    2808    2808
River Rch & RM=I100-00-00,I100-00-00_0008 ,27097.22
    2821    2821
River Rch & RM=I100-00-00,I100-00-00_0008 ,26751.03
    3138    3138
River Rch & RM=I100-00-00,I100-00-00_0008 ,26262.9
    3125    3125
River Rch & RM=I100-00-00,I100-00-00_0008 ,25864.96
    3110    3110
River Rch & RM=I100-00-00,I100-00-00_0008 ,25392.72
    3076    3076
River Rch & RM=I100-00-00,I100-00-00_0008 ,24331.07
    3895    3895
River Rch & RM=I100-00-00,I100-00-00_0008 ,23523.97
    4472    4472
River Rch & RM=I100-00-00,I100-00-00_0008 ,22206.24
    4350    4350
River Rch & RM=I100-00-00,I100-00-00_0008 ,21279.38
    4234    4234
River Rch & RM=I100-00-00,I100-00-00_0008 ,20373.4
    4720    4720
River Rch & RM=I100-00-00,I100-00-00_0008 ,19792.1
    5087    5087
River Rch & RM=I100-00-00,I100-00-00_0008 ,18416.74
    5133    5133
River Rch & RM=I100-00-00,I100-00-00_0008 ,18251.64
    5455    5455
River Rch & RM=I100-00-00,I100-00-00_0008 ,17132.05
    5512    5512
River Rch & RM=I100-00-00,I100-00-00_0008 ,16941.22
    5747    5747
River Rch & RM=I100-00-00,I100-00-00_0008 ,16097.19
    5999    5999
River Rch & RM=I100-00-00,I100-00-00_0008 ,15226.85
    6244    6244
River Rch & RM=I100-00-00,I100-00-00_0008 ,14416.41
    6383    6383
River Rch & RM=I100-00-00,I100-00-00_0008 ,13970.87
    6819    6819
River Rch & RM=I100-00-00,I100-00-00_0008 ,12631.77
    7236    7236
River Rch & RM=I100-00-00,I100-00-00_0008 ,11336.82
    7300    7300
River Rch & RM=I100-00-00,I100-00-00_0008 ,11144.42
    7710    7710
River Rch & RM=I100-00-00,I100-00-00_0008 ,9952.692
    8175    8175
River Rch & RM=I100-00-00,I100-00-00_0008 ,8674.735
    8549    8549
River Rch & RM=I100-00-00,I100-00-00_0008 ,5850.572
    8908    8908
River Rch & RM=I100-00-00,I100-00-00_0008 ,3258.957
   13836   13836
River Rch & RM=I100-00-00,I100-00-00_0008 ,2212.434
   13987   13987
Boundary for River Rch & Prof#=I100-00-00,I100-00-00_0008 , 1
Up Type= 0
Dn Type= 3
Dn Slope=0.001
Boundary for River Rch & Prof#=I100-00-00,I100-00-00_0008 , 2
Up Type= 0
Dn Type= 3
Dn Slope=0.001
Observed WS=Vince           ,Main	                ,31931.78,0,,
Observed WS=Vince           ,Main           		,21459.79,0,,
Observed WS=Vince           ,Main            		,14142.5 ,0,,
Observed WS=Vince           ,Main           		,12631.77,0,,
Observed WS=Vince           ,Main           		,8654.613,0,,
Observed WS=I100-00-00      ,I100-00-00_0008      ,31931.78,0,,
Observed WS=I100-00-00      ,I100-00-00_0008      ,21459.79,0,,
Observed WS=I100-00-00      ,I100-00-00_0008      ,14142.5 ,0,,
Observed WS=I100-00-00      ,I100-00-00_0008      ,12631.77,0,,
Observed WS=I100-00-00      ,I100-00-00_0008      ,8654.613,0,,
DSS Import GetInterval= 0
DSS Import GetPeak= 0
DSS Import FillOption= 0

--- I100-00-00.f04 (steady flow) ---

Flow Title=FEMA Effective June 2007
Program Version=3.13
Number of Profiles= 4
Profile Names=10PCT_10yr, 2PCT_50yr, 1PCT_100yr, 0.2PCT_500yr
River Rch & RM=Vince,I100-00-00_0008 ,31949.77
     849    1223    1419    1968
River Rch & RM=Vince,I100-00-00_0008 ,31688.05
    1003    1444    1676    2324
River Rch & RM=Vince,I100-00-00_0008 ,30886.78
    1034    1489    1728    2396
River Rch & RM=Vince,I100-00-00_0008 ,30740.23
    1085    1562    1813    2507
River Rch & RM=Vince,I100-00-00_0008 ,30379.45
    1106    1592    1847    2552
River Rch & RM=Vince,I100-00-00_0008 ,30239.3
    1217    1753    2033    2793
River Rch & RM=Vince,I100-00-00_0008 ,29519.8
    1247    1795    2082    2856
River Rch & RM=Vince,I100-00-00_0008 ,29340.04
    1367    1967    2281    3112
River Rch & RM=Vince,I100-00-00_0008 ,28656.45
    1405    2021    2344    3193
River Rch & RM=Vince,I100-00-00_0008 ,28451.33
    1683    2422    2808    3785
River Rch & RM=Vince,I100-00-00_0008 ,27097.22
    1763    2490    2821    3703
River Rch & RM=Vince,I100-00-00_0008 ,26751.03
    1882    2708    3138    4203
River Rch & RM=Vince,I100-00-00_0008 ,26262.9
    1948    2697    3125    4195
River Rch & RM=Vince,I100-00-00_0008 ,25864.96
    2030    2684    3110    4186
River Rch & RM=Vince,I100-00-00_0008 ,25392.72
    2226    2655    3076    4167
River Rch & RM=Vince,I100-00-00_0008 ,24331.07
    2387    3375    3895    4602
River Rch & RM=Vince,I100-00-00_0008 ,23523.97
    2842    3885    4472    5388
River Rch & RM=Vince,I100-00-00_0008 ,22206.24
    2840    3791    4350    5369
River Rch & RM=Vince,I100-00-00_0008 ,21279.38
    2837    3700    4234    5352
River Rch & RM=Vince,I100-00-00_0008 ,20373.4
    3272    4178    4720    5882
River Rch & RM=Vince,I100-00-00_0008 ,19792.1
    3619    4633    5087    6219
River Rch & RM=Vince,I100-00-00_0008 ,18416.74
    3662    4691    5133    6261
River Rch & RM=Vince,I100-00-00_0008 ,18251.64
    3975    5103    5455    6552
River Rch & RM=Vince,I100-00-00_0008 ,17132.05
    4031    5177    5512    6603
River Rch & RM=Vince,I100-00-00_0008 ,16941.22
    4162    5377    5747    6885
River Rch & RM=Vince,I100-00-00_0008 ,16097.19
    4302    5591    5999    7189
River Rch & RM=Vince,I100-00-00_0008 ,15226.85
    4437    5799    6244    7484
River Rch & RM=Vince,I100-00-00_0008 ,14416.41
    4512    5916    6383    7651
River Rch & RM=Vince,I100-00-00_0008 ,13970.87
    4748    6283    6819    8176
River Rch & RM=Vince,I100-00-00_0008 ,12631.77
    4970    6609    7236    8822
River Rch & RM=Vince,I100-00-00_0008 ,11336.82
    5004    6659    7300    8922
River Rch & RM=Vince,I100-00-00_0008 ,11144.42
    5219    6976    7710    9569
River Rch & RM=Vince,I100-00-00_0008 ,9952.692
    5461    7332    8175   10315
River Rch & RM=Vince,I100-00-00_0008 ,8674.735
    5666    7650    8549   10850
River Rch & RM=Vince,I100-00-00_0008 ,5850.572
    5862    7954    8908   11365
River Rch & RM=Vince,I100-00-00_0008 ,3258.957
    8692   12064   13836   18520
River Rch & RM=Vince,I100-00-00_0008 ,2212.434
    8778   12199   13987   18778
River Rch & RM=I100-00-00,I100-00-00_0008 ,31949.77
     849    1223    1419    1968
River Rch & RM=I100-00-00,I100-00-00_0008 ,31688.05
    1003    1444    1676    2324
River Rch & RM=I100-00-00,I100-00-00_0008 ,30886.78
    1034    1489    1728    2396
River Rch & RM=I100-00-00,I100-00-00_0008 ,30740.23
    1085    1562    1813    2507
River Rch & RM=I100-00-00,I100-00-00_0008 ,30379.45
    1106    1592    1847    2552
River Rch & RM=I100-00-00,I100-00-00_0008 ,30239.3
    1217    1753    2033    2793
River Rch & RM=I100-00-00,I100-00-00_0008 ,29519.8
    1247    1795    2082    2856
River Rch & RM=I100-00-00,I100-00-00_0008 ,29340.04
    1367    1967    2281    3112
River Rch & RM=I100-00-00,I100-00-00_0008 ,28656.45
    1405    2021    2344    3193
River Rch & RM=I100-00-00,I100-00-00_0008 ,28451.33
    1683    2422    2808    3785
River Rch & RM=I100-00-00,I100-00-00_0008 ,27097.22
    1763    2490    2821    3703
River Rch & RM=I100-00-00,I100-00-00_0008 ,26751.03
    1882    2708    3138    4203
River Rch & RM=I100-00-00,I100-00-00_0008 ,26262.9
    1948    2697    3125    4195
River Rch & RM=I100-00-00,I100-00-00_0008 ,25864.96
    2030    2684    3110    4186
River Rch & RM=I100-00-00,I100-00-00_0008 ,25392.72
    2226    2655    3076    4167
River Rch & RM=I100-00-00,I100-00-00_0008 ,24331.07
    2387    3375    3895    4602
River Rch & RM=I100-00-00,I100-00-00_0008 ,23523.97
    2842    3885    4472    5388
River Rch & RM=I100-00-00,I100-00-00_0008 ,22206.24
    2840    3791    4350    5369
River Rch & RM=I100-00-00,I100-00-00_0008 ,21279.38
    2837    3700    4234    5352
River Rch & RM=I100-00-00,I100-00-00_0008 ,20373.4
    3272    4178    4720    5882
River Rch & RM=I100-00-00,I100-00-00_0008 ,19792.1
    3619    4633    5087    6219
River Rch & RM=I100-00-00,I100-00-00_0008 ,18416.74
    3662    4691    5133    6261
River Rch & RM=I100-00-00,I100-00-00_0008 ,18251.64
    3975    5103    5455    6552
River Rch & RM=I100-00-00,I100-00-00_0008 ,17132.05
    4031    5177    5512    6603
River Rch & RM=I100-00-00,I100-00-00_0008 ,16941.22
    4162    5377    5747    6885
River Rch & RM=I100-00-00,I100-00-00_0008 ,16097.19
    4302    5591    5999    7189
River Rch & RM=I100-00-00,I100-00-00_0008 ,15226.85
    4437    5799    6244    7484
River Rch & RM=I100-00-00,I100-00-00_0008 ,14416.41
    4512    5916    6383    7651
River Rch & RM=I100-00-00,I100-00-00_0008 ,13970.87
    4748    6283    6819    8176
River Rch & RM=I100-00-00,I100-00-00_0008 ,12631.77
    4970    6609    7236    8822
River Rch & RM=I100-00-00,I100-00-00_0008 ,11336.82
    5004    6659    7300    8922
River Rch & RM=I100-00-00,I100-00-00_0008 ,11144.42
    5219    6976    7710    9569
River Rch & RM=I100-00-00,I100-00-00_0008 ,9952.692
    5461    7332    8175   10315
River Rch & RM=I100-00-00,I100-00-00_0008 ,8674.735
    5666    7650    8549   10850
River Rch & RM=I100-00-00,I100-00-00_0008 ,5850.572
    5862    7954    8908   11365
River Rch & RM=I100-00-00,I100-00-00_0008 ,3258.957
    8692   12064   13836   18520
River Rch & RM=I100-00-00,I100-00-00_0008 ,2212.434
    8778   12199   13987   18778
Boundary for River Rch & Prof#=I100-00-00,I100-00-00_0008 , 1
Up Type= 0
Dn Type= 3
Dn Slope=0.001
Boundary for River Rch & Prof#=I100-00-00,I100-00-00_0008 , 2
Up Type= 0
Dn Type= 3
Dn Slope=0.001
Boundary for River Rch & Prof#=I100-00-00,I100-00-00_0008 , 3
Up Type= 0
Dn Type= 3
Dn Slope=0.001
Boundary for River Rch & Prof#=I100-00-00,I100-00-00_0008 , 4
Up Type= 0
Dn Type= 3
Dn Slope=0.001
Observed WS=Vince           ,I100-00-00_0008            ,31931.78,0,,,32.3,
Observed WS=Vince           ,I100-00-00_0008            ,21459.79,0,,,28,
Observed WS=Vince           ,I100-00-00_0008            ,14142.5 ,0,,,21.3,
Observed WS=Vince           ,I100-00-00_0008            ,12631.77,0,,,19.3,
Observed WS=Vince           ,I100-00-00_0008            ,8654.613,0,,,15.7,
Observed WS=I100-00-00      ,I100-00-00_0008      ,31931.78,0,,,32.3,
Observed WS=I100-00-00      ,I100-00-00_0008      ,21459.79,0,,,28,
Observed WS=I100-00-00      ,I100-00-00_0008      ,14142.5 ,0,,,21.3,
Observed WS=I100-00-00      ,I100-00-00_0008      ,12631.77,0,,,19.3,
Observed WS=I100-00-00      ,I100-00-00_0008      ,8654.613,0,,,15.7,
DSS Import GetInterval= 0
DSS Import GetPeak= 0
DSS Import FillOption= 0

--- I100-00-00.g01 (geometry) ---

Geom Title=I-100-00 June 2007 (Floodway)
Program Version=3.13

River Reach=I100-00-00      ,I100-00-00_0008
Reach XY= 30
     3178013.009    13802304.229      3177816.75       13804350.
      3177678.25       13804551.      3177071.25       13804723.
        3176993.       13805581.      3176611.25       13806989.
        3175009.       13809881.      3173716.75       13811605.
      3172127.25       13812309.        3171611.       13813396.
      3171304.75       13813710.       3170540.5       13813962.
       3169909.5       13815188.      3169738.75       13816081.
       3169308.5       13816803.      3169202.25       13818165.
        3169489.       13818531.        3169557.       13819454.
        3169309.       13820254.        3169463.       13821791.
        3169329.       13823448.       3169625.5       13824557.
       3169213.5       13825391.        3169286.       13826064.
       3168354.5       13827151.        3168134.       13828178.
       3167533.5       13828797.      3166874.25       13829099.
      3166729.75       13830167.        3166865.       13830748.

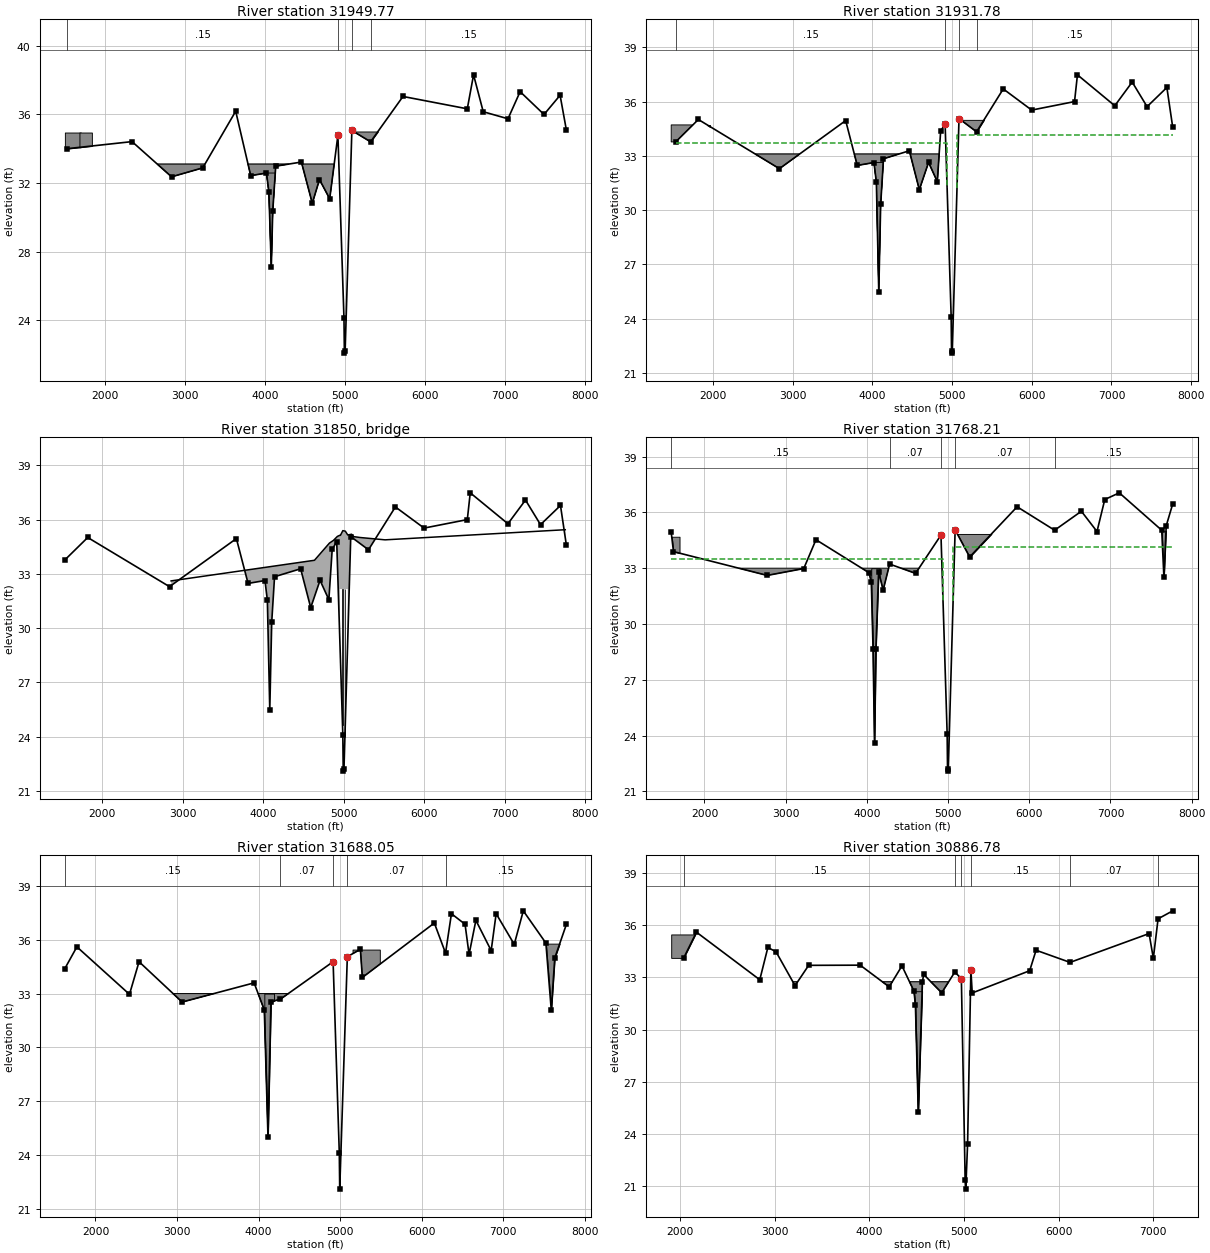
Type RM Length L Ch R = 1 ,31949.77,15.58,17.99,20.12
BEGIN DESCRIPTION:
Fairmont Parkway
END DESCRIPTION:
XS GIS Cut Line= 6
       3174349.6    13803838.512     3177722.234    13804044.889
     3178474.666    13804064.673       3178678.6      13804058.3
     3179823.005    13803863.019     3180561.747    13803886.654
#Sta/Elev= 30
 1532.62      34 2339.88   34.41 2833.65   32.36 3223.42   32.88 3635.32   36.18
  3822.9   32.43 4019.96   32.58 4050.02   31.48 4080.08   27.08 4098.26   30.36
 4135.62   32.98 4456.58   33.22 4592.66   30.82  4682.4    32.2 4810.34   31.08
 4912.79   34.78 4988.72   24.11 4993.88   22.09 5003.08   22.22 5087.21   35.06
 5321.28    34.4 5726.16   37.04 6529.98   36.32  6608.2    38.3 6729.22   36.15
  7038.6   35.74 7190.28   37.32 7489.08   35.99 7689.82   37.11 7768.92   35.07
#Mann= 4 ,-1 , 0
 1532.62     .15       0 4912.79     .03       0 5087.21     .07       0
 5321.28     .15       0
#Block Obstruct= 6 ,-1
 1500.15 1699.61   34.94 1573.38 4870.31    33.1 1682.23  1837.7   34.94
 2361.77  4894.2    33.1 4019.13 4139.41   32.58 5101.25 5682.59      35
Bank Sta=4912.79,5087.21
Exp/Cntr=0.5,0.3

Type RM Length L Ch R = 1 ,31931.78,169.45,163.57,160.74
BEGIN DESCRIPTION:
Fairmont Parkway
END DESCRIPTION:
XS GIS Cut Line= 6
      3174349.96    13803870.416     3177722.234    13804059.811
     3178474.774    13804084.679     3178680.683    13804078.245
     3179823.907     13803883.06     3180561.747    13803906.654
#Sta/Elev= 30
  1533.3   33.77  1817.5   35.01 2834.45   32.29  3665.5   34.95 3810.88   32.47
  4020.6   32.634050.659   31.54  4080.7   25.47 4104.66   30.324140.021   32.84
 4464.22   33.28 4589.46   31.134705.419   32.64 4815.16   31.57 4856.66   34.35
 4912.79   34.78 4988.72   24.11 4993.88   22.09 5003.08   22.225087.209   35.06
5307.621   34.33 5642.14    36.7  5998.9   35.53 6536.36      366572.759   37.48
  7041.2   35.77  7259.5   37.087446.339   35.72 7694.58   36.78 7768.37   34.57
#Mann= 4 ,-1 , 0
  1533.3     .15       0 4912.79     .03       05087.209     .07       0
5307.621     .15       0
#XS Ineff= 2 , 0
       0    4938    33.75061.999       0   34.15
Permanent Ineff=
       F       F
#Block Obstruct= 6 ,-1
                         1477.05 1968.36   34.71 2019.34 4886.23    33.1
 2258.25 4870.31    33.1 4020.43 4155.44   32.63 5101.25 5754.27   34.99
Bank Sta=4912.79,5087.209
Exp/Cntr=0.5,0.3

Type RM Length L Ch R = 3 ,31850   ,,,
BEGIN DESCRIPTION:
Bridge at Fairmont Parkway
END DESCRIPTION:
Bridge Culvert--1,0,-1,-1, 0
Deck Dist Width WeirC Skew NumUp NumDn MinLoCord MaxHiCord MaxSubmerge Is_Ogee
12,115,2.6,0, 17, 17, , , 0.95, 0, 0,0,,
2853.999    4636    4822    4872    4921    4950    4950    4959    49895019.999
    5050    5050    5098    5121    5203    5514    7754
   32.61   33.75    34.7   34.85   35.07   35.13   35.13   35.13   35.39   35.36
   35.15   35.15   35.19   35.06   35.01   34.88   35.44
       0       0       0       0       0       0   32.16   32.16   32.16   32.16
   32.16       0       0       0       0       0       0
2853.999    4636    4822    4872    4921    4950    4950    4959    49895019.999
    5050    5050    5098    5121    5203    5514    7754
   32.61   33.75    34.7   34.85   35.07   35.13   35.13   35.13   35.39   35.36
   35.15   35.15   35.19   35.06   35.01   34.88   35.44
       0       0       0       0       0       0   32.16   32.16   32.16   32.16
   32.16       0       0       0       0       0       0
Pier Skew, UpSta & Num, DnSta & Num=  ,4985, 2 ,4985, 2 , 0 , 0 , 0 ,,
     1.1     1.1
       0    32.5
     1.1     1.1
       0    32.5
Pier Skew, UpSta & Num, DnSta & Num=  ,5015, 2 ,5015, 2 , 0 , 0 , 0 ,,
     1.1     1.1
       0    32.5
     1.1     1.1
       0    32.5
BR Coef=-1 , 1 , 0 ,, 0 ,,,0.8,0,2,0,
WSPro=,,,, 1 ,,,, 0 ,,,, 0 ,,,,-1 ,-1 ,-1 , 0 , 0 , 0 , 0 , 0
BC Design=,, 0 ,, 0 ,,,,,,
BC HTab HWMax=37.48

Type RM Length L Ch R = 1 ,31768.21,93.86,80.16,80.2
BEGIN DESCRIPTION:
Fairmont Parkway
END DESCRIPTION:
XS GIS Cut Line= 6
      3174406.89    13804084.771     3175679.139     13804097.58
     3178475.641     13804244.73     3178697.347    13804237.802
     3179831.121    13804043.392     3180561.747    13804066.654
#Sta/Elev= 30
 1590.33   34.93 1618.51   33.89 2772.59   32.613222.979   32.98 3373.32   34.53
 4024.62   32.764054.839   32.27 4076.38   28.65 4094.12   23.61 4110.78   28.63
    4145   32.81 4200.74   31.82  4280.5   33.22 4599.76   32.72 4912.79   34.78
 4988.72   24.11 4993.88   22.09 5003.08   22.225087.209   35.06 5266.06    33.6
 5850.46    36.3 6312.48   35.046641.919   36.06  6834.2   34.976930.139   36.69
 7108.84   37.057631.479   35.04  7658.6    32.57686.939   35.287767.259   36.46
#Mann= 5 ,-1 , 0
 1590.33     .15       0  4280.5     .07       0 4912.79     .03       0
5087.209     .07       0 6312.48     .15       0
#XS Ineff= 2 , 0
       0    4938    33.55061.999       0   34.15
Permanent Ineff=
       F       F
#Block Obstruct= 5 ,-1
 1342.43 1692.83   34.69 2091.01 4846.42      33 4054.27 4157.45      33
 5101.25 5674.63   34.84 7506.26 7864.62   35.01
Bank Sta=4912.79,5087.209
Exp/Cntr=0.5,0.3

Type RM Length L Ch R = 1 ,31688.05,309.79,801.26,995.69
BEGIN DESCRIPTION:
Fairmont Parkway
END DESCRIPTION:
XS GIS Cut Line= 6
      3174435.69     13804166.38     3175683.406    13804178.011
     3178476.075    13804324.756     3178705.678    13804317.581
     3179834.728    13804123.558     3180561.747    13804146.654
#Sta/Elev= 30
  1624.7    34.4 1772.07   35.61 2416.68   32.96 2534.05   34.78 3061.94   32.53
 3944.35    33.6 4069.38   32.09 4114.47   25.02 4150.92   32.54 4266.79   32.69
 4912.79   34.78 4988.72   24.11 4993.88   22.09 5087.21   35.06 5247.14   35.47
 5271.37    33.9 6153.62   36.94 6291.14   35.26 6363.27   37.46 6530.25   36.87
 6579.49   35.19 6663.04   37.09 6850.39    35.4 6911.37   37.46 7133.24   35.75
 7244.29   37.62 7521.21   35.82 7587.23   32.08 7630.13   34.99  7772.8   36.87
#Mann= 5 ,-1 , 0
  1624.7     .15       0 4266.79     .07       0 4912.79     .03       0
 5087.21     .07       0 6291.14     .15       0
#Block Obstruct= 5 ,-1
 1971.56 4703.07      33 2035.27 4790.67      33 4069.56 4188.47      33
    5157 5491.47   35.43 7482.37 7745.17   35.79
Bank Sta=4912.79,5087.21
Exp/Cntr=0.3,0.1

Type RM Length L Ch R = 1 ,30886.78,20,20.12,21.06
BEGIN DESCRIPTION:
Federal Road
END DESCRIPTION:
XS GIS Cut Line= 6
       3174445.3    13804199.984     3175505.885    13804206.488
     3177077.556    13804287.201     3177131.273    13804512.087
     3177386.138    13804965.995     3179168.591     13805025.42
#Sta/Elev= 30
 2037.08   34.13 2171.54   35.61 2841.01   32.87 2926.61   34.73  3013.1   34.48
 3213.92   32.53 3357.99    33.7 3902.77   33.71  4209.4   32.46 4344.63   33.67
 4471.97   32.21 4486.99   31.39 4517.03   25.28    4561   32.74 4573.58   33.18
 4764.76   32.12 4903.14   33.31 4972.64   32.94 5012.88   21.36  5019.1   20.81
 5038.56   23.41 5073.28   33.42 5087.62   32.11 5695.02   33.39 5762.72   34.57
 6122.09   33.87 6957.66   35.53 7002.68   34.11 7052.85   36.38 7207.98   36.84
#Mann= 6 ,-1 , 0
 2037.08     .15       0 4903.14     .07       0 4972.64     .03       0
 5073.28     .15       0 6122.09     .07       0 7052.85     .15       0
#Block Obstruct= 4 ,-1
 1904.44 2177.47   35.48 2464.16 4853.24   32.75 2539.25  4894.2   32.75
 4449.39 4659.62   32.21
Bank Sta=4972.64,5073.28
Exp/Cntr=0.5,0.3

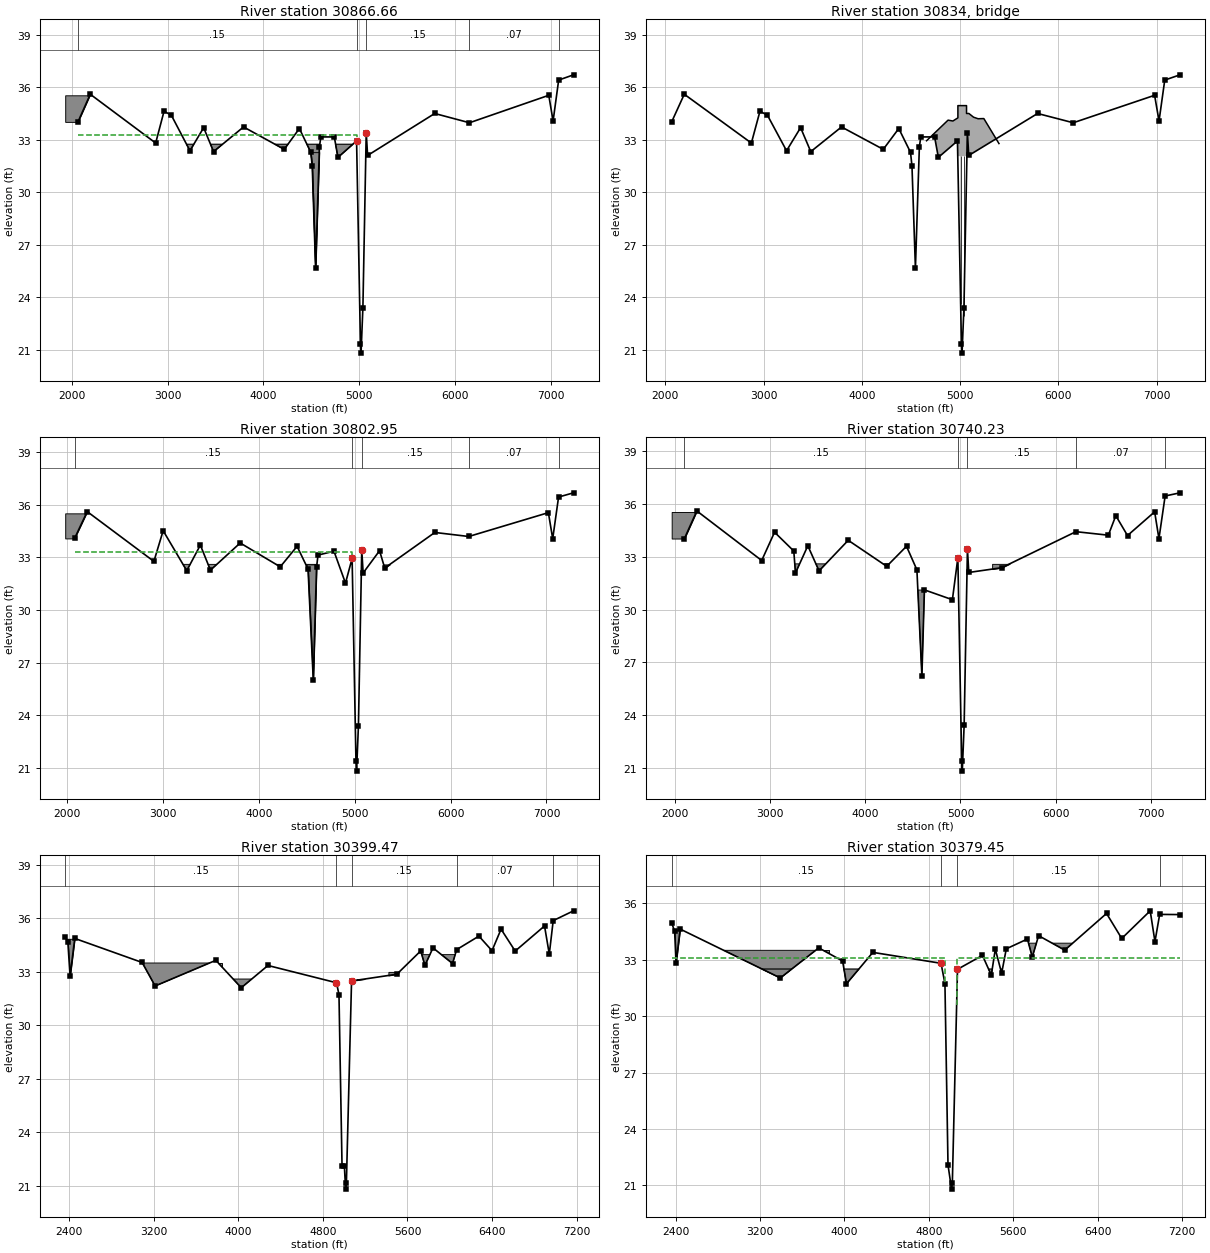
Type RM Length L Ch R = 1 ,30866.66,48.88,63.71,81.3
BEGIN DESCRIPTION:
Federal Road
END DESCRIPTION:
XS GIS Cut Line= 6
       3174450.1    13804214.385     3175472.626     13804223.76
     3177059.407    13804301.075     3177112.701    13804519.643
     3177370.656    13804979.378      3179176.62    13805045.493
#Sta/Elev= 30
 2064.95   34.03 2193.14   35.61  2875.8   32.82 2963.21   34.64 3039.35   34.41
 3233.69   32.38 3376.59    33.7 3480.17   32.33 3792.99   33.74  4217.7   32.46
 4375.61   33.65 4494.92   32.29 4509.94    31.5 4544.93   25.66 4585.03    32.6
 4599.56   33.17 4740.18   33.17 4778.22      32 4972.64   32.94 5012.88   21.36
  5019.1   20.81 5038.56   23.41 5073.28   33.42 5087.62   32.11 5787.93   34.51
 6150.74   33.98 6978.48   35.55  7023.5   34.08 7081.68   36.42 7236.84   36.72
#Mann= 5 ,-1 , 0
 2064.95     .15       0 4972.64     .03       0 5073.28     .15       0
 6150.74     .07       0 7081.68     .15       0
#XS Ineff= 2 , 0
       0 4972.64    33.3 5073.28       0      33
Permanent Ineff=
       F       F
#Block Obstruct= 4 ,-1
 1931.74 2197.95   35.55 2557.19 4941.91   32.75 2621.16 4935.15   32.75
 4484.56 4639.39    32.3
Bank Sta=4972.64,5073.28
Exp/Cntr=0.3,0.3

Type RM Length L Ch R = 3 ,30834   ,,,
BEGIN DESCRIPTION:
Bridge at Federal Road
END DESCRIPTION:
Bridge Culvert--1,0,-1,-1, 0
Deck Dist Width WeirC Skew NumUp NumDn MinLoCord MaxHiCord MaxSubmerge Is_Ogee
11,35,2.6,0, 14, 14, , , 0.95, 0, 0,0,,
    4658    4877    4926    4977    4977    4998    5038    5065    5065    5089
    5136    5182    5241    5395
   32.95   34.13   34.08   34.26   34.96   34.96   34.96   34.96   34.51   34.51
    34.3   34.21   34.22   32.79
       0       0       0       0   32.07   32.07   32.07   32.07       0       0
       0       0       0       0
    4658    4877    4926    4977    4977    4998    5038    5065    5065    5089
    5136    5182    5241    5395
   32.95   34.13   34.08   34.26   34.96   34.96   34.96   34.96   34.51   34.51
    34.3   34.21   34.22   32.79
       0       0       0       0   32.07   32.07   32.07   32.07       0       0
       0       0       0       0
Pier Skew, UpSta & Num, DnSta & Num=  ,5005, 2 ,5005, 2 , 0 , 0 , 0 ,,
     1.1     1.1
       0      33
     1.1     1.1
       0      33
Pier Skew, UpSta & Num, DnSta & Num=  ,5035, 2 ,5035, 2 , 0 , 0 , 0 ,,
     1.1     1.1
       0      33
     1.1     1.1
       0      33
BR Coef=-1 , 1 , 0 ,, 0 ,,,0.8,0,2,0,
WSPro=,,,, 1 ,,,, 0 ,,,, 0 ,,,,-1 ,-1 ,-1 , 0 , 0 , 0 , 0 , 0
BC Design=,, 0 ,, 0 ,,,,,,
BC HTab HWMax=36.81

Type RM Length L Ch R = 1 ,30802.95,45.76,62.72,71.22
BEGIN DESCRIPTION:
Federal Road
END DESCRIPTION:
XS GIS Cut Line= 6
       3174445.3    13804223.987     3175467.852    13804242.319
      3177008.42    13804309.158     3177077.807    13804593.975
     3177287.654     13804995.12     3179180.634    13805057.536
#Sta/Elev= 30
 2077.17   34.08  2209.1   35.61 2904.69   32.77 3001.26   34.52 3247.55   32.24
  3389.4    33.7 3494.67   32.27 3805.03   33.82  4222.8   32.46 4398.52   33.63
  4512.8   32.33 4567.34   26.03 4601.81   32.44 4616.82   33.13 4783.32   33.35
 4903.48   31.53 4972.64   32.94 5012.88   21.36  5019.1   20.81 5038.56   23.41
 5073.28   33.42 5087.62   32.11 5259.06   33.38 5312.68   32.39  5835.6   34.42
 6189.44   34.19 7020.25   35.55 7065.26   34.06 7126.41   36.44 7282.57   36.68
#Mann= 5 ,-1 , 0
 2077.17     .15       0 4972.64     .03       0 5073.28     .15       0
 6189.44     .07       0 7126.41     .15       0
#XS Ineff= 2 , 0
       0 4972.64    33.3 5073.28       0      33
Permanent Ineff=
       F       F
#Block Obstruct= 4 ,-1
 1979.52 2218.43   35.51 2634.81 4778.16    32.6 4498.25 4660.89    32.6
 5221.84 5583.62    32.6
Bank Sta=4972.64,5073.28
Exp/Cntr=0.5,0.3

Type RM Length L Ch R = 1 ,30740.23,755.11,340.76,81.13
BEGIN DESCRIPTION:
Federal Road
END DESCRIPTION:
XS GIS Cut Line= 6
       3174445.3    13804238.388     3176965.086     13804330.24
     3177056.103    13804673.557      3177240.46    13805010.121
     3178072.551    13805058.697     3179184.649     13805069.58
#Sta/Elev= 30
 2099.88   34.04 2230.32   35.61 2911.67   32.79 3046.84    34.4 3248.85   33.33
 3266.68   32.08 3396.39   33.63 3514.33    32.2 3820.84   33.94 4225.16   32.46
 4433.05    33.6 4542.36   32.26 4594.74   26.22 4621.49   31.12 4915.22   30.56
 4972.64   32.94 5012.88   21.36  5019.1   20.81 5038.56   23.41 5073.28   33.42
 5087.62   32.11 5432.82   32.38 6213.15   34.43  6553.7   34.23 6632.11   35.34
 6755.06   34.21 7040.26   35.56 7085.26   34.03 7150.36   36.46 7306.56   36.64
#Mann= 5 ,-1 , 0
 2099.88     .15       0 4972.64     .03       0 5073.28     .15       0
 6213.15     .07       0 7150.36     .15       0
#XS Ineff= 1 ,-1
    4440    4970   32.65
Permanent Ineff=
       F
#Block Obstruct= 5 ,-1
 1965.87 2232.08   35.55 2689.42  4395.9    32.6 4529.07 4627.29   31.11
 5332.74 5558.22    32.6 6068.26 6259.39    33.9
Bank Sta=4972.64,5073.28
Exp/Cntr=0.3,0.1

Type RM Length L Ch R = 1 ,30399.47,20,20.02,20.05
BEGIN DESCRIPTION:
Llano Street
END DESCRIPTION:
XS GIS Cut Line= 6
      3174390.51     13804894.29       3176952.8    13805044.252
     3177095.204    13805048.221     3177301.024    13805062.041
     3178088.678    13805089.609     3179192.678    13805089.653
#Sta/Elev= 30
 2363.06   34.97 2388.23   34.66 2409.16   32.76 2453.41   34.88  3090.4   33.53
 3213.62   32.21 3787.73   33.65 4028.24   32.11 4280.52   33.36  4928.8   32.39
 4952.21   31.73 4981.24   22.09 5003.24   22.11  5014.9    20.8 5022.33   21.13
  5071.2   32.49 5499.83   32.87 5725.54   34.18    5765   33.36 5841.32   34.35
 6026.27   33.47 6064.87   34.25 6275.75   35.01 6399.48   34.19  6485.2    35.4
 6618.74   34.17 6896.29   35.58 6941.29      34  6978.3   35.88 7170.61   36.43
#Mann= 5 ,-1 , 0
 2363.06     .15       0  4928.8     .03       0  5071.2     .15       0
 6064.87     .07       0  6978.3     .15       0
#Block Obstruct= 6 ,-1
 2354.02 2454.66   34.86 2976.11 4491.47    32.6  5419.8  5658.7      33
 5720.14 6436.86   33.97    2900    3850    33.5    5120    5200    32.6
Bank Sta=4928.8,5071.2
Exp/Cntr=0.5,0.3

Type RM Length L Ch R = 1 ,30379.45,60.01,60.07,60.62
BEGIN DESCRIPTION:
Llano Street
END DESCRIPTION:
XS GIS Cut Line= 6
      3174389.35    13804914.256     3176951.912    13805064.235
     3177094.255    13805068.202     3177300.004    13805082.017
     3178080.521    13805109.335     3179200.707    13805121.769
#Sta/Elev= 30
 2362.81   34.96 2390.92   34.51 2404.04   32.82 2443.22   34.63 3392.36   32.03
  3756.8   33.63 3982.44   32.93  4019.3   31.72  4269.1   33.39 4915.24   32.81
 4952.21   31.73 4981.24   22.09  5014.9    20.8 5022.33   21.13  5071.2   32.49
 5307.68   33.23 5391.46   32.18  5429.6   33.56 5489.48   32.28  5533.6   33.58
 5733.74    34.1 5779.98   33.14  5839.6   34.28 6087.54   33.51 6483.42   35.46
 6627.49   34.13 6897.25    35.6 6942.25   33.96 6986.94   35.41 7179.61    35.4
#Mann= 4 ,-1 , 0
 2362.81     .15       0 4915.24     .03       0  5071.2     .15       0
 6986.94     .15       0
#XS Ineff= 2 , 0
       0    4951    33.1    5063       0    33.1
Permanent Ineff=
       F       F
#Block Obstruct= 7 ,-1
 2327.62 2444.14    34.6    2850    3850    33.5 2969.28 4457.34    32.5
 3092.15 4566.55    32.5 5310.58 5563.14    32.5 5311.09  5547.1    32.5
 5726.96 6443.69   33.88
Bank Sta=4915.24,5071.2
Exp/Cntr=0.5,0.3