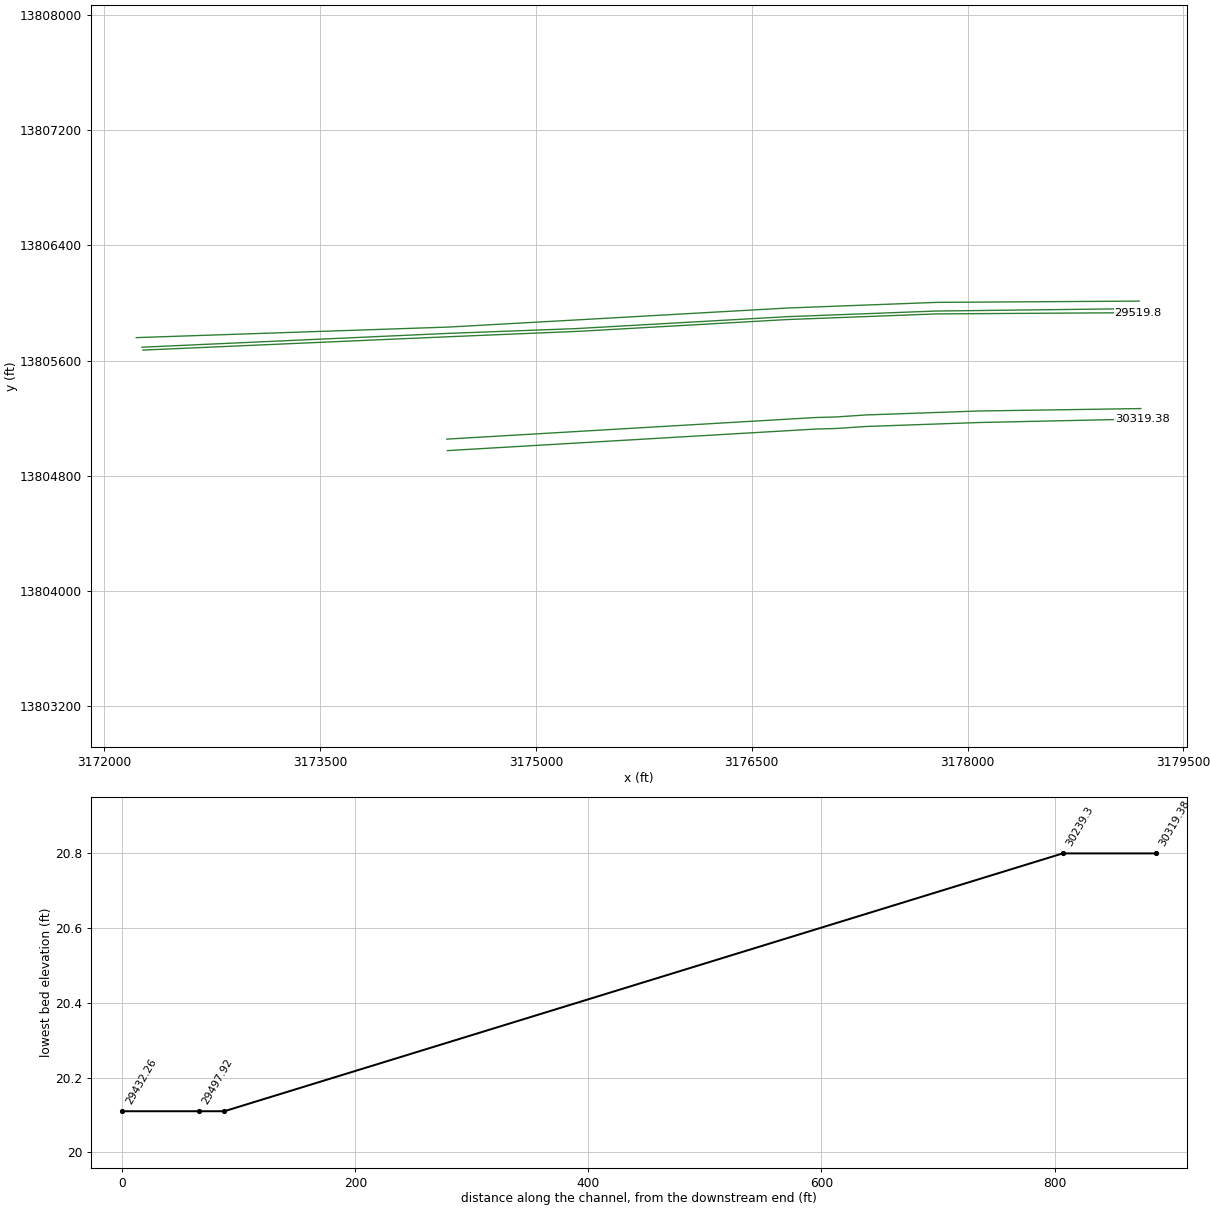
HEC-RAS study I100-00-00.prj: I100-00-00

--- I100-00-00.g01 (geometry) --- (continued)

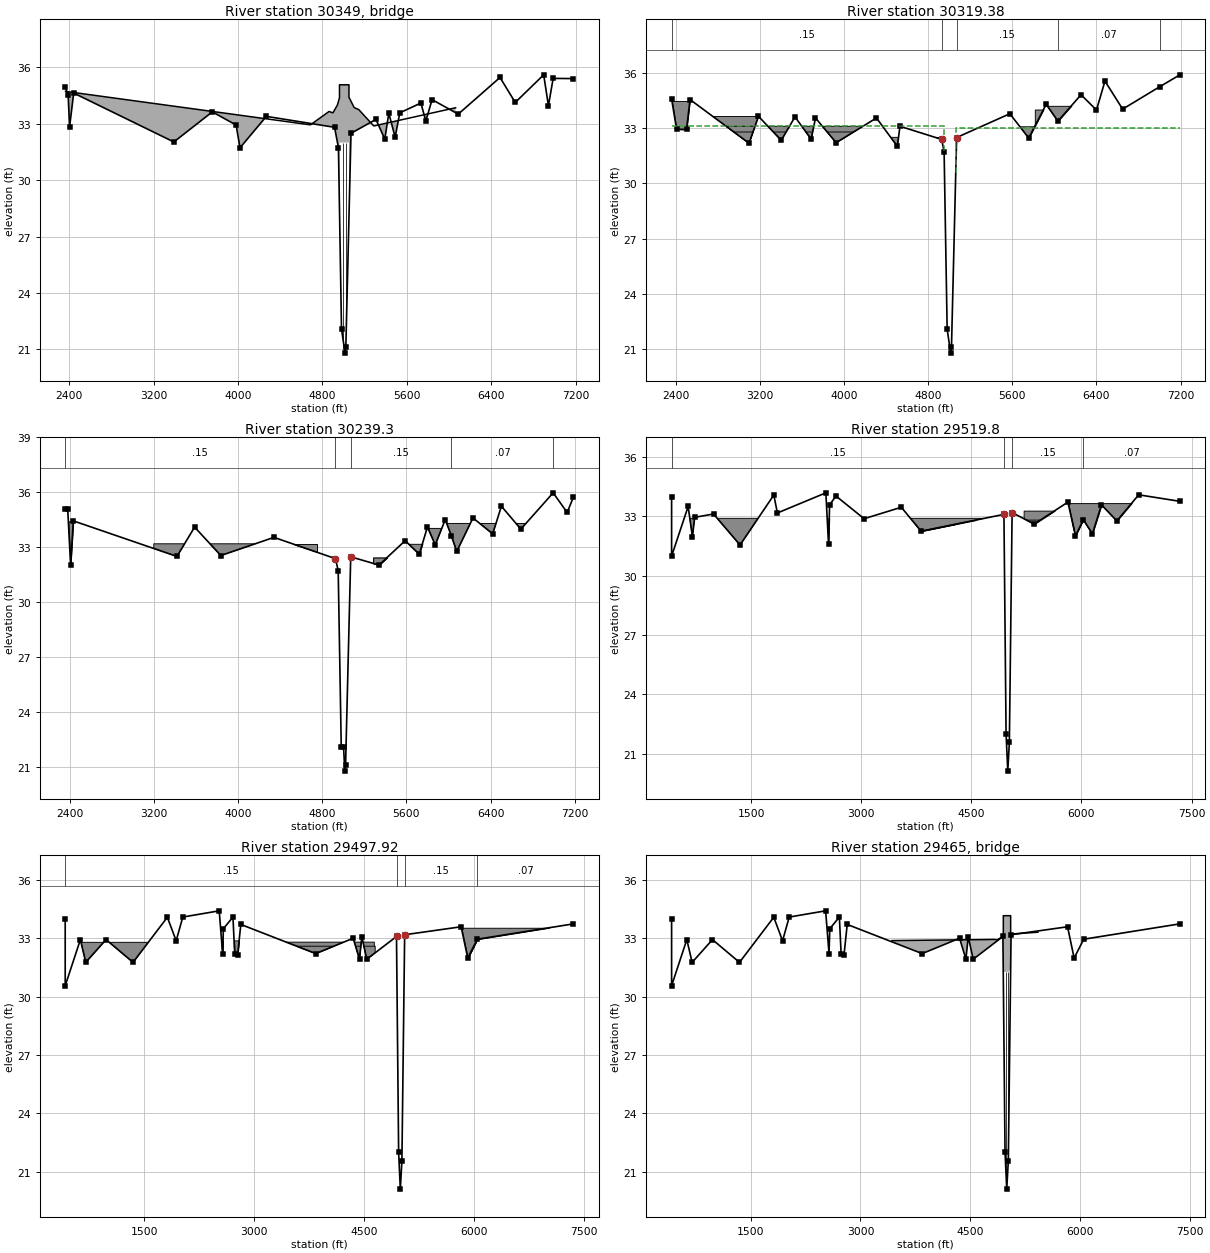
Type RM Length L Ch R = 3 ,30349   ,,,
BEGIN DESCRIPTION:
Bridge at Llano Street
END DESCRIPTION:
Bridge Culvert--1,0,-1,-1, 0
Deck Dist Width WeirC Skew NumUp NumDn MinLoCord MaxHiCord MaxSubmerge Is_Ogee
5,35,2.6,0, 14, 14, , , 0.95, 0, 0,0,,
    2366    4687    4863    4900    4942    4962    4962    5004    5052    5052
    5101    5145    5287    6063
   34.72   32.94   33.65   33.58   33.99   34.38   35.07   35.07   35.07   34.41
   33.86   33.75   32.88   33.85
       0       0       0       0       0       0      32      32      32       0
       0       0       0       0
    2366    4687    4863    4900    4942    4962    4962    5004    5052    5052
    5101    5145    5287    6063
   34.72   32.94   33.65   33.58   33.99   34.38   35.07   35.07   35.07   34.41
   33.86   33.75   32.88   33.85
       0       0       0       0       0       0      32      32      32       0
       0       0       0       0
Pier Skew, UpSta & Num, DnSta & Num=  ,4995, 2 ,4995, 2 , 0 , 0 , 0 ,,
     1.1     1.1
       0      33
     1.1     1.1
       0      33
Pier Skew, UpSta & Num, DnSta & Num=  ,5025, 2 ,5025, 2 , 0 , 0 , 0 ,,
     1.1     1.1
       0      33
     1.1     1.1
       0      33
BR Coef=-1 , 1 , 0 ,, 0 ,,,0.8,0,2,0,
WSPro=,,,, 1 ,,,, 0 ,,,, 0 ,,,,-1 ,-1 ,-1 , 0 , 0 , 0 , 0 , 0
BC Design=,, 0 ,, 0 ,,,,,,
BC HTab HWMax=35.6

Type RM Length L Ch R = 1 ,30319.38,80.02,80.08,81.14
BEGIN DESCRIPTION:
Llano Street
END DESCRIPTION:
XS GIS Cut Line= 6
      3174385.87    13804974.155     3176949.249    13805124.184
     3177091.408    13805128.146     3177296.944    13805141.947
     3178076.518    13805169.232     3179212.751    13805194.031
#Sta/Elev= 30
 2361.44   34.58 2408.45   32.94 2503.44   32.93  2536.4   34.55 3097.96   32.18
 3187.45   33.64 3403.78   32.34 3534.38   33.61 3688.36    32.4 3729.42   33.55
 3925.83   32.21 4309.04   33.55 4508.06   32.01 4532.37    33.1  4928.8   32.39
 4952.21   31.73 4981.24   22.09  5014.9    20.8 5022.33   21.13  5071.2   32.49
 5577.46   33.78 5756.78   32.46 5922.41   34.29 6034.16   33.38 6254.14   34.81
 6400.93   33.98 6481.58   35.55 6649.66   34.03 7000.67   35.24 7193.97   35.89
#Mann= 5 ,-1 , 0
 2361.44     .15       0  4928.8     .03       0  5071.2     .15       0
 6034.16     .07       0 7000.67     .15       0
#XS Ineff= 2 , 0
       0    4951    33.1    5063       0      33
Permanent Ineff=
       F       F
#Block Obstruct= 11 ,-1
 2177.47  2552.9   34.47  2680.3 3193.13   33.63 2764.51 4197.95    33.1
 2832.76 4232.08   32.79 4290.67  4890.8    32.5 5154.76 5299.51   32.49
 5283.28 6006.83    32.5 5310.58  6395.9    32.5    5625    5810    33.1
 5814.64 5930.54   34.01 5931.74 6232.08   34.21
Bank Sta=4928.8,5071.2
Exp/Cntr=0.5,0.3

Type RM Length L Ch R = 1 ,30239.3 ,716.68,719.49,692.48
BEGIN DESCRIPTION:
Llano Street
END DESCRIPTION:
XS GIS Cut Line= 6
      3174381.23     13805054.02     3176945.698    13805204.116
     3177087.613    13805208.071     3177292.864    13805221.853
     3178080.536    13805249.422     3179204.722    13805266.293
#Sta/Elev= 30
 2358.54   35.12 2382.22    35.1 2409.94   32.03  2435.6   34.45  3420.3   32.51
 3587.92   34.11 3837.26   32.56 4341.86   33.55  4926.5   32.39 4952.21   31.73
 4981.24   22.09 5003.24   22.11  5014.9    20.8 5022.33   21.13  5071.2   32.49
 5339.68   32.04 5588.34   33.37 5722.42   32.63 5800.26   34.12 5874.14   33.14
 5969.28   34.52 6028.58   33.62 6078.34   32.78 6232.79   34.61 6419.98   33.74
 6502.66   35.25 6687.52      34 6994.38   35.98 7127.38   34.91 7187.54   35.75
#Mann= 5 ,-1 , 0
 2358.54     .15       0  4926.5     .03       0  5071.2     .15       0
 6028.58     .07       0 6994.38     .15       0
#Block Obstruct= 10 ,-1
 2360.92 2435.84   34.43 3201.37 4873.72   32.45 4630.32 4723.19   32.45
 5283.88 5516.83   32.45 5284.49  5815.5   32.45  5658.7  6205.8   32.45
  5788.4 5979.52   34.04  5972.7 7194.54   34.31    3200    4750    33.2
    5575    5815    33.2
Bank Sta=4926.5,5071.2
Exp/Cntr=0.3,0.1

Type RM Length L Ch R = 1 ,29519.8 ,21.54,21.89,20.56
BEGIN DESCRIPTION:
 Pampa Street
END DESCRIPTION:
XS GIS Cut Line= 6
      3172270.11    13805672.676     3174361.036    13805764.018
     3175305.764    13805803.376     3176745.543    13805884.727
     3177783.443    13805924.048     3179184.649    13805932.708
#Sta/Elev= 30
  418.68      34  418.68   30.99  643.77    33.5  701.95   31.97  733.02   32.95
  989.68   33.12 1350.53   31.55 1810.53   34.08 1859.05   33.17 2519.21   34.19
 2555.36   31.61 2570.37   33.58 2656.38   34.03 3040.31   32.88 3546.65   33.46
 3816.22   32.25 4944.37    33.1 4973.46      22 4996.63   20.11 5018.33   21.58
 5055.63   33.19    5357   32.61 5815.28   33.72 5918.66   32.01 6025.34   32.83
 6148.82   32.12 6272.88   33.58  6481.8   32.77 6779.48   34.09  7340.5   33.76
#Mann= 4 ,-1 , 0
  418.68     .15       0 4944.37     .03       0 5055.63     .15       0
 6025.34     .07       0
#Block Obstruct= 9 ,-1
 2440.12 2659.56    32.9 3569.97 4641.64   32.81  3658.7 4703.07    32.6
 5212.51 5801.88   33.29  5262.8 6621.16   32.81  5262.8 6313.99    32.6
 5800.81 7385.37   33.67    2850    4675    32.9   410.2    2300    32.9
Bank Sta=4944.37,5055.63
Exp/Cntr=0.5,0.3

Type RM Length L Ch R = 1 ,29497.92,64.6,65.66,61.1
BEGIN DESCRIPTION:
 Pampa Street
END DESCRIPTION:
XS GIS Cut Line= 6
      3172263.45    13805692.657     3174388.054    13805788.561
     3175275.601    13805821.704     3176744.606    13805904.706
     3177779.436     13805943.91     3179192.678     13805960.81
#Sta/Elev= 30
  422.78      34  422.78   30.57  630.13   32.94  702.97   31.77  980.25   32.94
 1349.17   31.77 1816.96   34.09  1937.3   32.88 2027.57    34.1 2524.74   34.42
 2571.22   32.22 2581.72    33.5 2712.27    34.1 2736.17   32.21 2775.42   32.14
 2819.42   33.72 3842.58   32.22 4352.63   33.01 4439.41   31.94 4471.39   33.09
 4538.56   31.93 4944.37    33.1 4973.46      22 4996.63   20.11 5018.33   21.58
 5055.63   33.19 5826.46    33.6 5916.58   31.99 6047.46   32.96 7359.82   33.75
#Mann= 4 ,-1 , 0
  422.78     .15       0 4944.37     .03       0 5055.63     .15       0
 6047.46     .07       0
#XS Ineff= 2 , 0
       0 4944.37    32.9 5055.63       0   33.19
Permanent Ineff=
       F       F
#Block Obstruct= 9 ,-1
 2389.08 2682.59    32.9 2430.03 4641.64   32.81 2504.86 4653.67    32.6
 2627.99 2832.76    32.9 5070.87  5798.4   33.16 5126.28 6641.64   32.81
 5315.86 6253.37    32.6 5829.35 7269.62   33.55   410.2    2300    32.8
Bank Sta=4944.37,5055.63
Exp/Cntr=0.5,0.3

Type RM Length L Ch R = 3 ,29465   ,,,
BEGIN DESCRIPTION:
Bridge at Pampa Street
END DESCRIPTION:
Bridge Culvert--1,0,-1,-1, 0
Deck Dist Width WeirC Skew NumUp NumDn MinLoCord MaxHiCord MaxSubmerge Is_Ogee
12,40,2.6,0, 11, 12, , , 0.95, 0, 0,0,,
    3429    4678    4820    4867    4908    4950    4950    5050    5050    5101
    5422
   32.89   32.94   32.95   32.93   33.02   33.02   34.17   34.17   33.24   33.24
   33.32
       0       0       0       0       0       0   31.28   31.28       0       0
       0
    3429    4678    4820    4867    4908    4950    4950    5050    5050    5101
    5422    5470
   32.89   32.94   32.95   32.93   33.02   33.02   34.17   34.17   33.24   33.24
   33.32    33.3
       0       0       0       0       0       0   31.28   31.28       0       0
       0       0
Pier Skew, UpSta & Num, DnSta & Num=  ,4985, 2 ,4985, 2 , 0 , 0 , 0 ,,
     1.2     1.2
       0      32
     1.2     1.2
       0      32
Pier Skew, UpSta & Num, DnSta & Num=  ,5015, 2 ,5015, 2 , 0 , 0 , 0 ,,
     1.2     1.2
       0      32
     1.2     1.2
       0      32
BR Coef=-1 , 1 , 0 ,, 0 ,,,0.8,0,2,0,
WSPro=,,,, 1 ,,,, 0 ,,,, 0 ,,,,-1 ,-1 ,-1 , 0 , 0 , 0 , 0 , 0
BC Design=,, 0 ,, 0 ,,,,,,
BC HTab HWMax=34.43

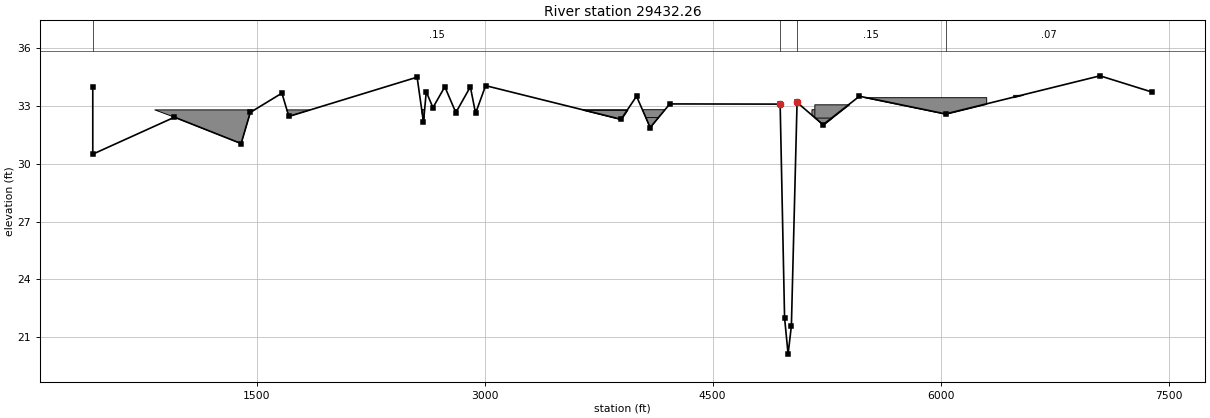
Type RM Length L Ch R = 1 ,29432.26,81.88,92.22,81.83
BEGIN DESCRIPTION:
 Pampa Street
END DESCRIPTION:
XS GIS Cut Line= 6
      3172223.49    13805759.262      3174395.18    13805832.632
     3175281.734    13805882.146     3176741.795    13805964.643
     3177783.299      13806004.1     3179192.678    13806012.999
#Sta/Elev= 30
  420.98      34  420.98    30.5  958.53   32.42  1397.2   31.05 1457.76   32.67
 1665.56   33.67 1711.29   32.46 2555.36    34.5  2597.3   32.16 2615.45   33.74
 2659.58   32.92 2737.67      34 2810.33   32.66 2905.74      34 2939.99   32.62
 3006.06   34.06 3897.46   32.31 3999.22   33.51 4089.15   31.88 4218.16   33.11
 4944.37    33.1 4973.46      22 4996.63   20.11 5018.33   21.58 5055.63   33.19
 5226.75   32.03 5466.11   33.51 6033.04   32.59 7049.44   34.57 7394.22   33.72
#Mann= 4 ,-1 , 0
  420.98     .15       0 4944.37     .03       0 5055.63     .15       0
 6033.04     .07       0
#XS Ineff= 2 , 0
       0 4944.37    32.9 5055.63       0   33.19
Permanent Ineff=
       F       F
#Block Obstruct= 11 ,-1
  2368.6 4375.43   32.81 2382.25 3010.24    32.8 2530.23 4359.96    32.4
 3010.24  3290.1    32.8 3317.41  3972.7    32.8 5153.58  6580.2   32.81
 5169.32 5496.75   33.09 5169.38 6344.02    32.4 5460.75 6300.34   33.46
 6477.82 6901.02   33.58   410.5    2100    32.8
Bank Sta=4944.37,5055.63
Exp/Cntr=0.5,0.3