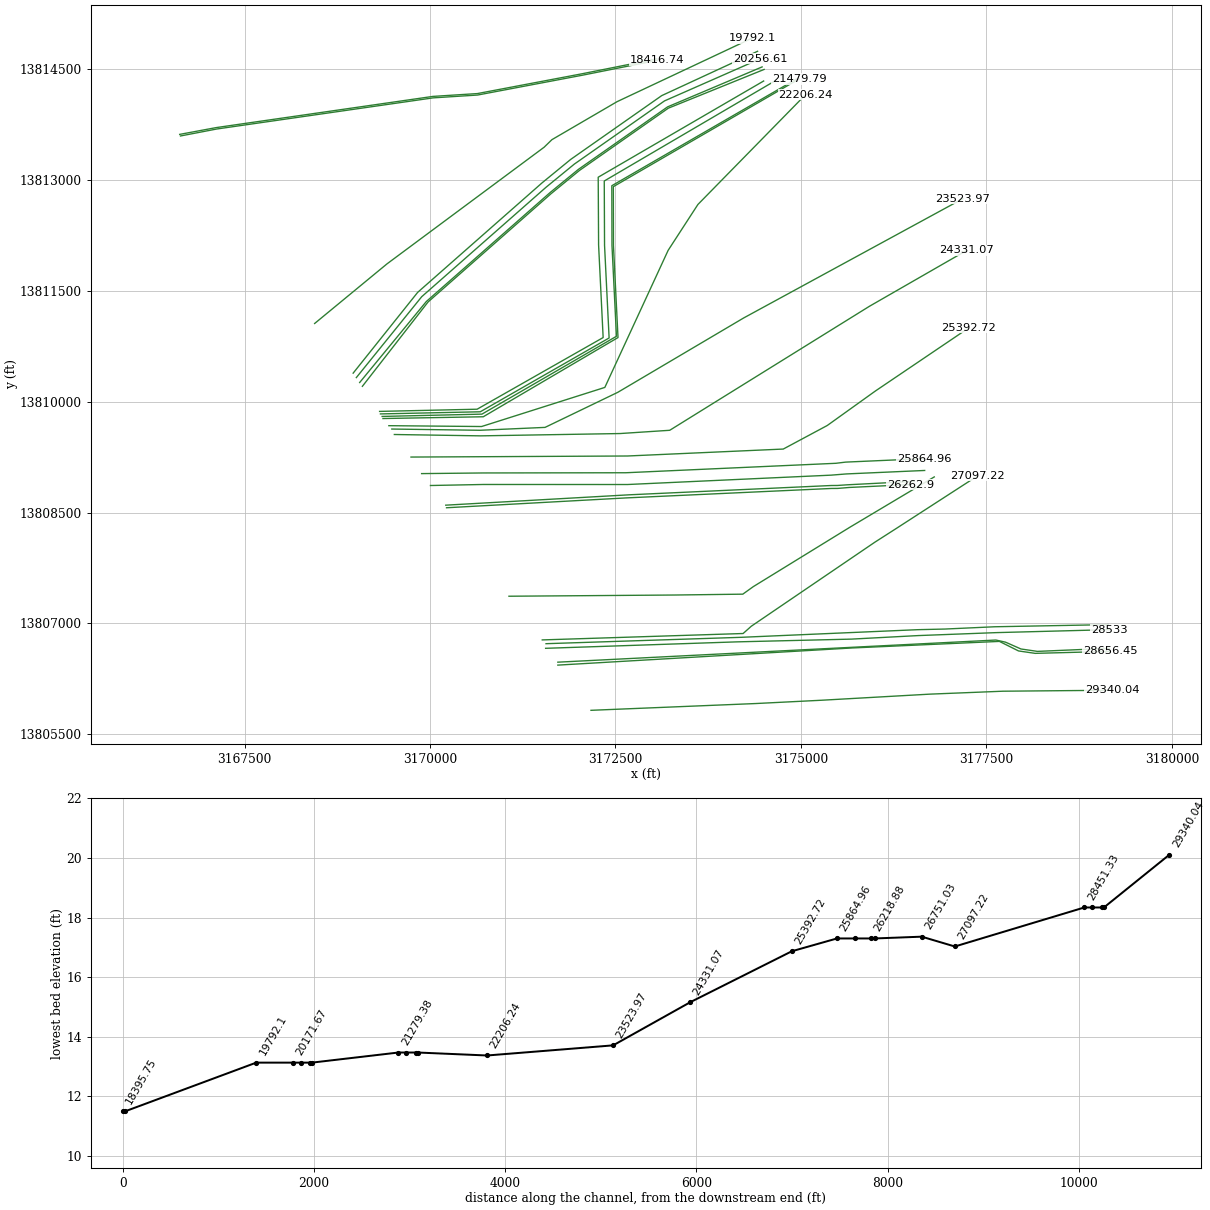
HEC-RAS study I100-00-00.prj: I100-00-00

--- I100-00-00.g01 (geometry) --- (continued)

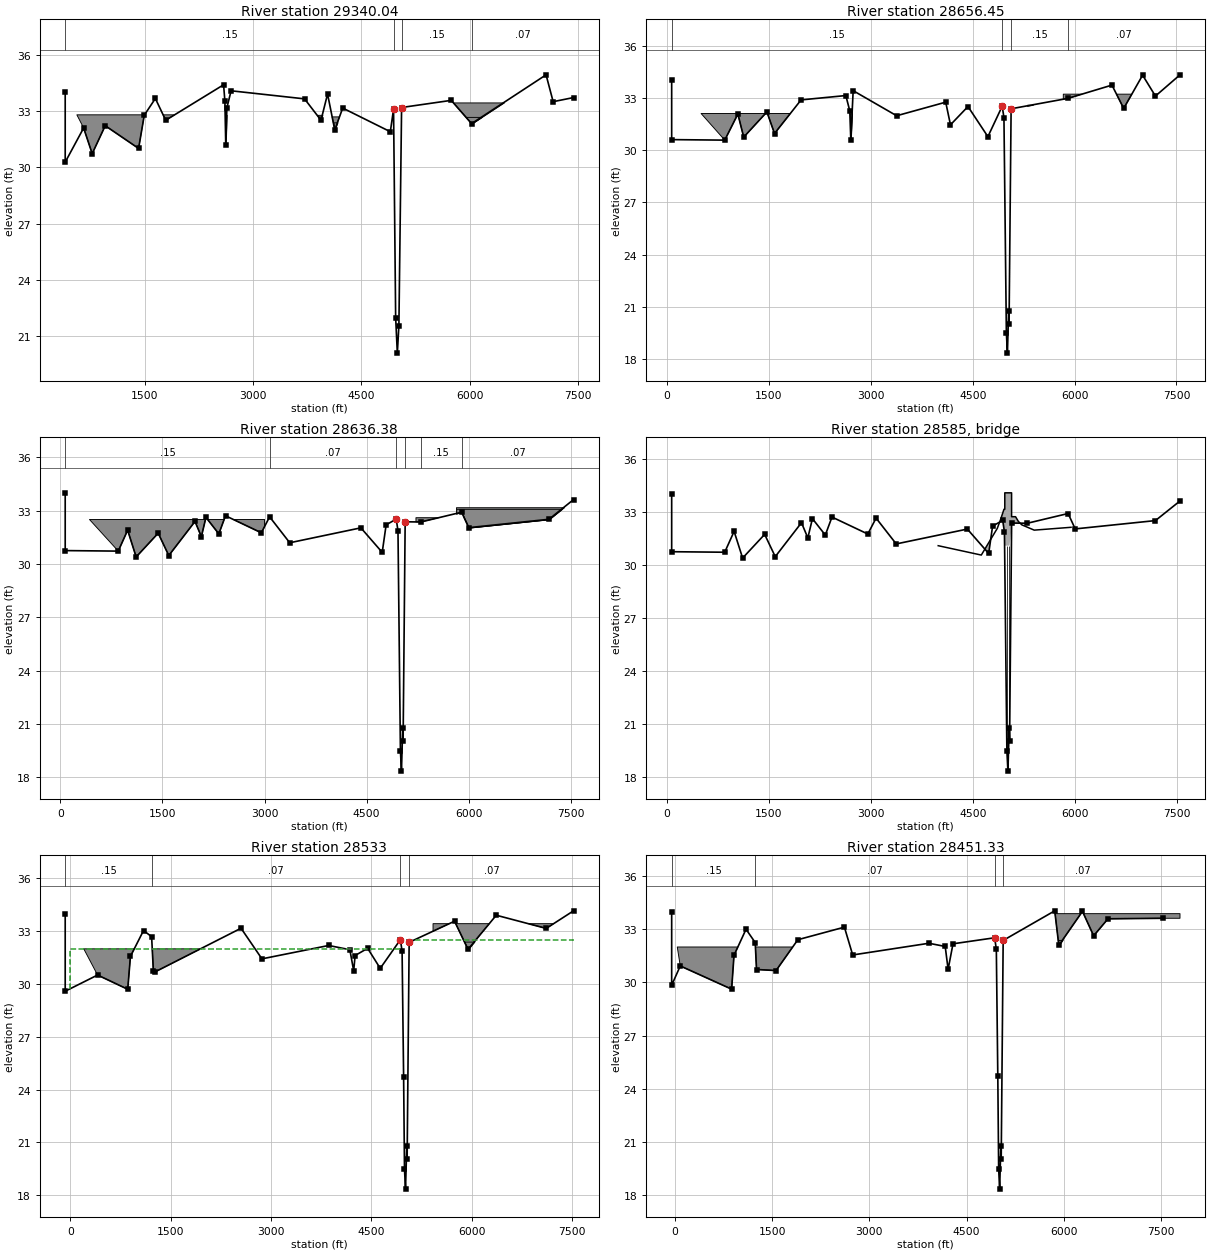
Type RM Length L Ch R = 1 ,29340.04,687.08,683.59,676.81
BEGIN DESCRIPTION:
 Pampa Street
END DESCRIPTION:
XS GIS Cut Line= 6
      3172170.21    13805825.867     3174387.907    13805917.353
     3175281.345    13805962.252     3176738.047    13806044.559
     3177723.561    13806084.183     3179196.693    13806097.305
#Sta/Elev= 30
  400.63      34  400.63   30.28  655.62    32.1   774.1   30.73  954.58   32.22
 1416.28   31.01 1494.71   32.78 1648.18   33.67 1791.42   32.51 2592.33    34.4
 2610.36   33.53 2622.37   31.18 2637.72   33.17 2696.18   34.08  3712.9   33.65
 3940.37   32.51 4031.16   33.91 4130.71      32 4240.76   33.16 4899.78    31.9
 4944.37    33.1 4973.46      22 4996.63   20.11 5018.33   21.58 5055.63   33.19
 5742.29   33.57 6024.11   32.33 7054.92   34.93 7153.03    33.5 7435.01   33.72
#Mann= 4 ,-1 , 0
  400.63     .15       0 4944.37     .03       0 5055.63     .15       0
 6024.11     .07       0
#Block Obstruct= 9 ,-1
 2520.27 2676.58    32.8 3344.71 4006.83    32.8 3351.54 4238.91   32.69
 4024.17 4220.01    32.4 5305.53 5659.41    33.1 5747.44 6716.72   33.46
 5774.74 6361.77   32.69 5856.66 6409.56    32.3   391.6    2300    32.8
Bank Sta=4944.37,5055.63
Exp/Cntr=0.3,0.1

Type RM Length L Ch R = 1 ,28656.45,20.15,20.07,20.05
BEGIN DESCRIPTION:
Vista Road
END DESCRIPTION:
XS GIS Cut Line= 6
      3171723.23    13806436.992      3175684.44    13806668.601
     3177674.967    13806757.611      3177932.75    13806628.532
     3178157.893    13806595.945     3179165.109    13806622.607
#Sta/Elev= 30
   67.94      34   67.94    30.6  849.58   30.57 1042.57   32.07 1128.47   30.74
 1470.06   32.19  1582.2   30.95 1973.02   32.88 2632.02   33.13 2690.25   32.25
 2705.28   30.59  2740.1   33.41 3380.51   31.97 4102.66   32.75  4172.7   31.45
 4430.46    32.5 4723.76   30.77 4934.47   32.52 4960.01   31.86 4995.73    19.5
 5011.08   18.34 5029.51   20.78 5035.28   20.03 5065.53   32.37 5903.86   32.97
 6550.18   33.73 6723.02   32.39  7001.6    34.3 7190.32    33.1 7552.09   34.32
#Mann= 4 ,-1 , 0
   67.94     .15       0 4934.47     .03       0 5065.53     .15       0
 5903.86     .07       0
#Block Obstruct= 6 ,-1
    5300    5550    32.6    2250    2820    32.1   55.94    2400    32.1
                         5334.02 7402.02    32.4  5833.9 7654.15   33.21
Bank Sta=4934.47,5065.53
Exp/Cntr=0.5,0.3

Type RM Length L Ch R = 1 ,28636.38,100.01,103.38,101.5
BEGIN DESCRIPTION:
Vista Road
END DESCRIPTION:
XS GIS Cut Line= 6
      3171723.23    13806476.748     3177626.991    13806776.045
     3177757.969    13806747.028     3177965.337    13806655.193
     3178187.517    13806622.607     3179156.222     13806664.08
#Sta/Elev= 30
   71.78      34   71.78   30.75  850.96   30.72  988.96    31.9 1113.87   30.39
 1437.71   31.73 1593.27   30.47 1978.49   32.39 2071.93   31.53 2139.21   32.62
 2328.58   31.69  2426.5   32.71 2952.86   31.75 3074.23   32.65 3370.17   31.19
 4414.94   32.03 4728.42   30.65 4785.95    32.2 4934.47   32.52 4960.01   31.86
 4995.73    19.5 5011.08   18.34 5029.51   20.78 5035.28   20.03 5065.53   32.37
  5296.9   32.36 5894.93   32.91 5999.64   32.04 7177.88   32.51 7538.78   33.62
#Mann= 6 ,-1 , 0
   71.78     .15       0 3074.23     .07       0 4934.47     .03       0
 5065.53     .07       0  5296.9     .15       0 5894.93     .07       0
#XS Ineff= 2 ,-1
                            3000    4954   30.75
Permanent Ineff=
       F       F
#Block Obstruct= 6 ,-1
   65.27    3000    32.5
 5224.12 7335.61    32.6 5811.77 7546.61   33.19  5815.7 7572.24    33.1
Bank Sta=4934.47,5065.53
Exp/Cntr=0.5,0.3

Type RM Length L Ch R = 3 ,28585   ,,,
BEGIN DESCRIPTION:
Bridge at Vista Road
END DESCRIPTION:
Bridge Culvert--1,0,-1,-1, 0
Deck Dist Width WeirC Skew NumUp NumDn MinLoCord MaxHiCord MaxSubmerge Is_Ogee
8,55,2.6,0, 14, 14, , , 0.95, 0, 0,0,,
    3987    4620    4855    4905    4953    4965    4965    5065    5065    5123
    5165    5215    5397    5938
   31.09   30.56   32.07   32.59   33.15   33.15   34.08   34.08   32.73   32.73
   32.46   32.27   31.97   32.13
       0       0       0       0       0       0   31.09   31.09       0       0
       0       0       0       0
    3987    4620    4855    4905    4953    4965    4965    5065    5065    5123
    5165    5215    5397    5938
   31.09   30.56   32.07   32.59   33.15   33.15   34.08   34.08   32.73   32.73
   32.46   32.27   31.97   32.13
       0       0       0       0       0       0   31.09   31.09       0       0
       0       0       0       0
Pier Skew, UpSta & Num, DnSta & Num=  ,5000, 2 ,5000, 2 , 0 , 0 , 0 ,,
     1.3     1.3
       0      32
     1.3     1.3
       0      32
Pier Skew, UpSta & Num, DnSta & Num=  ,5030, 2 ,5030, 2 , 0 , 0 , 0 ,,
     1.3     1.3
       0      32
     1.3     1.3
       0      32
BR Coef=-1 , 1 , 0 ,, 0 ,,,0.8,0,2,0,
WSPro=,,,, 1 ,,,, 0 ,,,, 0 ,,,,-1 ,-1 ,-1 , 0 , 0 , 0 , 0 , 0
BC Design=,, 0 ,, 0 ,,,,,,
BC HTab HWMax=34

Type RM Length L Ch R = 1 ,28533   ,80.41,81.67,81.39
BEGIN DESCRIPTION:
Vista Road
END DESCRIPTION:
XS GIS Cut Line= 6
      3171558.52     13806664.17     3174142.628    13806751.542
     3175678.452    13806788.452     3176576.521    13806836.103
     3177626.819    13806876.143     3179152.532    13806916.273
#Sta/Elev= 30
  -75.83      34  -75.83   29.59  407.86   30.51  858.93    29.7  899.29   31.57
 1094.98   33.04 1215.92   32.69 1241.79   30.76 1268.03   30.69 2552.41   33.17
 2864.93   31.43 3862.96   32.19 4178.92   31.95 4236.39   30.75    4258   31.62
 4444.91   32.03 4633.17   30.89 4934.47   32.52 4960.01   31.86  4982.8    24.7
 4995.73    19.5 5011.08   18.34 5029.51   20.78 5035.28   20.03 5065.53   32.37
 5743.91   33.57 5945.48   31.97 6367.75   33.91 7114.74   33.16 7522.72   34.16
#Mann= 4 ,-1 , 0
  -75.83     .15       0 1215.92     .07       0 4934.47     .03       0
 5065.53     .07       0
#XS Ineff= 2 , 0
       0    4954      32 5065.53       0    32.5
Permanent Ineff=
       F       F
#Block Obstruct= 5 ,-1
 -100.23    2000      32
 5422.52 7462.71   33.43 5838.45 6759.95   32.41
Bank Sta=4934.47,5065.53
Exp/Cntr=0.5,0.3

Type RM Length L Ch R = 1 ,28451.33,1193.42,1354.11,1558.75
BEGIN DESCRIPTION:
Vista Road
END DESCRIPTION:
XS GIS Cut Line= 6
       3171564.2    13806726.644     3174199.424    13806813.067
     3176572.952    13806916.029      3176937.49    13806924.574
     3177610.988      13806955.5     3179144.503     13806984.52
#Sta/Elev= 30
  -51.66      34  -51.66   29.84   80.85   30.93  873.98   29.62  910.55   31.53
 1096.13      33 1237.81   32.25 1258.21   30.73 1560.02   30.67 1895.71   32.41
 2614.74   33.12 2742.65   31.55 3919.41   32.21 4170.66   32.03  4215.7   30.74
 4291.13   32.18 4934.47   32.52 4960.01   31.86  4982.8    24.7 4995.73    19.5
 5011.08   18.34 5029.51   20.78 5035.28   20.03 5065.53   32.37 5861.41   34.04
  5924.8   32.09 6289.44   34.01  6462.4   32.63 6683.69   33.59 7533.41   33.62
#Mann= 4 ,-1 , 0
  -51.66     .15       0 1237.81     .07       0 4934.47     .03       0
 5065.53     .07       0
#Block Obstruct= 5 ,-1
  -76.92    2000      32
 5804.32 7795.22   33.88 5842.18 6115.27    32.4
Bank Sta=4934.47,5065.53
Exp/Cntr=0.3,0.1

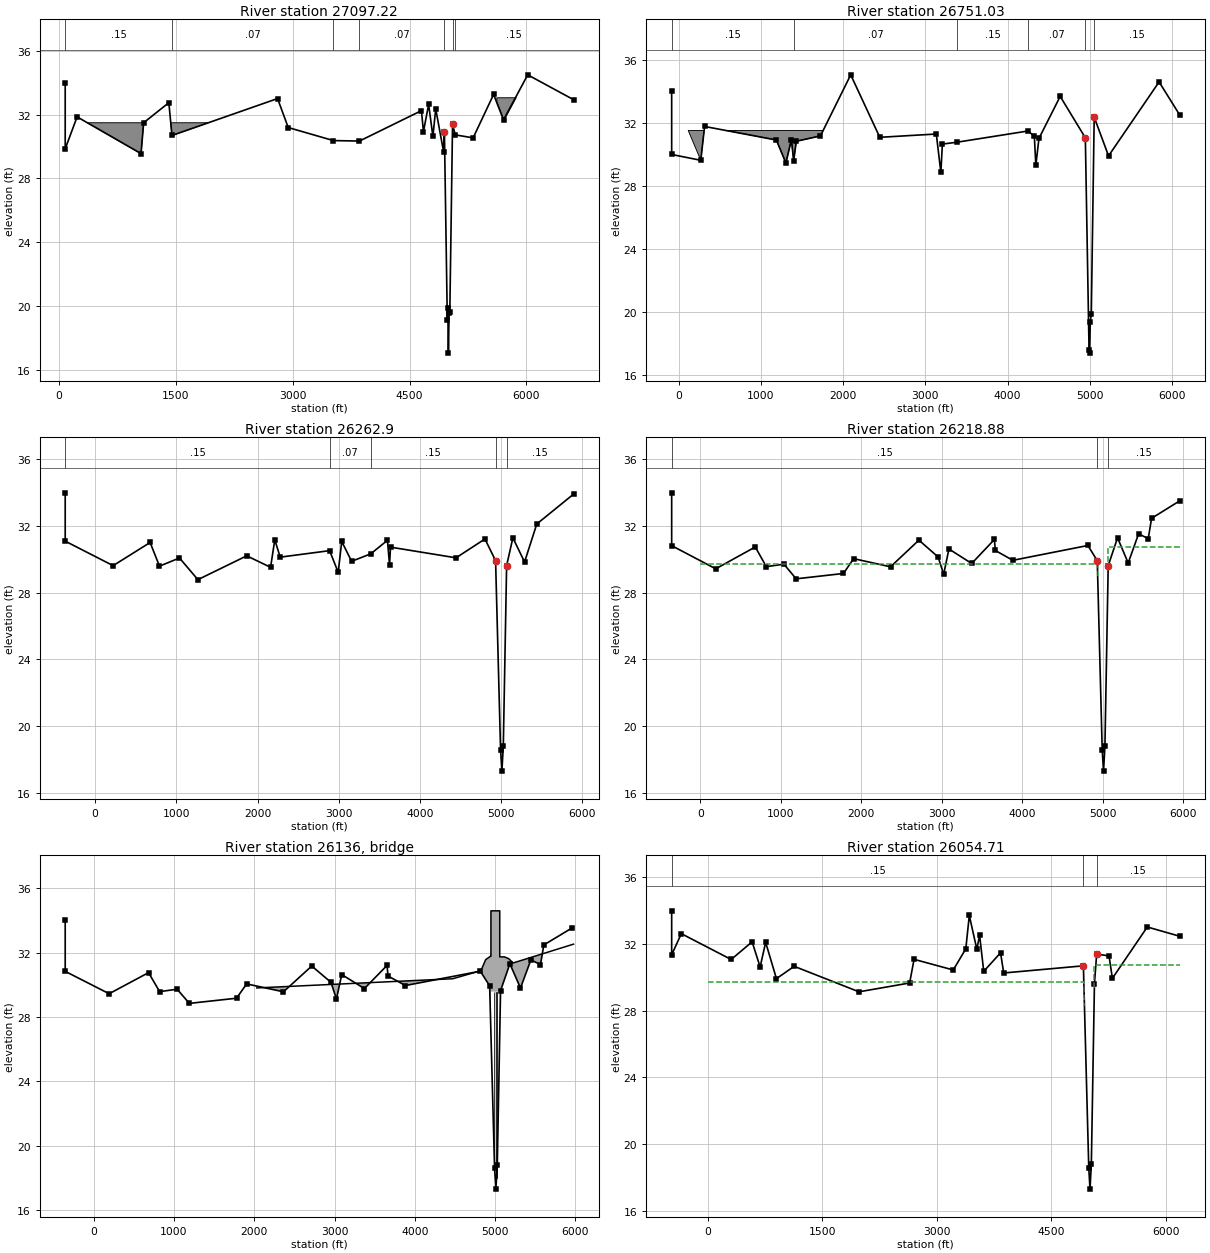
Type RM Length L Ch R = 1 ,27097.22,369.03,346.19,333.03
XS GIS Cut Line= 6
      3171513.09    13806777.759     3174220.406    13806864.265
     3174330.801    13806962.717     3175994.892    13808098.102
     3176284.253    13808284.116     3177385.203    13808998.471
#Sta/Elev= 30
   78.24      34   78.24   29.86  230.88   31.87 1052.11   29.56 1085.48    31.5
  1409.1   32.76 1449.02    30.7 2805.28   33.02 2941.75    31.2 3522.33   30.38
 3856.48   30.35 4652.75   32.26 4678.36   30.94 4745.28   32.65 4799.73   30.64
 4836.14   32.37  4937.4   29.67 4947.82   30.89 4984.93   19.09 4991.17   19.88
 4998.99   17.03 5007.51   19.54 5017.07   19.59 5052.18   31.41 5086.09   30.74
 5316.45   30.55  5579.6   33.28 5706.48   31.68 6017.75   34.51 6605.78   32.95
#Mann= 7 ,-1 , 0
   78.24     .15       0 1449.02     .07       0 3522.33     .15       0
 3856.48     .07       0 4947.82     .03       0 5052.18     .07       0
 5086.09     .15       0
#Block Obstruct= 3 ,-1
                         5614.33 5908.99    33.1    65.2    2500    31.5
Bank Sta=4947.82,5052.18
Exp/Cntr=0.3,0.1

Type RM Length L Ch R = 1 ,26751.03,651.88,488.14,262.52
XS GIS Cut Line= 6
      3171064.41    13807368.423     3173302.129    13807384.797
     3174216.281    13807396.309     3174358.397    13807498.493
     3175661.916     13808302.68     3176796.919     13808981.56
#Sta/Elev= 30
  -84.06      34  -84.06   29.98   269.9   29.61  316.06   31.76 1188.64    30.9
 1304.93   29.44 1371.89   30.92 1399.43   29.58  1431.5   30.82 1724.94   31.16
 2093.13   35.04  2446.7   31.07 3133.82   31.28 3189.24   28.84 3207.72   30.64
 3386.56   30.76 4246.41   31.47 4325.77   31.15 4344.21   29.29 4381.92      31
 4640.27   33.67 4946.08   31.04 4991.14   17.59 4998.08   17.36  5006.2   19.35
 5018.44   19.84 5053.92   32.35 5228.33   29.89 5842.89   34.59 6097.16   32.46
#Mann= 6 ,-1 , 0
  -84.06     .15       0 1399.43     .07       0 3386.56     .15       0
 4246.41     .07       0 4946.08     .03       0 5053.92     .15       0
#Block Obstruct= 1 ,-1
    -100    2000    31.5
Bank Sta=4946.08,5053.92
Exp/Cntr=0.3,0.1

Type RM Length L Ch R = 1 ,26262.9 ,42.84,44.01,43.48
BEGIN DESCRIPTION:
Spencer Hwy
END DESCRIPTION:
XS GIS Cut Line= 6
      3170223.03    13808564.562     3172650.358    13808698.022
     3175410.372    13808825.417     3175492.962    13808825.864
     3175652.533    13808839.046     3176476.384    13808878.276
#Sta/Elev= 30
 -369.18      34 -369.18    31.1  220.95   29.63  676.63   31.02  792.18    29.6
 1038.57   30.09 1265.14   28.79 1867.03   30.22 2160.43   29.53 2212.32   31.18
 2279.07   30.14 2887.76   30.53 2993.35   29.23 3036.92   31.08 3158.97   29.89
 3394.86   30.34 3599.97   31.15 3625.66   29.69  3638.2   30.74 4444.95    30.1
 4800.97   31.23 4932.01   29.93 4993.35   18.59 5009.75    17.3 5027.17   18.79
 5067.99   29.63    5145    31.3 5289.16   29.85 5439.59   32.13 5892.26   33.92
#Mann= 5 ,-1 , 0
 -369.18     .15       0 2887.76     .07       0 3394.86     .15       0
 4932.01     .03       0 5067.99     .15       0
Bank Sta=4932.01,5067.99
Exp/Cntr=0.5,0.3

Type RM Length L Ch R = 1 ,26218.88,150.59,164.18,160.49
BEGIN DESCRIPTION:
Spencer Hwy
END DESCRIPTION:
XS GIS Cut Line= 6
      3170212.54    13808599.536     3172686.578    13808739.737
     3175409.341    13808865.412     3175490.426    13808865.851
     3175629.769    13808875.172     3176519.122    13808921.014
#Sta/Elev= 30
 -355.08      34 -355.08   30.83  192.26   29.44  683.17   30.75  821.11   29.57
 1038.91   29.72 1191.49   28.84 1778.75   29.16 1905.25   30.05 2363.88   29.56
 2716.16   31.16 2955.06   30.15 3023.86   29.11 3089.34   30.63 3371.96   29.76
 3654.16    31.2 3665.84   30.54 3883.34   29.95 4815.43   30.84 4932.01   29.93
 4993.35   18.59 5009.75    17.3 5027.17   18.79 5067.99   29.63    5184    31.3
 5316.22   29.79 5445.66   31.54 5565.48   31.25  5606.7   32.47 5959.87   33.53
#Mann= 3 ,-1 , 0
 -355.08     .15       0 4932.01     .03       0 5067.99     .15       0
#XS Ineff= 2 , 0
       0    4937    29.7    5067       0   30.75
Permanent Ineff=
       F       F
Bank Sta=4932.01,5067.99
Exp/Cntr=0.5,0.3

Type RM Length L Ch R = 3 ,26136   ,,,
BEGIN DESCRIPTION:
Bridge at Spencer Hwy
END DESCRIPTION:
Bridge Culvert--1,0,-1,-1, 0
Deck Dist Width WeirC Skew NumUp NumDn MinLoCord MaxHiCord MaxSubmerge Is_Ogee
10,100,2.6,0, 13, 14, , , 0.95, 0, 0,0,,
    2031    4472    4823    4883    4943    4948    4948    5058    5058    5115
    5169    5224    5977
    29.8   30.37   30.87   31.56   31.77   31.77   34.59   34.59   31.73   31.73
   31.62   31.35   32.52
       0       0       0       0       0       0   29.57   29.57       0       0
       0       0       0
    1950    2031    4472    4823    4883    4943    4948    4948    5058    5058
    5115    5169    5224    5977
   29.65    29.8   30.37   30.87   31.56   31.77   31.77   34.59   34.59   31.73
   31.73   31.62   31.35   32.52
       0       0       0       0       0       0       0   29.57   29.57       0
       0       0       0       0
Pier Skew, UpSta & Num, DnSta & Num=  ,4988, 2 ,4988, 2 , 0 , 0 , 0 ,,
     1.5     1.5
       0      30
     1.5     1.5
       0      30
Pier Skew, UpSta & Num, DnSta & Num=  ,5018, 2 ,5018, 2 , 0 , 0 , 0 ,,
     1.5     1.5
       0      30
     1.5     1.5
       0      30
BR Coef=-1 , 1 , 0 ,, 0 ,,,0.8,0,2,0,
WSPro=,,,, 1 ,,,, 0 ,,,, 0 ,,,,-1 ,-1 ,-1 , 0 , 0 , 0 , 0 , 0
BC Design=,, 0 ,, 0 ,,,,,,
BC HTab HWMax=34

Type RM Length L Ch R = 1 ,26054.71,177.5,189.75,183.6
BEGIN DESCRIPTION:
Spencer Hwy
END DESCRIPTION:
XS GIS Cut Line= 6
      3170006.19    13808865.345     3170719.676    13808879.321
     3172662.838     13808878.79     3175405.733    13809005.395
     3175614.633    13809022.022     3176667.735    13809068.777
#Sta/Elev= 30
 -476.37      34 -476.37   31.36 -349.99   32.63  303.78   31.08  578.53   32.14
  683.71   30.63  755.98   32.11   897.6   29.93 1130.07   30.67 1980.38   29.14
 2644.27   29.67 2702.34   31.09 3216.27   30.45 3380.83   31.72 3426.87   33.72
 3525.62   31.69 3561.64   32.54 3616.09   30.37 3836.73   31.48 3878.02   30.27
    4923    30.7 4993.35   18.59 5009.75    17.3 5027.17   18.79 5067.99   29.63
    5097    31.4    5259    31.3 5303.21   29.95 5761.06   33.03 6189.94   32.47
#Mann= 3 ,-1 , 0
 -476.37     .15       0    4923     .03       0    5097     .15       0
#XS Ineff= 2 , 0
       0    4937    29.7    5067       0   30.75
Permanent Ineff=
       F       F
Bank Sta=4923,5097
Exp/Cntr=0.5,0.3

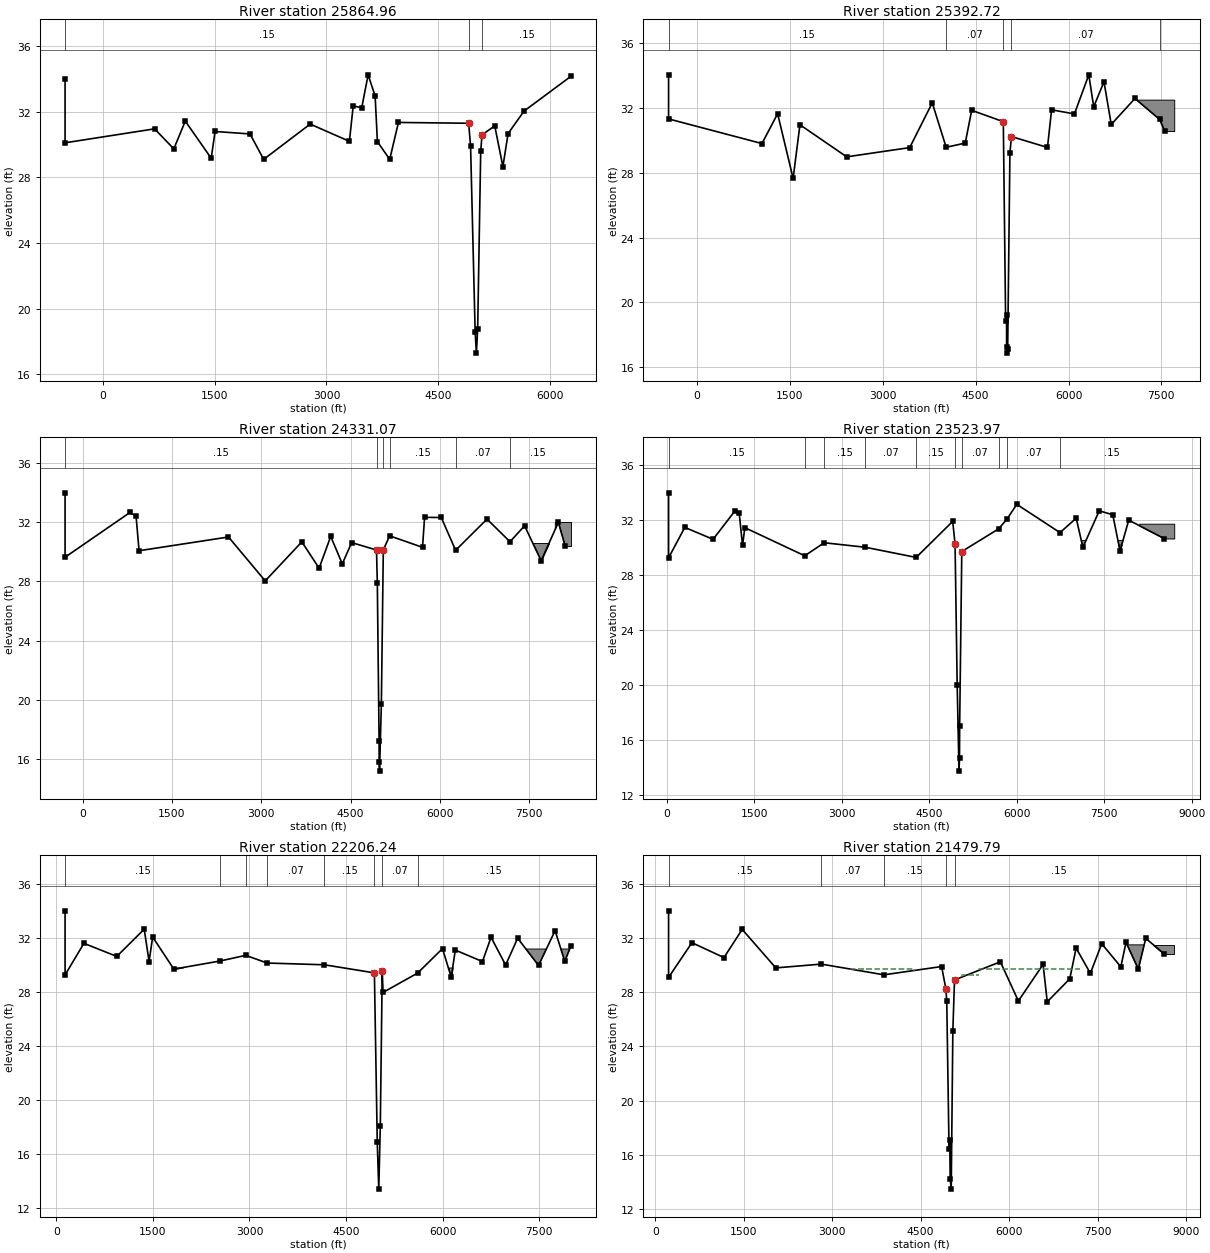
Type RM Length L Ch R = 1 ,25864.96,344.09,472.24,702.16
BEGIN DESCRIPTION:
Spencer Hwy
END DESCRIPTION:
XS GIS Cut Line= 6
      3169887.27    13809026.229     3170719.685    13809035.079
     3172639.279    13809037.873     3175471.406    13809165.752
     3175602.319    13809181.705     3176660.379    13809228.607
#Sta/Elev= 30
 -503.83      34 -503.83   30.11  695.88   30.96  953.87   29.74 1107.59   31.43
    1455   29.17 1506.97    30.8 1975.06   30.65 2158.44    29.1 2781.94   31.25
  3307.5    30.2 3358.66   32.36 3472.66   32.24 3558.64   34.25 3652.44   32.96
 3682.88   30.18 3848.06    29.1  3965.1   31.35    4906    31.3 4932.01   29.93
 4993.35   18.59 5009.75    17.3 5027.17   18.79 5067.99   29.63    5086    30.6
 5256.16   31.14 5365.36   28.66 5434.66   30.67 5648.12   32.04 6274.28   34.15
#Mann= 3 ,-1 , 0
 -503.83     .15       0    4906     .03       0    5086     .15       0
#Block Obstruct= 2 ,-1
                            5660    5780    31.8
Bank Sta=4906,5086
Exp/Cntr=0.3,0.1

Type RM Length L Ch R = 1 ,25392.72,1026.93,1061.65,1055.31
XS GIS Cut Line= 6
      3169743.88    13809250.068       3172662.2    13809264.379
      3174761.59    13809358.211      3175354.73    13809676.759
     3176004.099    13810143.597     3177261.612    13810996.233
#Sta/Elev= 30
  -460.4      34  -460.4   31.32 1047.85    29.8 1300.98   31.64  1551.5   27.65
 1661.43   30.96 2416.92   28.98 3434.52   29.55 3798.68   32.31  4023.5   29.57
 4331.94   29.83 4435.62   31.85 4946.61   31.15 4984.03   18.88 4999.02   19.25
 5000.17   17.25 5010.51   16.87 5017.37   17.15 5053.39   29.24 5078.71   30.23
 5660.02   29.56 5726.58   31.88 6095.68   31.63 6327.72   34.04 6406.73   32.07
 6572.97   33.61 6690.18   30.98 7073.17   32.58  7471.8   31.29 7551.92   30.57
#Mann= 5 ,-1 , 0
  -460.4     .15       0  4023.5     .07       0 4946.61     .03       0
 5078.71     .07       0  7471.8     .15       0
#XS Ineff= 1 ,-1
    6520    6950    31.8
Permanent Ineff=
       F
#Block Obstruct= 1 ,-1
 7085.69 7707.44   32.51
Bank Sta=4946.61,5078.71
Exp/Cntr=0.3,0.1

Type RM Length L Ch R = 1 ,24331.07,791.85,807.11,745.07
XS GIS Cut Line= 6
       3169519.6    13809555.014     3170684.006    13809536.741
     3172562.764    13809567.992     3173231.521    13809612.056
     3175923.173    13811288.612     3177235.714    13812045.116
#Sta/Elev= 30
 -296.39      34 -296.39   29.64  794.15   32.67  896.52   32.42  947.04   30.08
 2449.45   31.01 3066.47   28.04 3682.16   30.68 3972.37    28.9 4167.46   31.05
 4361.62   29.19 4518.97   30.63  4936.7   30.13 4950.52   27.87 4980.26   17.18
  4980.8    15.8 4987.52   15.16 5018.46   19.72    5051   30.13 5156.54   31.09
  5709.8   30.31 5744.66   32.34  6024.7   32.33 6266.23   30.11 6793.54   32.22
 7179.88   30.69 7425.18   31.77 7702.76    29.4 7992.48      32 8103.91   30.42
#Mann= 6 ,-1 , 0
 -296.39     .15       0  4936.7     .03       0    5051     .07       0
 5156.54     .15       0 6266.23     .07       0 7179.88     .15       0
#XS Ineff= 2 ,-1
    -800     700    31.5    6000    7950    31.5
Permanent Ineff=
       F       F
#Block Obstruct= 3 ,-1
    -500     100    30.5    6800    7900    30.6    7941    8200      32
Bank Sta=4936.7,5051
Exp/Cntr=0.3,0.1

Type RM Length L Ch R = 1 ,23523.97,1109.03,1317.73,1544.23
XS GIS Cut Line= 6
      3169485.52    13809628.847     3170672.772    13809612.095
      3171550.99    13809651.177     3172531.727     13810125.54
     3174227.425     13811130.37     3177183.917    13812744.371
#Sta/Elev= 30
   30.19      34   30.19   29.26  308.38   31.48  793.11   30.61 1166.31   32.67
  1240.6   32.54 1298.17   30.17 1337.77   31.46 2364.17   29.41 2699.23   30.36
 3405.58   30.03 4275.26   29.29 4902.01   31.92 4942.28   30.26 4978.58      20
 5009.94   13.71 5018.36   14.69 5020.95   16.98 5057.72   29.72  5688.5   31.37
 5833.45   32.09 6000.73   33.16 6741.56    31.1 7019.64   32.15 7133.97   30.02
 7414.47   32.69 7646.56    32.4 7770.63   29.77 7920.28   32.01 8525.59   30.67
#Mann= 10 ,-1 , 0
   30.19     .15       0 2364.17     .07       0 2699.23     .15       0
 3405.58     .07       0 4275.26     .15       0 4942.28     .03       0
 5057.72     .07       0  5688.5     .15       0 5833.45     .07       0
 6741.56     .15       0
#XS Ineff= 2 ,-1
       0    1100    31.2    6900    8000    31.3
Permanent Ineff=
       F       F
#Block Obstruct= 5 ,-1
       0     300    30.1 7013.87 7936.42   30.53 7016.43 7308.57   30.23
 7618.23 7885.95   30.23    8100    8700   31.75
Bank Sta=4942.28,5057.72
Exp/Cntr=0.3,0.1

Type RM Length L Ch R = 1 ,22206.24,558.51,726.45,965.61
XS GIS Cut Line= 6
      3169445.76    13809674.283      3170695.28    13809662.828
     3172356.662    13810191.591     3173209.855      13812044.7
     3173611.417    13812665.258     3175062.471    13814150.374
#Sta/Elev= 30
  137.76      34  137.76   29.25  430.55   31.59  940.39   30.62 1366.38   32.64
 1441.38   30.24 1497.35   32.06  1825.7   29.68 2543.46   30.28 2941.81    30.7
 3273.78   30.13 4162.88      30 4939.12    29.4  4983.7   16.83 5007.13   13.37
 5030.86   18.04 5060.88   29.55 5073.44   27.95 5611.14   29.39  5996.5    31.2
 6131.98   29.07 6194.74   31.09  6616.7   30.24 6749.84   32.04 6976.52   29.98
 7163.12   31.97  7486.9   29.95 7743.86   32.53 7894.68   30.26 7986.42   31.36
#Mann= 8 ,-1 , 0
  137.76     .15       0 2543.46     .07       0 2941.81     .15       0
 3273.78     .07       0 4162.88     .15       0 4939.12     .03       0
 5060.88     .07       0 5611.14     .15       0
#XS Ineff= 1 ,-1
       0     500    30.6
Permanent Ineff=
       F
#Block Obstruct= 3 ,-1
       0    2500    29.8    6040    6250    29.8    7150    8000   31.17
Bank Sta=4939.12,5060.88
Exp/Cntr=0.3,0.1

Type RM Length L Ch R = 1 ,21479.79,21.23,20,24.84
BEGIN DESCRIPTION:
Shaver Street
END DESCRIPTION:
XS GIS Cut Line= 6
      3169366.25    13809770.834     3170718.188    13809794.905
     3172534.248     13810865.81     3172472.973     13812110.16
     3172471.219     13812905.79     3174973.909    13814361.561
#Sta/Elev= 30
  225.66      34  225.66   29.09  621.87   31.65 1164.61   30.55 1473.83   32.63
 2043.99   29.79 2814.55   30.07 3877.17   29.28 4854.84   29.89 4926.29   28.27
 4942.24   27.34 4981.11    16.4 4993.46   17.08  5000.3   14.23 5017.89   13.47
 5045.61   25.16 5073.71    28.9  5851.4   30.24  6156.5   27.35 6575.68   30.05
 6645.94   27.29  7027.5   28.98  7135.8   31.25 7377.38   29.39  7569.6   31.57
 7893.92   29.87 7981.92   31.67 8190.16    29.7 8316.38   31.97 8623.79   30.84
#Mann= 5 ,-1 , 0
  225.66     .15       0 2814.55     .07       0 3877.17     .15       0
 4926.29     .03       0 5073.71     .15       0
#XS Ineff= 4 ,-1
       0     700    30.5 5193.42 5486.96   29.26    3300    4380    29.7
    5488    7200    29.7
Permanent Ineff=
       F       F       F       F
#Block Obstruct= 5 ,-1
                                                    8000    8799   31.49
     150     450    29.6    7200    7400    29.6
Bank Sta=4926.29,5073.71
Exp/Cntr=0.5,0.3

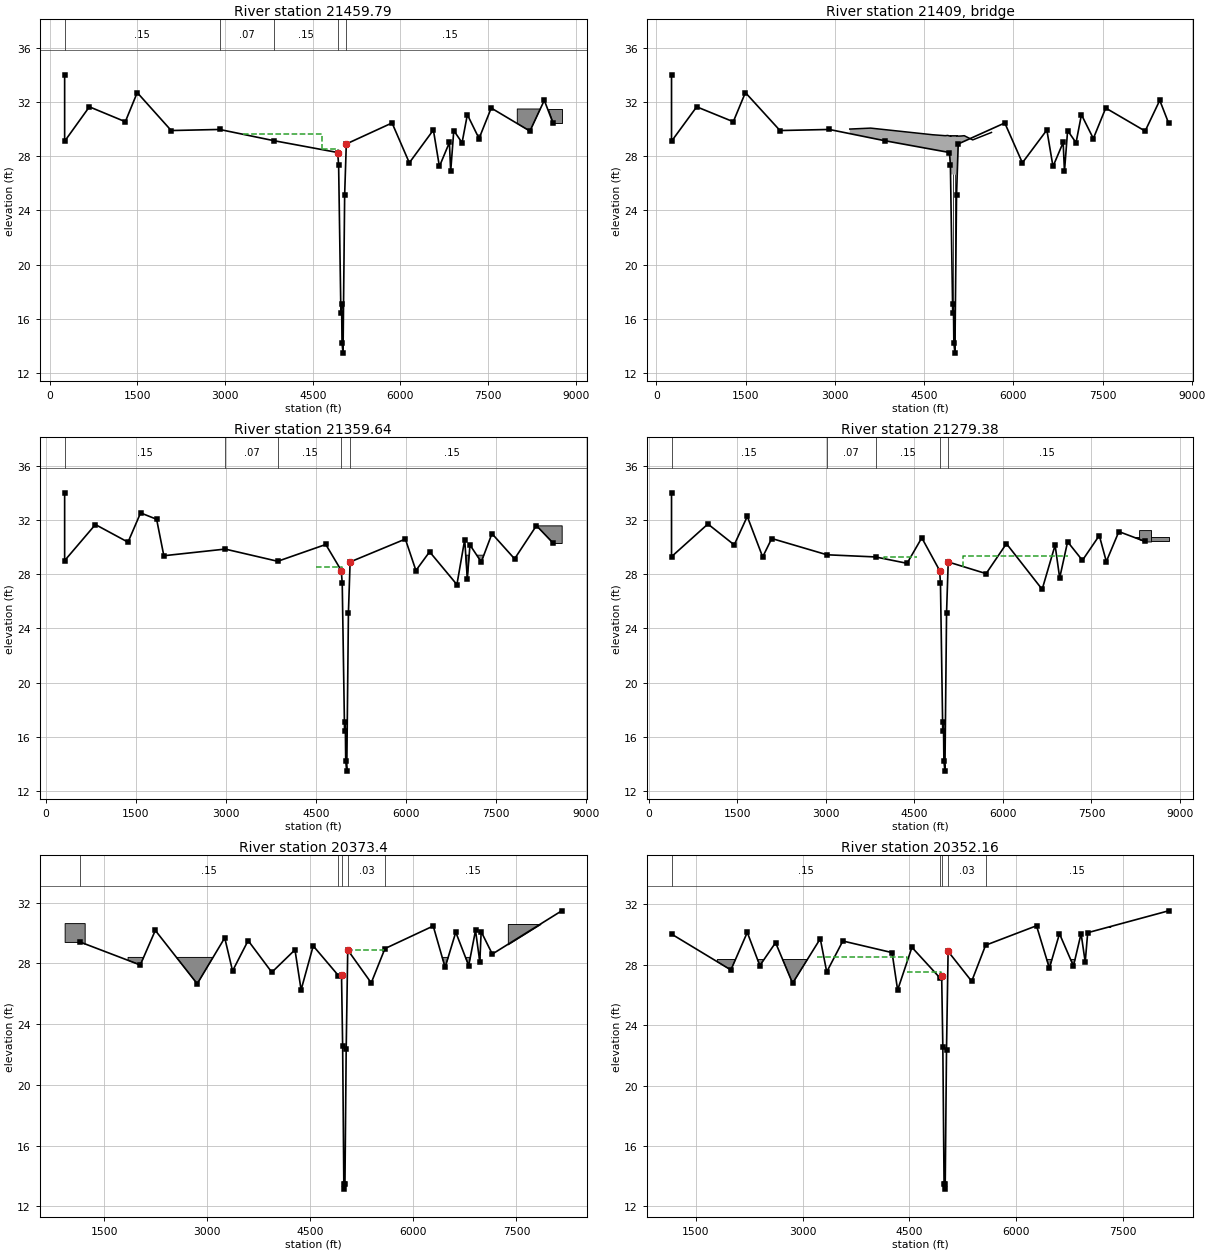
Type RM Length L Ch R = 1 ,21459.79,106.15,100.15,124.19
BEGIN DESCRIPTION:
Shaver Street
END DESCRIPTION:
XS GIS Cut Line= 6
      3169354.89    13809799.231     3170700.184    13809830.486
     3172513.354    13810882.935     3172452.942    13812110.799
     3172450.837    13812918.571     3174939.847    13814361.561
#Sta/Elev= 30
  253.11      34  253.11    29.1  676.32   31.64 1291.69   30.54 1495.27   32.69
 2077.07   29.89 2905.04   29.97 3836.42   29.14 4926.29   28.27 4942.24   27.34
 4981.11    16.4 4993.46   17.08  5000.3   14.23 5017.89   13.47 5045.61   25.16
 5073.71    28.9 5856.64   30.45 6152.31   27.51  6564.1   29.93 6667.17   27.24
 6838.26   29.01 6860.21   26.87 6913.09   29.89 7054.95   28.99 7145.57   31.06
 7345.55    29.3 7554.03   31.55 8216.63   29.85  8462.5   32.12 8610.33   30.45
#Mann= 5 ,-1 , 0
  253.11     .15       0 2905.04     .07       0 3836.42     .15       0
 4926.29     .03       0 5073.71     .15       0
#XS Ineff= 4 ,-1
       0     770    30.5    4667    4932    28.5    3300 4665.23    29.6
    5485    7200    29.6
Permanent Ineff=
       F       F       F       F
#Block Obstruct= 5 ,-1
     150     450    29.6
    7270    7430    29.6    8000  8759.8   31.48
Bank Sta=4926.29,5073.71
Exp/Cntr=0.5,0.3

Type RM Length L Ch R = 3 ,21409   ,,,
BEGIN DESCRIPTION:
Bridge at Shaver Street
END DESCRIPTION:
Bridge Culvert--1,0,-1,-1, 0
Deck Dist Width WeirC Skew NumUp NumDn MinLoCord MaxHiCord MaxSubmerge Is_Ogee
15,50,2.6,0, 18, 18, , , 0.95, 0, 0,0,,
    3250    3602    4644    4857    4896    4947    4947    4958    4999    5040
    5046    5052    5052    5089    5131    5175    5317    5633
      30   30.07   29.58   29.51   29.53   29.47    29.5    29.5    29.5    29.5
    29.5    29.5   29.48   29.48   29.49   29.51    29.2   29.75
       0       0       0       0       0       0   26.65   26.65   26.65   26.65
   26.65   26.65       0       0       0       0       0       0
    3250    3602    4644    4857    4896    4947    4947    4958    4999    5040
    5046    5052    5052    5089    5131    5175    5317    5633
      30   30.07   29.58   29.51   29.53   29.47    29.5    29.5    29.5    29.5
    29.5    29.5   29.48   29.48   29.49   29.51    29.2   29.75
       0       0       0       0       0       0   26.65   26.65   26.65   26.65
   26.65   26.65       0       0       0       0       0       0
Pier Skew, UpSta & Num, DnSta & Num=  ,4985, 4 ,4985, 4 , 3 , 3 , 0 ,,
     1.5     1.5       2       2
       0   24.65   24.65      27
     1.5     1.5       2       2
       0   24.65   24.65      27
Pier Skew, UpSta & Num, DnSta & Num=  ,5015, 4 ,5015, 4 , 3 , 3 , 0 ,,
     1.5     1.5       2       2
       0   24.65   24.65      27
     1.5     1.5       2       2
       0   24.65   24.65      27
BR Coef=-1 , 1 , 0 ,, 0 ,,,0.8,0,2,0,
WSPro=,,,, 1 ,,,, 0 ,,,, 0 ,,,,-1 ,-1 ,-1 , 0 , 0 , 0 , 0 , 0
BC Design=,, 0 ,, 0 ,,,,,,
BC HTab HWMax=34

Type RM Length L Ch R = 1 ,21359.64,88.84,80.25,115.86
BEGIN DESCRIPTION:
Shaver Street
END DESCRIPTION:
XS GIS Cut Line= 6
      3169332.17    13809833.308     3170677.907    13809862.233
     3172414.383    13810860.101     3172352.785    13812113.995
     3172348.925    13812982.474     3174646.911    13814334.311
#Sta/Elev= 30
  315.57      34  315.57      29   828.2   31.66 1371.81   30.36 1581.33   32.52
 1848.53   32.05 1968.95   29.36 2991.69   29.85 3866.84   28.95 4668.19   30.19
 4926.29   28.27 4942.24   27.34 4981.11    16.4 4993.46   17.08  5000.3   14.23
 5017.89   13.47 5045.61   25.16 5073.71    28.9 5994.46   30.59 6170.48   28.27
 6398.84   29.65 6853.82   27.23 6983.82   30.55 7026.94   27.67 7071.77   30.15
  7259.7    28.9 7438.03   30.99 7815.18   29.13 8179.26   31.58 8455.34    30.3
#Mann= 5 ,-1 , 0
  315.57     .15       0 2991.69     .07       0 3866.84     .15       0
 4926.29     .03       0 5073.71     .15       0
#XS Ineff= 4 ,-1
       0     850    30.5    4500    4932    28.5    5350    6940    29.1
    3400    4490    29.2
Permanent Ineff=
       F       F       F       F
#Block Obstruct= 2 ,-1
    8200    8600    31.6    7005    7350    29.4
Bank Sta=4926.29,5073.71
Exp/Cntr=0.5,0.3

Type RM Length L Ch R = 1 ,21279.38,1149.23,905.99,405.3
BEGIN DESCRIPTION:
Shaver Street
END DESCRIPTION:
XS GIS Cut Line= 6
      3169320.82    13809867.384      3170635.33    13809896.981
     3172333.995    13810865.732     3172272.659    13812116.553
     3172267.395    13813033.597     3174497.037    13814334.311
#Sta/Elev= 30
  387.36      34  387.36   29.29 1003.72    31.7 1449.55   30.16 1670.47   32.26
 1931.42   29.27 2084.65   30.63 3020.05   29.43 3842.15   29.27 4376.49    28.8
 4626.12   30.68    4928   28.27 4942.24   27.34 4981.11    16.4 4993.46   17.08
  5000.3   14.23 5017.89   13.47 5045.61   25.16 5073.71    28.9 5715.43   28.04
 6059.69   30.25 6664.75   26.88 6883.83   30.14 6961.54   27.72 7095.67   30.39
 7346.55   29.02 7632.58   30.85 7751.65   28.93  7963.7   31.14 8409.35   30.41
#Mann= 5 ,-1 , 0
  387.36     .15       0 3020.05     .07       0 3842.15     .15       0
    4928     .03       0 5073.71     .15       0
#XS Ineff= 3 ,-1
       0     900    30.5 5330.33    7110   29.31    3980    4550    29.3
Permanent Ineff=
       F       F       F
#Block Obstruct= 3 ,-1
                            8000 8805.46   30.71 8306.45 8509.03   31.25
Bank Sta=4928,5073.71
Exp/Cntr=0.3,0.1

Type RM Length L Ch R = 1 ,20373.4 ,20.01,21.24,20.22
XS GIS Cut Line= 6
      3169088.78    13810206.573     3169974.071    13811346.956
     3171632.237    13812811.257     3172012.864    13813123.829
     3173211.659    13813966.637     3174503.849    13814490.997
#Sta/Elev= 30
 1148.83   29.42 2027.36    27.9 2246.04   30.18 2855.66   26.66 3255.84   29.69
  3369.8   27.51 3596.42   29.51 3940.76   27.42 4277.74    28.9 4366.88   26.26
 4543.06   29.16 4910.36    27.2 4954.74   27.25  4971.2   22.55  4988.4   13.44
 4996.76   13.13 5004.69   13.45 5022.75   22.38 5045.26   28.89    5387   26.72
 5586.24   28.98 6288.62   30.47 6461.72   27.74 6616.72   30.06 6804.84   27.86
 6904.14   30.18 6966.72    28.1 6986.16    30.1 7148.18   28.62 8157.33   31.47
#Mann= 5 ,-1 , 0
 1148.83     .15       0 4910.36     .03       0 4954.74    .019       0
 5045.26     .03       0 5586.24     .15       0
#XS Ineff= 2 ,-1
 5088.11  5578.1   28.86    3200    4550    28.5
Permanent Ineff=
       F       F
#Block Obstruct= 4 ,-1
  927.19 1218.43   30.66    1850    3100    28.4    6200    7200    28.4
 7374.11 8248.57    30.6
Bank Sta=4954.74,5045.26
Exp/Cntr=0.5,0.3

Type RM Length L Ch R = 1 ,20352.16,90.77,95.56,91.01
XS GIS Cut Line= 6
      3169052.31    13810258.052     3169949.991    13811352.373
     3171619.496    13812826.688     3172000.618    13813139.668
       3173202.4    13813984.576     3174476.599     13814525.06
#Sta/Elev= 30
 1155.93   30.04 1990.91   27.66 2221.17   30.15 2397.63   27.95 2619.22   29.47
 2858.47   26.78 3247.71   29.73 3338.35   27.53 3564.96   29.58 4257.34   28.81
 4335.43   26.33 4536.51   29.16 4927.24   27.15 4954.74   27.25  4971.2   22.55
  4988.4   13.44 4996.76   13.13 5004.69   13.45 5022.75   22.38 5045.26   28.89
 5376.93   26.91  5572.5    29.3 6288.52   30.59 6469.19   27.78 6611.36   30.06
 6807.81   27.92 6915.26   30.07 6973.33   28.18 7008.02   30.13 8145.15   31.58
#Mann= 5 ,-1 , 0
 1155.93     .15       0 4927.24     .03       0 4954.74    .019       0
 5045.26     .03       0  5572.5     .15       0
#XS Ineff= 4 ,-1
    4462    4942    27.5 3195.94 4460.38    28.5    5050    5065    26.9
 5066.79 5582.77   28.59
Permanent Ineff=
       F       F       F       F
#Block Obstruct= 3 ,-1
    1800    3100   28.35    6200    7100   28.35    7306 8234.58   30.54
Bank Sta=4954.74,5045.26
Exp/Cntr=0.5,0.3

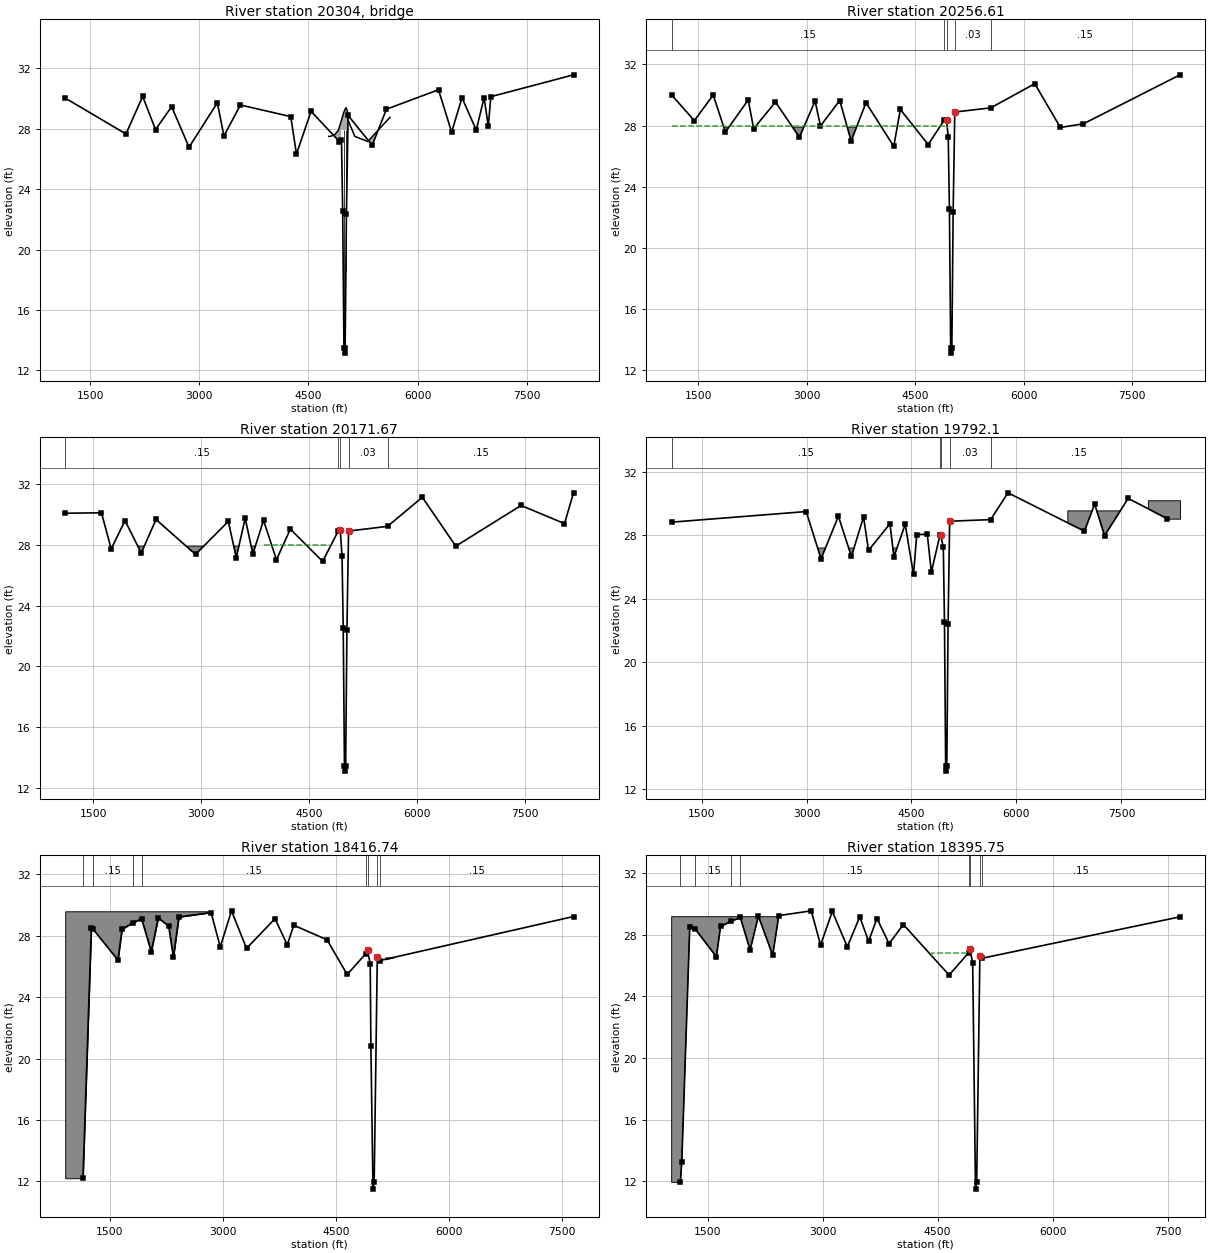
Type RM Length L Ch R = 3 ,20304   ,,,
BEGIN DESCRIPTION:
Bridge at Queens Road
END DESCRIPTION:
Bridge Culvert--1,0,-1,-1, 0
Deck Dist Width WeirC Skew NumUp NumDn MinLoCord MaxHiCord MaxSubmerge Is_Ogee
8,50,2.6,0, 16, 15, , , 0.95, 0, 0,0,,
    4780    4803    4859    4911    4950    4950    4987    5004    5016    5034
    5050    5050    5086    5138    5316    5621
    27.5    27.5    27.6    27.9    28.5    28.5    29.1    29.3    29.4    29.2
    28.5    28.5    28.1    27.5   27.16   28.76
       0       0       0       0       0   27.93   27.93   27.93   27.93   27.93
   27.93       0       0       0       0       0
    4803    4859    4911    4950    4950    4987    5004    5016    5034    5050
    5050    5086    5138    5316    5621
    27.5    27.6    27.9    28.5    28.5    29.1    29.3    29.4    29.2    28.5
    28.5    28.1    27.5   27.16   28.76
       0       0       0       0   27.93   27.93   27.93   27.93   27.93   27.93
       0       0       0       0       0
Pier Skew, UpSta & Num, DnSta & Num=  ,4985, 2 ,4985, 2 , 0 , 0 , 0 ,,
       2       2
       0      28
       2       2
       0      28
Pier Skew, UpSta & Num, DnSta & Num=  ,5015, 2 ,5015, 2 , 0 , 0 , 0 ,,
       2       2
       0      28
       2       2
       0      28
BR Coef=-1 , 1 , 0 ,, 0 ,,,0.8,-1,2,0,
WSPro=,,,, 1 ,,,, 0 ,,,, 0 ,,,,-1 ,-1 ,-1 , 0 , 0 , 0 , 0 , 0
BC Design=,, 0 ,, 0 ,,,,,,
BC HTab HWMax=31.58

Type RM Length L Ch R = 1 ,20256.61,81.16,84.94,80.9
XS GIS Cut Line= 6
      3169007.27    13810324.545     3169888.372    13811418.028
     3171562.162    13812896.126      3171945.51    13813210.941
     3173160.732    13814065.298     3174449.349    13814634.059
#Sta/Elev= 30
 1131.31      30 1444.32   28.33  1705.6      30 1874.22   27.58  2189.5   29.68
 2264.92    27.8 2566.64   29.54 2897.48   27.24 3114.02   29.61  3188.4   27.98
  3454.8   29.64 3612.56      27    3818    29.5 4201.76   26.64  4292.4   29.06
 4677.64   26.76 4899.98   28.37 4932.28   28.35 4954.74   27.25  4971.2   22.55
  4988.4   13.44 4996.76   13.13 5004.69   13.45 5022.75   22.38 5045.26   28.89
  5542.3   29.16 6151.18   30.74  6504.8   27.88 6824.32   28.12  8158.9   31.32
#Mann= 5 ,-1 , 0
 1131.31     .15       0 4899.98     .03       0 4932.28    .021       0
 5045.26     .03       0  5542.3     .15       0
#XS Ineff= 2 , 0
       0    4942      28    5050       0    27.9
Permanent Ineff=
       F       F
#Block Obstruct= 1 ,-1
    1700    3800    27.9
Bank Sta=4932.28,5045.26
Exp/Cntr=0.5,0.3

Type RM Length L Ch R = 1 ,20171.67,392.63,379.56,352.01
XS GIS Cut Line= 6
      3168964.37    13810384.604     3169833.614    13811476.401
     3171511.198    13812957.849     3171896.525    13813274.295
     3173123.694     13814137.05     3174415.287    13814736.246
#Sta/Elev= 30
 1111.96   30.06 1615.17   30.09 1750.57   27.72 1942.42   29.58 2167.31   27.45
 2372.37   29.65 2920.76   27.36 3375.82   29.52  3487.2   27.15 3610.62   29.73
 3716.42   27.38  3864.7   29.59 4044.66   27.01 4236.94   29.02 4685.16    26.9
 4900.54   28.88 4929.92   28.97 4954.74   27.25  4971.2   22.55  4988.4   13.44
 4996.76   13.13 5004.69   13.45 5022.75   22.38 5045.26   28.89 5586.48    29.2
 6069.34   31.11 6533.46    27.9 7439.78   30.57  8042.7   29.38 8168.29    31.4
#Mann= 5 ,-1 , 0
 1111.96     .15       0 4900.54     .03       0 4929.92    .021       0
 5045.26     .03       0 5586.48     .15       0
#XS Ineff= 1 ,-1
    3875    4800      28
Permanent Ineff=
       F
#Block Obstruct= 1 ,-1
    1900    3900    27.9
Bank Sta=4929.92,5045.26
Exp/Cntr=0.3,0.1

Type RM Length L Ch R = 1 ,19792.1 ,1449.06,1375.36,1052.72
XS GIS Cut Line= 6
      3168445.29    13811055.974     3169420.033    13811861.646
     3171537.956    13813438.792     3171643.564    13813541.443
     3172521.423       13814055.      3174340.35     13814913.37
#Sta/Elev= 30
 1073.44   28.83 2995.63    29.5 3207.81   26.52 3455.58    29.2 3641.45   26.67
 3814.66   29.16 3886.23   27.05 4192.25   28.73 4248.41   26.64 4409.86   28.69
 4529.38   25.53 4575.03   28.05 4725.93   28.07  4783.8   25.68 4906.28      28
 4917.32   27.99 4954.74   27.25  4971.2   22.55  4988.4   13.44 4996.76   13.13
 5004.69   13.45 5022.75   22.38 5045.26   28.89 5630.51   28.99 5878.81   30.68
 6971.35   28.26 7116.83   29.97 7258.97   27.98    7596   30.33 8154.72   29.05
#Mann= 5 ,-1 , 0
 1073.44     .15       0 4906.28     .03       0 4917.32    .021       0
 5045.26     .03       0 5630.51     .15       0
#XS Ineff= 1 ,-1
    4400    4900    27.5
Permanent Ineff=
       F
#Block Obstruct= 5 ,-1
    2850    4400    27.2    6350    6550      29
 6733.79 7643.91   29.54 7878.19 8336.67   30.21
Bank Sta=4917.32,5045.26
Exp/Cntr=0.3,0.1

Type RM Length L Ch R = 1 ,18416.74,22.88,20.99,23.19
BEGIN DESCRIPTION:
West Avenue
END DESCRIPTION:
XS GIS Cut Line= 6
       3166637.1     13813591.31     3167123.318    13813685.041
     3170041.978    13814106.454     3170641.055    13814144.602
     3172058.848    13814413.711     3173062.014    13814614.344
#Sta/Elev= 30
 1145.73    12.2 1256.78    28.5 1275.94   28.46 1609.79   26.42 1664.35   28.43
 1803.21   28.84 1923.96   29.11  2051.9   26.97 2145.21   29.18 2283.51   28.62
 2345.79   26.61 2418.77   29.23 2846.48   29.52 2967.72   27.27 3117.13   29.63
  3316.3   27.18 3694.43   29.12 3857.12   27.41 3943.28   28.69 4384.95   27.74
 4652.34   25.48 4895.83   26.82 4922.24   27.05 4958.05   26.18 4966.87   20.82
 4994.99   11.49 5010.52   11.93 5051.95    26.6 5086.39   26.39 7656.32   29.26
#Mann= 8 ,-1 , 0
 1145.73     .07       0 1275.94     .15       0 1803.21     .07       0
 1923.96     .15       0 4895.83     .03       0 4922.24    .021       0
 5051.95     .03       0 5086.39     .15       0
#XS Ineff= 1 ,-1
    4400    4900    26.7
Permanent Ineff=
       F
#Block Obstruct= 2 ,-1
  910.06    2850    29.6    5160    5400    26.6
Bank Sta=4922.24,5051.95
Exp/Cntr=0.5,0.3

Type RM Length L Ch R = 1 ,18395.75,67.5,61.78,62.71
BEGIN DESCRIPTION:
West Avenue
END DESCRIPTION:
XS GIS Cut Line= 6
      3166626.37    13813612.759     3167120.486     13813704.84
     3170039.902    13814126.362     3170638.641    13814164.501
     3172055.022    13814433.342     3173058.092    13814633.956
#Sta/Elev= 30
 1145.23   11.93 1164.23   13.28 1268.09   28.53 1340.74   28.36 1615.01   26.57
 1669.95   28.54  1806.8   28.86 1927.52   29.12 2055.09   27.02 2163.22    29.2
 2350.28   26.67  2428.5   29.24 2852.99   29.55 2974.23   27.33  3127.3   29.51
 3322.81   27.22 3485.48   29.16 3600.29   27.58 3710.27   29.05 3867.44   27.42
 4053.71   28.66    4651   25.38 4906.44   26.84 4922.24   27.05 4958.05   26.18
 4994.99   11.49 5010.52   11.93 5051.95    26.6 5077.67   26.47 7662.18   29.16
#Mann= 8 ,-1 , 0
 1145.23     .07       0 1340.74     .15       0  1806.8     .07       0
 1927.52     .15       0 4906.44    .003       0 4922.24    .021       0
 5051.95     .03       0 5077.67     .15       0
#XS Ineff= 3 ,-1
    4910 4958.05      26 4426.92 4907.95   26.81 5051.95 7662.18    25.5
Permanent Ineff=
       F       F       F
#Block Obstruct= 2 ,-1
 1032.04    2850   29.17    5100    5350    26.4
Bank Sta=4922.24,5051.95
Exp/Cntr=0.5,0.3