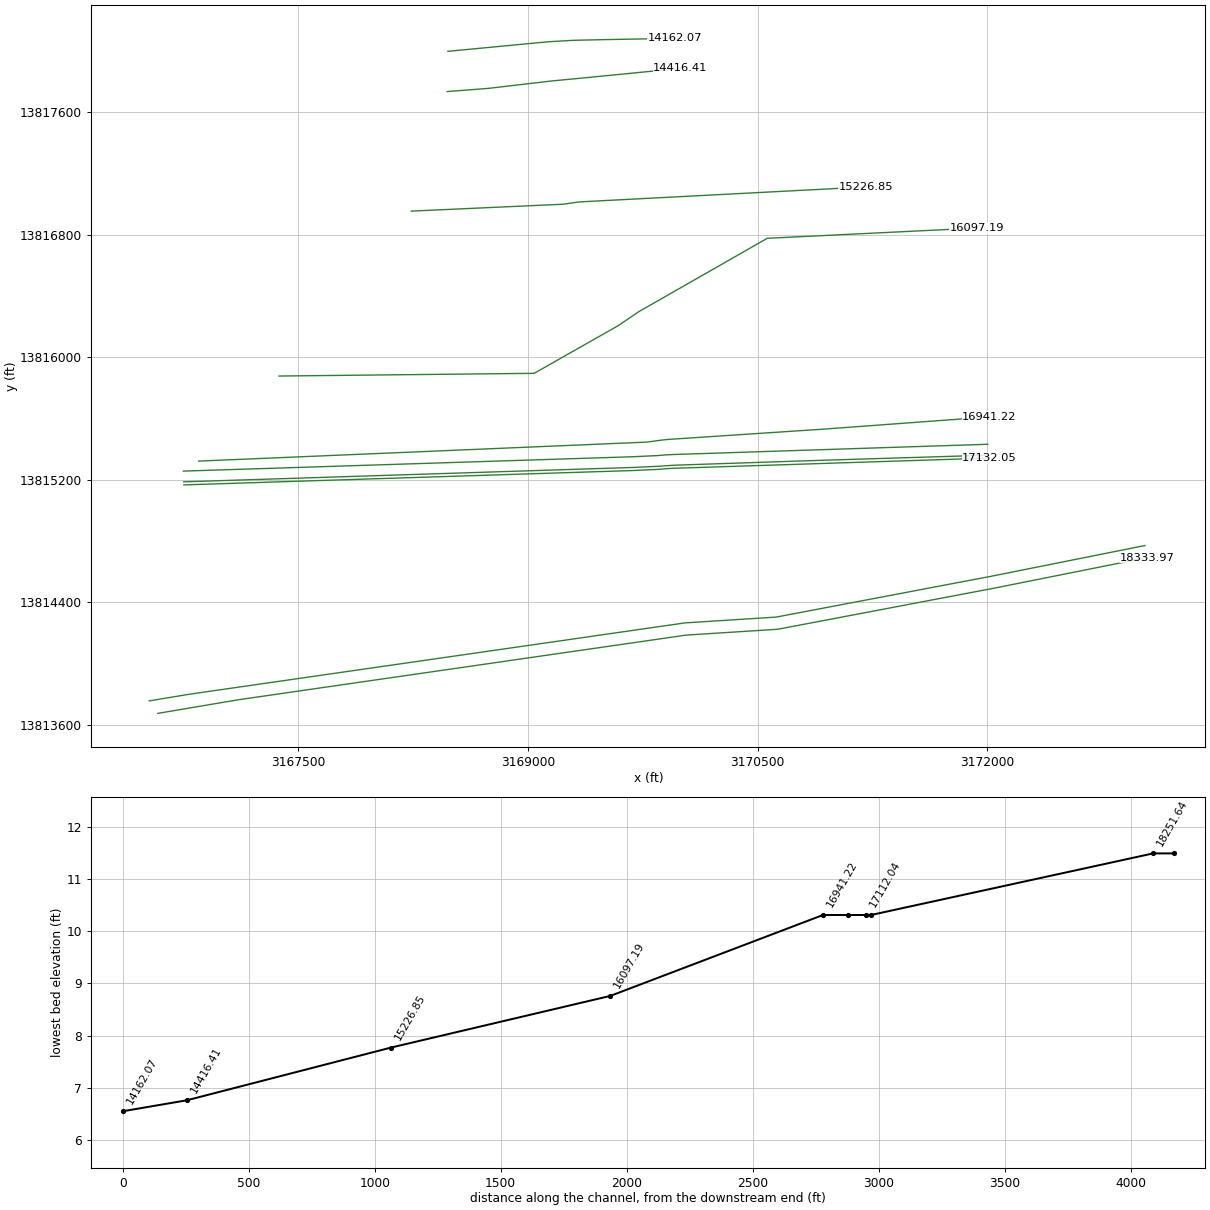
HEC-RAS study I100-00-00.prj: I100-00-00

--- I100-00-00.g01 (geometry) --- (continued)

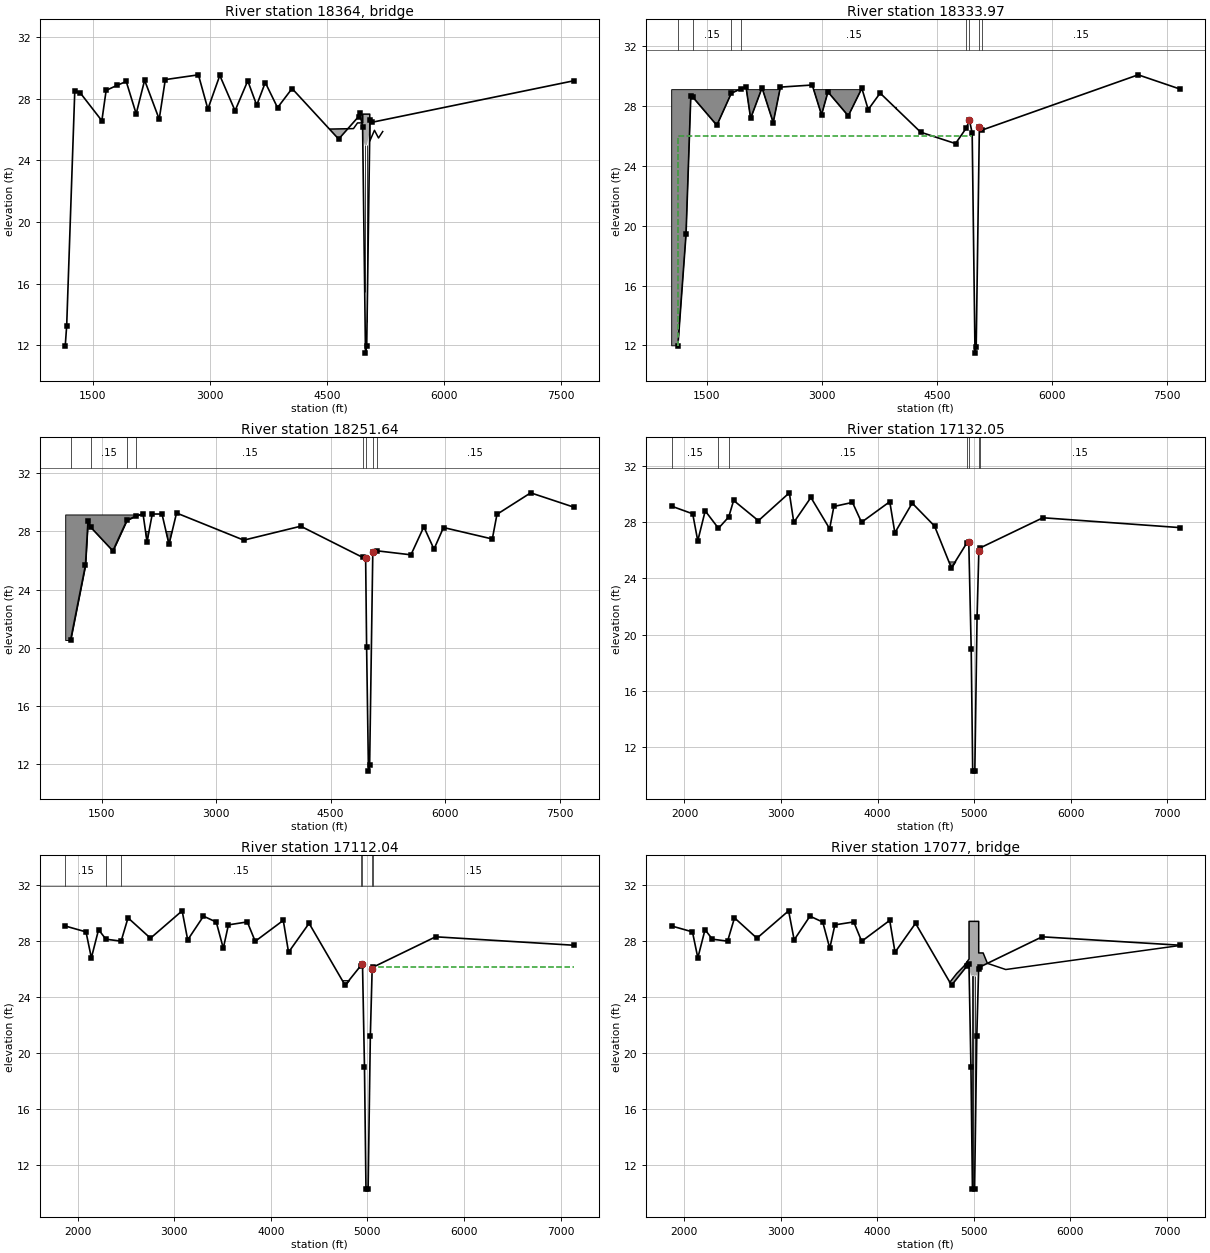
Type RM Length L Ch R = 3 ,18364   ,,,
BEGIN DESCRIPTION:
Bridge at West Avenue
END DESCRIPTION:
Bridge Culvert--1,0,-1,-1, 0
Deck Dist Width WeirC Skew NumUp NumDn MinLoCord MaxHiCord MaxSubmerge Is_Ogee
5,35,2.6,0, 12, 12, , , 0.95, 0, 0,0,,
    4542    4841    4893    4960    4960    4986    5014    5050    5050    5110
    5162    5216
   26.03   26.06   26.43   26.43      27      27      27      27   25.25   25.95
   25.45   25.87
       0       0       0       0      25      25      25      25       0       0
       0       0
    4542    4841    4893    4960    4960    4986    5014    5050    5050    5110
    5162    5216
   26.03   26.06   26.43   26.43      27      27      27      27   25.25   25.95
   25.45    25.6
       0       0       0       0      25      25      25      25       0       0
       0       0
Pier Skew, UpSta & Num, DnSta & Num=  ,4985, 2 ,4985, 2 , 0 , 0 , 0 ,,
       2       2
       0      26
       2       2
       0      26
Pier Skew, UpSta & Num, DnSta & Num=  ,5015, 2 ,5015, 2 , 0 , 0 , 0 ,,
       2       2
       0      26
       2       2
       0      26
BR Coef=-1 , 1 , 0 ,, 0 ,,,0.8,-1,2,0,
WSPro=,,,, 1 ,,,, 0 ,,,, 0 ,,,,-1 ,-1 ,-1 , 0 , 0 , 0 , 0 , 0
BC Design=,, 0 ,, 0 ,,,,,,
BC HTab HWMax=29.86

Type RM Length L Ch R = 1 ,18333.97,85.77,82.32,83.61
BEGIN DESCRIPTION:
West Avenue
END DESCRIPTION:
XS GIS Cut Line= 6
      3166583.47    13813674.963     3167110.959    13813764.087
     3170033.676    13814186.085     3170631.399    13814224.198
     3172043.544    13814492.235     3173046.325    13814692.791
#Sta/Elev= 30
 1120.94   11.98    1227   19.42 1289.25   28.63 1317.35   28.57 1628.91    26.7
 1817.57   28.84 1938.23   29.13 2008.65   29.28 2069.28   27.16 2218.15    29.2
 2363.78   26.88 2457.67   29.25 2872.52   29.39 2993.77    27.4 3077.44   28.93
 3342.34   27.33 3519.63   29.17  3602.4   27.75 3757.78   28.85 4286.74   26.24
 4740.96   25.48 4882.97   26.53 4922.24   27.05 4958.05   26.18 4994.99   11.49
 5010.52   11.93 5051.95    26.6    5091   26.39 7122.47   30.07 7667.88   29.12
#Mann= 8 ,-1 , 0
 1120.94     .07       0 1317.35     .15       0 1817.57     .07       0
 1938.23     .15       0 4882.97     .03       0 4922.24    .021       0
 5051.95     .03       0    5091     .15       0
#XS Ineff= 2 , 0
       0 4958.05      26 5051.95       0    25.7
Permanent Ineff=
       F       F
#Block Obstruct= 2 ,-1
 1039.82 3500.57   29.08    3501    3970    27.9
Bank Sta=4922.24,5051.95
Exp/Cntr=0.5,0.3

Type RM Length L Ch R = 1 ,18251.64,1070.93,1119.59,1079.36
BEGIN DESCRIPTION:
West Avenue
END DESCRIPTION:
XS GIS Cut Line= 6
       3166527.7    13813756.471     3166789.891    13813800.084
     3170025.375    13814265.716     3170621.743    13814303.793
      3172028.24    13814570.758     3173030.635    13814771.237
#Sta/Elev= 30
 1094.47   20.52 1289.08   25.68  1322.6   28.75 1357.91   28.29 1647.75   26.66
 1831.92   28.77  1952.5   29.07 2042.82   29.22  2095.3   27.28 2163.82    29.2
 2291.36    29.2 2383.26   27.11  2481.9   29.27 3362.46    27.4 4108.34   28.36
 4920.15   26.21 4958.05   26.18 4970.93   20.01 4994.99   11.49 5010.52   11.93
 5051.95    26.6 5100.35   26.67 5551.36   26.39 5720.38   28.32 5853.02   26.78
  5977.9   28.27 6616.92   27.48 6678.04   29.18 7119.84   30.66 7680.53   29.68
#Mann= 8 ,-1 , 0
 1094.47     .07       0 1357.91     .15       0 1831.92     .07       0
  1952.5     .15       0 4920.15     .03       0 4958.05    .019       0
 5051.95     .03       0 5100.35     .15       0
#Block Obstruct= 3 ,-1
 1023.89  2027.3   29.17 4652.75  4743.4   26.19    1900    2500      28
Bank Sta=4958.05,5051.95
Exp/Cntr=0.3,0.1

Type RM Length L Ch R = 1 ,17132.05,20.95,20,21.07
BEGIN DESCRIPTION:
Allendale Road
END DESCRIPTION:
XS GIS Cut Line= 6
     3166753.271    13815167.069     3169682.639    13815260.679
     3169852.954     13815268.51     3169906.764     13815273.24
     3169957.916    13815275.578     3172014.445    13815342.236
#Sta/Elev= 30
  1867.8   29.12 2085.64   28.58 2138.04   26.66 2215.02   28.79 2352.26   27.55
 2458.96   28.36 2509.32   29.53 2765.88   28.09 3086.28   30.07 3132.62   27.97
 3309.58   29.74 3503.74   27.52  3547.5    29.1 3740.08   29.39  3833.9   27.98
 4126.48   29.44 4179.08   27.23 4358.46   29.34 4590.12   27.71 4764.38   24.74
 4924.52   26.51 4944.54   26.61  4969.7   18.98 4985.23   10.31 5007.28   10.33
  5030.3   21.22 5049.05   25.96 5059.59   26.15 5712.22    28.3    7132    27.6
#Mann= 7 ,-1 , 0
  1867.8     .15       0 2352.26     .07       0 2458.96     .15       0
 4924.52     .03       0 4944.54     .02       0 5049.05     .03       0
 5059.59     .15       0
#Block Obstruct= 1 ,-1
    4650    4850    25.2
Bank Sta=4944.54,5049.05
Exp/Cntr=0.5,0.3

Type RM Length L Ch R = 1 ,17112.04,72.43,70.17,73.73
BEGIN DESCRIPTION:
Allendale Road
END DESCRIPTION:
XS GIS Cut Line= 6
     3166752.633    13815187.059      3169681.86    13815280.665
     3169851.619     13815288.47     3169957.125    13815295.563
     3170868.052    13815326.069     3172011.524    13815361.158
#Sta/Elev= 30
 1871.81   29.05 2086.96   28.63 2142.68   26.78 2217.12   28.79 2292.76   28.11
 2450.62   27.97 2522.08   29.63 2754.28   28.18 3082.23   30.13 3139.78   28.06
 3303.15   29.75 3435.49   29.33 3508.37   27.46 3561.17   29.13 3756.72   29.34
 3838.54   27.96 4129.02   29.45 4183.72   27.18 4396.23   29.24 4769.02   24.83
 4928.71    26.2 4949.19   26.35  4969.7   18.98 4985.23   10.31 5007.28   10.33
  5030.3   21.22 5049.05   25.96 5062.39   26.13 5706.51   28.28 7133.69   27.68
#Mann= 7 ,-1 , 0
 1871.81     .15       0 2292.76     .07       0 2450.62     .15       0
 4928.71     .03       0 4949.19     .02       0 5049.05     .03       0
 5062.39     .15       0
#XS Ineff= 2 , 0
       0    4947      25    5050       0    26.1
Permanent Ineff=
       F       F
#Block Obstruct= 1 ,-1
    4650    4850    25.2
Bank Sta=4949.19,5049.05
Exp/Cntr=0.5,0.3

Type RM Length L Ch R = 3 ,17077   ,,,
BEGIN DESCRIPTION:
Bridge at Allendale Road
END DESCRIPTION:
Bridge Culvert--1,0,-1,-1, 0
Deck Dist Width WeirC Skew NumUp NumDn MinLoCord MaxHiCord MaxSubmerge Is_Ogee
7,40,2.6,0, 12, 12, , , 0.95, 0, 0,0,,
    4749    4823    4897    4950    4950    5000    5050    5050    5096    5140
    5330    7122
   25.02   25.67   26.19    26.7   29.38   29.38   29.38   27.13   27.13   26.39
   25.95   27.65
       0       0       0       0   25.52   25.52   25.52       0       0       0
       0       0
    4749    4823    4897    4950    4950    5000    5050    5050    5096    5140
    5330    7122
   25.02   25.67   26.19    26.7   29.38   29.38   29.38   27.13   27.13   26.39
   25.95   27.65
       0       0       0       0   25.52   25.52   25.52       0       0       0
       0       0
Pier Skew, UpSta & Num, DnSta & Num=  ,4985, 4 ,4985, 4 , 3 , 3 , 0 ,,
     1.4     1.4       3       3
       0   22.52   22.52      26
     1.4     1.4       3       3
       0   22.52   22.52      26
Pier Skew, UpSta & Num, DnSta & Num=  ,5015, 4 ,5015, 4 , 3 , 3 , 0 ,,
     1.4     1.4       3       3
       0   22.52   22.52      26
     1.4     1.4       3       3
       0   22.52   22.52      26
BR Coef=-1 , 1 , 0 ,, 0 ,,,0.8,-1,2,0,
WSPro=,,,, 1 ,,,, 0 ,,,, 0 ,,,,-1 ,-1 ,-1 , 0 , 0 , 0 , 0 , 0
BC Design=,, 0 ,, 0 ,,,,,,
BC HTab HWMax=30.13

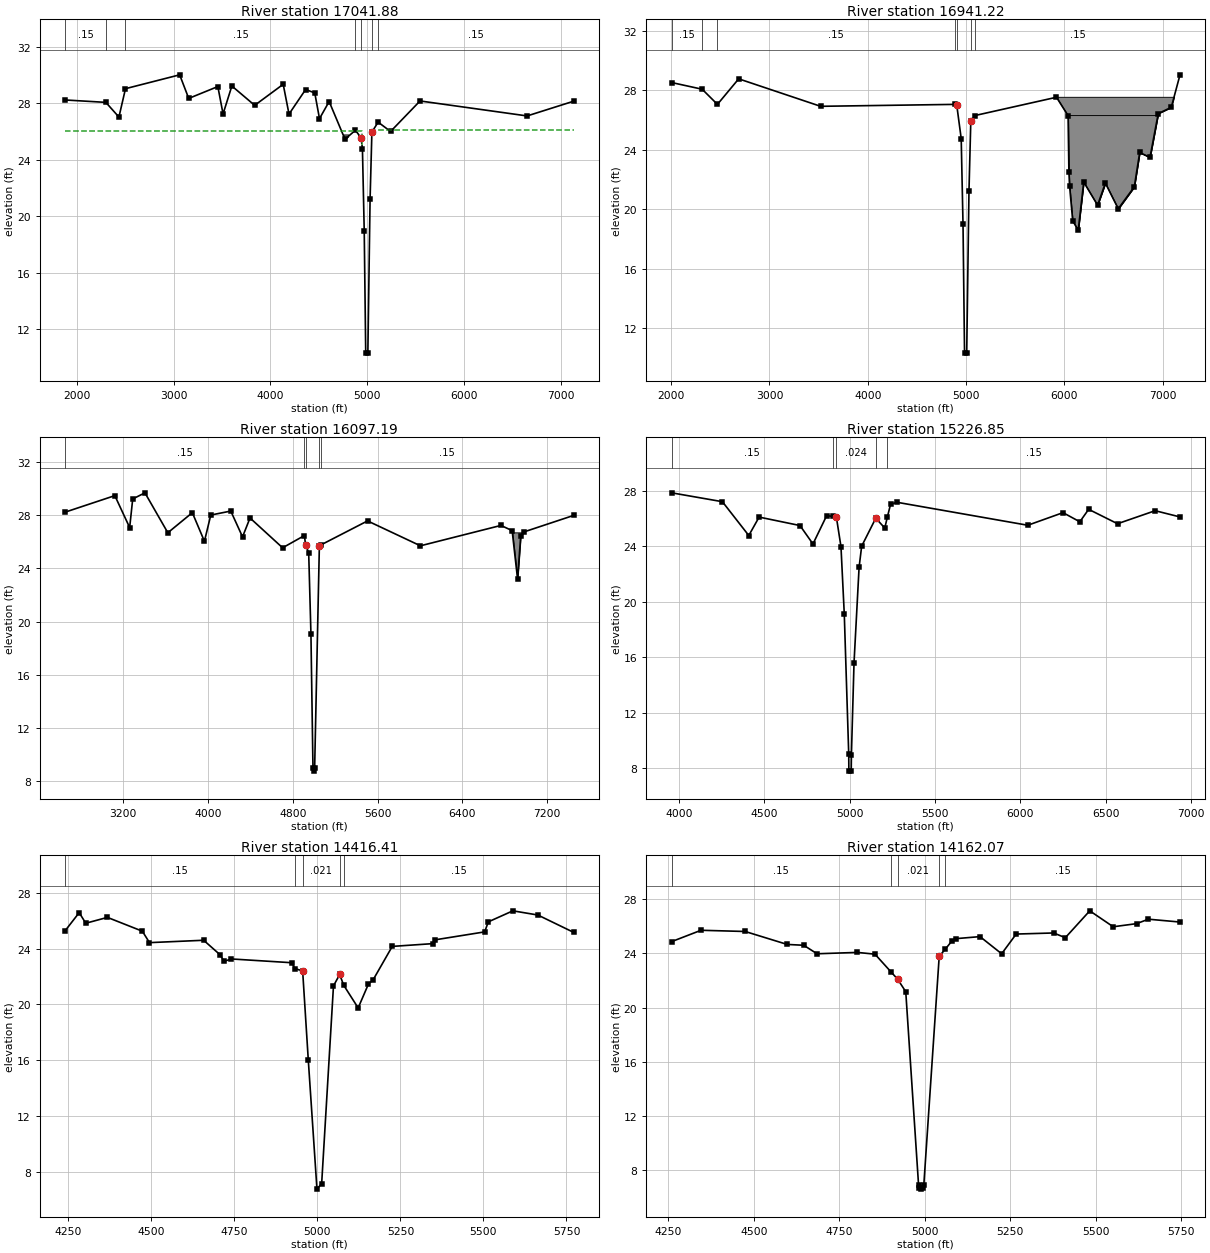
Type RM Length L Ch R = 1 ,17041.88,93.4,100.66,115.87
BEGIN DESCRIPTION:
Allendale Road
END DESCRIPTION:
XS GIS Cut Line= 6
     3166750.397    13815257.023     3169679.135    13815350.613
     3169846.945    13815358.329     3169900.766     13815363.06
     3169954.355     13815365.51     3172003.558    13815432.338
#Sta/Elev= 30
 1877.82   28.23 2298.32   28.06 2433.28   27.02  2501.1   29.03 3061.44   30.01
 3154.94   28.34 3456.18   29.18  3510.1   27.24    3601   29.22 3836.98   27.85
 4131.94   29.34 4191.98   27.23  4363.8   28.97 4458.26   28.73 4507.14   26.91
 4607.06   28.12 4770.84   25.45    4879   26.09 4938.22   25.53 4951.24   24.76
  4969.7   18.98 4985.23   10.31 5007.28   10.33  5030.3   21.22 5049.05   25.96
 5113.48   26.66  5242.3      26 5546.78   28.16  6654.2    27.1 7134.02   28.14
#Mann= 7 ,-1 , 0
 1877.82     .15       0 2298.32     .07       0  2501.1     .15       0
    4879     .03       0 4938.22    .021       0 5049.05     .03       0
 5113.48     .15       0
#XS Ineff= 2 , 0
       0    4947      26    5050       0    26.1
Permanent Ineff=
       F       F
#Block Obstruct= 1 ,-1
 4742.77 4803.11   25.79
Bank Sta=4938.22,5049.05
Exp/Cntr=0.5,0.3

Type RM Length L Ch R = 1 ,16941.22,674.32,844.03,972.21
BEGIN DESCRIPTION:
Allendale Road
END DESCRIPTION:
XS GIS Cut Line= 6
     3166850.462    13815322.423     3169778.482    13815446.442
     3169873.543    13815459.583     3169915.849    13815463.904
     3170926.871    13815530.783     3172014.193    13815611.059
#Sta/Elev= 30
 2005.04   28.53  2315.4   28.08 2470.58   27.06 2686.96   28.78 3520.56   26.93
 4886.01   27.06 4905.42   27.04 4951.24   24.76  4969.7   18.98 4985.23   10.31
 5007.28   10.33  5030.3   21.22 5049.05   25.96 5091.97   26.31  5920.7   27.54
 6038.78    26.3 6047.14   22.54 6053.82   21.58 6085.94   19.22 6141.88   18.58
    6198   21.83  6339.1   20.27  6418.1   21.76 6549.32   20.03 6712.62   21.51
  6767.7   23.82 6872.24   23.49 6956.22   26.44 7088.98   26.86 7177.68   29.05
#Mann= 7 ,-1 , 0
 2005.04     .15       0  2315.4     .07       0 2470.58     .15       0
 4886.01     .03       0 4905.42    .022       0 5049.05     .03       0
 5091.97     .15       0
#Block Obstruct= 3 ,-1
 5890.79 7365.19   27.57 5945.39 7133.11   26.34    5160    5380   26.35
Bank Sta=4905.42,5049.05
Exp/Cntr=0.3,0.1

Type RM Length L Ch R = 1 ,16097.19,954.66,870.34,699.28
XS GIS Cut Line= 6
     3167375.473    13815877.878      3169041.49    13815895.561
     3169591.046    13816207.404     3169724.569     13816298.14
     3170563.764    13816777.333     3171930.572    13816844.111
#Sta/Elev= 30
 2653.22   28.22 3121.33   29.46 3261.14   27.06 3289.93   29.21 3405.14   29.67
 3621.16   26.67 3852.17   28.18 3966.18   26.03 4026.19      28 4214.82    28.3
 4325.73   26.36 4396.16   27.78 4703.74   25.54 4909.29   26.46 4919.66   25.78
 4949.66   25.16 4970.76   19.08 4989.98    8.99 4997.18    8.76 5005.65    8.96
 5050.25   25.66 5063.36   25.75 5504.69   27.56 6003.48   25.69 6762.68   27.22
 6868.49   26.83 6919.62   23.19 6949.65   26.44 6978.56   26.73 7447.46   27.97
#Mann= 5 ,-1 , 0
 2653.22     .15       0 4909.29     .03       0 4919.66    .021       0
 5050.25     .03       0 5063.36     .15       0
#Block Obstruct= 1 ,-1
 6849.19 6982.14    26.7
Bank Sta=4919.66,5050.25
Exp/Cntr=0.3,0.1

Type RM Length L Ch R = 1 ,15226.85,800.22,810.44,816.42
XS GIS Cut Line= 4
     3168238.573    13816954.796     3169231.176    13816999.915
     3169336.452    13817014.954     3171208.863    13817112.711
#Sta/Elev= 30
 3958.78   27.85  4255.6   27.21 4410.04   24.77 4470.52    26.1 4709.64   25.49
  4785.7   24.16 4865.68    26.2 4901.56   26.15 4922.68    26.1 4949.58   23.97
    4969   19.08 4994.98    8.99 4995.74    7.77 5009.56    7.77 5010.65    8.96
    5026    15.6 5055.62   22.48 5070.68      24 5153.24   26.02 5205.86   25.31
 5220.68   26.08 5239.48   27.01 5276.42   27.17 6042.84   25.51 6249.06   26.42
 6347.46   25.76  6399.1   26.66  6568.1   25.62 6788.34   26.56  6933.7   26.11
#Mann= 5 ,-1 , 0
 3958.78     .15       0 4901.56     .03       0 4922.68    .024       0
 5153.24     .03       0 5220.68     .15       0
#XS Ineff= 1 ,-1
    4700    4850    24.7
Permanent Ineff=
       F
Bank Sta=4922.68,5153.24
Exp/Cntr=0.3,0.1

Type RM Length L Ch R = 1 ,14416.41,260.96,254.34,243.76
XS GIS Cut Line= 5
     3168473.484    13817735.617     3168741.369    13817756.223
     3169161.109    13817805.409     3169295.308    13817817.924
     3169996.078    13817886.732
#Sta/Elev= 30
 4241.02   25.29 4283.14   26.58 4302.91   25.82 4368.05   26.24 4473.23   25.25
  4494.7   24.43 4657.81    24.6 4707.24   23.56 4719.16   23.09 4741.33   23.26
 4922.95   22.99 4932.61   22.57 4955.79    22.4 4972.81      16 4998.87    6.76
 5013.03    7.16  5048.6   21.33 5067.39   22.15    5079   21.39 5122.88   19.75
 5153.99   21.47 5168.09   21.77 5225.52   24.16 5348.96   24.36 5354.15   24.63
 5503.64    25.2 5514.75   25.92 5588.68   26.71 5663.81   26.41 5771.23   25.17
#Mann= 5 ,-1 , 0
 4241.02     .15       0 4932.61     .03       0 4955.79    .021       0
 5067.39     .03       0    5079     .15       0
Bank Sta=4955.79,5067.39
Exp/Cntr=0.3,0.1

Type RM Length L Ch R = 1 ,14162.07,19.01,19.57,22.57
BEGIN DESCRIPTION:
Southmore Ave
END DESCRIPTION:
XS GIS Cut Line= 5
     3168477.887    13817998.274     3169137.306    13818061.147
     3169296.097    13818070.173      3169481.26    13818074.388
     3169960.638    13818083.131
#Sta/Elev= 30
 4259.91   24.88 4345.72   25.72 4474.79   25.63 4597.87   24.67 4646.01   24.61
 4684.85   23.98 4803.09   24.08 4854.27   23.95 4900.67   22.65 4920.42    22.1
 4944.27   21.17 4981.71    6.86 4982.53    6.67  4987.4    6.55 4995.69    6.61
 4997.05    6.86 5042.08   23.79 5060.19   24.33 5079.58   24.94  5091.1    25.1
 5161.36   25.25  5224.6   23.98 5267.13   25.44 5376.63   25.52 5410.79   25.17
 5482.21   27.16  5550.8   25.98 5619.03   26.21 5653.71   26.54 5746.04   26.33
#Mann= 5 ,-1 , 0
 4259.91     .15       0 4900.67     .03       0 4920.42    .021       0
 5042.08     .03       0 5060.19     .15       0
Bank Sta=4920.42,5042.08
Exp/Cntr=0.5,0.3