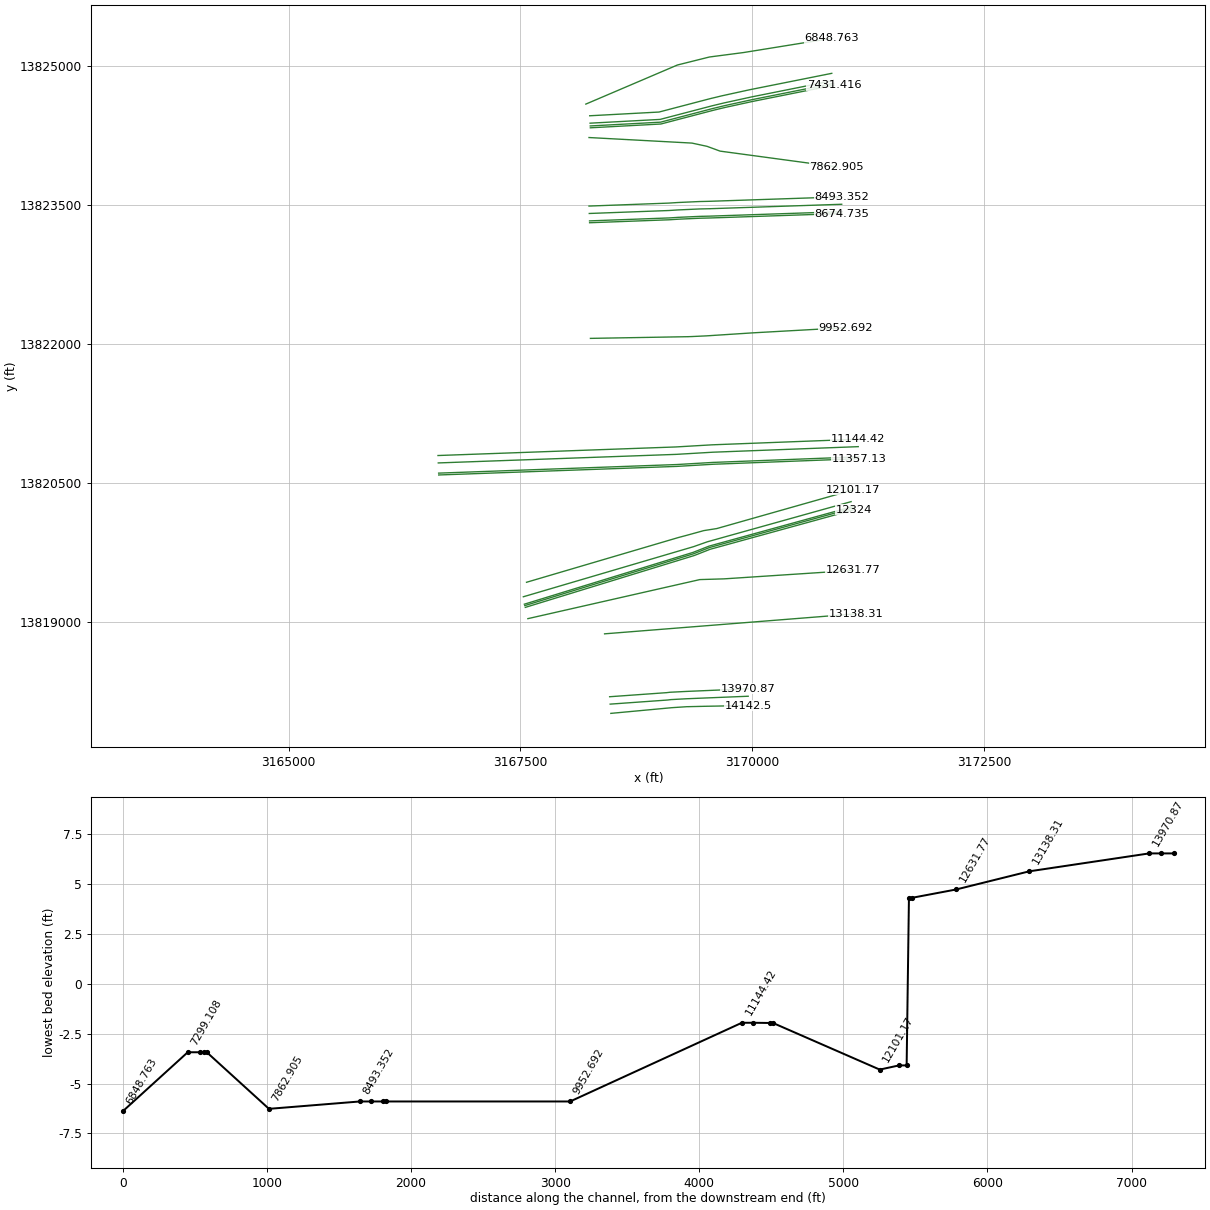
HEC-RAS study I100-00-00.prj: I100-00-00

--- I100-00-00.g01 (geometry) --- (continued)

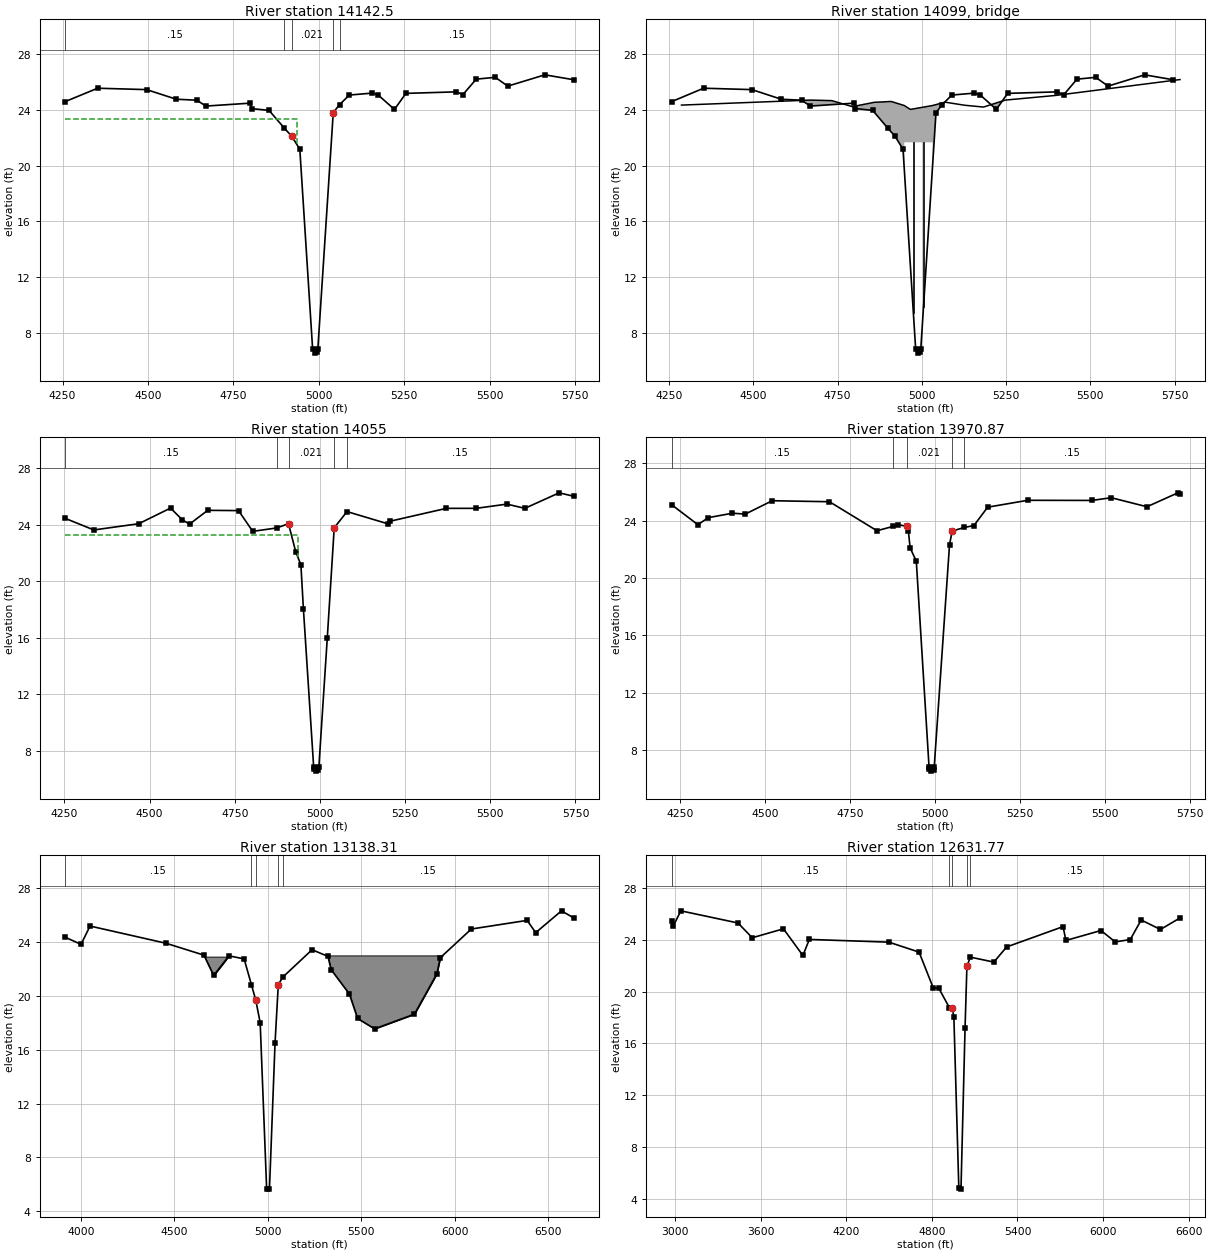
Type RM Length L Ch R = 1 ,14142.5 ,89.62,87.5,103.99
BEGIN DESCRIPTION:
Southmore Ave
END DESCRIPTION:
XS GIS Cut Line= 5
     3168476.459    13818018.223     3169136.375    13818079.763
     3169294.444    13818090.141      3169480.85    13818094.384
     3169960.273    13818103.128
#Sta/Elev= 30
 4257.92   24.58  4352.7   25.54 4495.94   25.44 4583.12   24.75 4643.24   24.68
  4669.3   24.26 4799.42   24.47 4803.09   24.08 4854.27   23.95 4899.32   22.67
 4920.42    22.1 4944.27   21.17 4981.71    6.86  4987.4    6.55 4995.69    6.61
 4997.05    6.86 5042.08   23.79 5060.38   24.36 5089.08   25.05 5156.04   25.19
  5172.8   25.07 5221.14   24.02 5254.68   25.17 5402.36   25.28  5421.4   25.08
 5460.34   26.19    5516   26.32  5552.7   25.69 5661.16    26.5 5745.06   26.15
#Mann= 5 ,-1 , 0
 4257.92     .15       0 4899.32     .03       0 4920.42    .021       0
 5042.08     .03       0 5060.38     .15       0
#XS Ineff= 2 , 0
       0    4935    23.3    5044       0    23.3
Permanent Ineff=
       F       F
Bank Sta=4920.42,5042.08
Exp/Cntr=0.5,0.3

Type RM Length L Ch R = 3 ,14099   ,,,
BEGIN DESCRIPTION:
Bridge at Southmore Ave
END DESCRIPTION:
Bridge Culvert--1,0,-1,-1, 0
Deck Dist Width WeirC Skew NumUp NumDn MinLoCord MaxHiCord MaxSubmerge Is_Ogee
12,55,2.6,0, 17, 18, , , 0.95, 0, 0,0,,
    4287    4670    4733    4794    4859    4909    4948    4948    4966    5032
    5032    5069    5127    5183    5248    5396    5766
   24.33   24.69   24.65   24.22   24.53   24.59    24.3    24.3   24.02    24.3
    24.3   24.54   24.32   24.19   24.69   25.02   26.16
       0       0       0       0       0       0       0   21.66   21.66   21.66
       0       0       0       0       0       0       0
    4252    4287    4670    4733    4794    4859    4909    4948    4948    4966
    5032    5032    5069    5127    5183    5248    5396    5766
    24.3   24.33   24.69   24.65   24.22   24.53   24.59    24.3    24.3   24.02
    24.3    24.3   24.54   24.32   24.19   24.69   25.02   26.16
       0       0       0       0       0       0       0       0   21.66   21.66
   21.66       0       0       0       0       0       0       0
Pier Skew, UpSta & Num, DnSta & Num=  ,4975, 4 ,4975, 4 , 3 , 3 , 0 ,,
       1       1       2       2
       0   20.66   20.66      22
       1       1       2       2
       0   20.66   20.66      22
Pier Skew, UpSta & Num, DnSta & Num=  ,5005, 4 ,5005, 4 , 3 , 3 , 0 ,,
       1       1       2       2
       0   20.66   20.66      22
       1       1       2       2
       0   20.66   20.66      22
BR Coef=-1 , 1 , 0 ,, 0 ,,,0.8,-1,2,0,
WSPro=,,,, 1 ,,,, 0 ,,,, 0 ,,,,-1 ,-1 ,-1 , 0 , 0 , 0 , 0 , 0
BC Design=,, 0 ,, 0 ,,,,,,
BC HTab HWMax=26.5

Type RM Length L Ch R = 1 ,14055   ,81.18,84.13,89.5
BEGIN DESCRIPTION:
Southmore Ave
END DESCRIPTION:
XS GIS Cut Line= 5
     3168469.319    13818117.968     3169087.954    13818162.253
     3169123.649    13818166.669     3169287.169    13818175.639
      3169958.45    13818203.111
#Sta/Elev= 30
 4252.61   24.46 4336.68   23.64 4468.33   24.08 4561.74   25.19  4595.7   24.37
 4617.42   24.05 4670.81   25.03  4761.3   25.01 4802.91   23.54 4872.83   23.78
    4908   24.08    4929    22.1 4944.27   21.17 4951.73   18.02 4981.71    6.86
 4982.53    6.67  4987.4    6.55 4995.69    6.61 4997.05    6.86 5021.77      16
 5042.08   23.79 5079.58   24.94 5200.35   24.07  5206.3   24.26 5371.31   25.17
 5458.24   25.17 5548.99   25.47  5601.4   25.17 5702.22   26.27  5744.4   26.03
#Mann= 5 ,-1 , 0
 4252.61     .15       0 4872.83     .03       0    4908    .021       0
 5042.08     .03       0 5079.58     .15       0
#XS Ineff= 2 , 0
       0    4935    23.3    5044       0    23.3
Permanent Ineff=
       F       F
Bank Sta=4908,5042.08
Exp/Cntr=0.5,0.3

Type RM Length L Ch R = 1 ,13970.87,714.42,832.55,738.24
BEGIN DESCRIPTION:
Southmore Ave
END DESCRIPTION:
XS GIS Cut Line= 5
     3168463.607    13818197.764     3169080.182    13818241.901
     3169113.058    13818245.968     3169305.786     13818255.69
     3169956.991    13818283.098
#Sta/Elev= 30
 4224.31    25.1 4301.46   23.71  4331.8    24.2    4403   24.51 4441.06   24.45
 4520.22   25.38 4688.75   25.31 4828.52   23.29 4875.59   23.59 4891.43    23.7
    4916   23.61    4921   23.27    4926    22.1 4944.27   21.17 4981.71    6.86
 4982.53    6.67  4987.4    6.55 4995.69    6.61 4997.05    6.86 5042.08   22.33
    5050   23.27 5085.96   23.52 5113.74   23.65 5154.33   24.93 5272.23   25.41
 5461.16    25.4 5518.01   25.59 5623.04   24.96 5714.23   25.93 5720.34   25.86
#Mann= 5 ,-1 , 0
 4224.31     .15       0 4875.59     .03       0    4916    .021       0
    5050     .03       0 5085.96     .15       0
Bank Sta=4916,5050
Exp/Cntr=0.3,0.1

Type RM Length L Ch R = 1 ,13138.31,451.99,506.55,488.39
XS GIS Cut Line= 2
     3168409.125      13818876.3      3171120.75    13819092.193
#Sta/Elev= 30
    3916   24.35 4000.62   23.82 4048.88   25.18 4456.02    23.9 4658.36   23.02
  4710.2   21.51 4792.46   22.97 4873.42   22.74 4912.23   20.84 4935.72   19.68
 4959.31   18.01 4994.01    5.65 5009.03    5.65    5039   16.53  5056.3   20.83
 5080.41   21.39 5236.86   23.42 5322.04   22.93  5338.7   21.95  5436.8   20.13
 5480.42   18.32  5571.6   17.55 5784.88   18.64 5904.78   21.63 5923.26   22.83
 6089.32   24.96  6387.8    25.6 6433.76   24.69 6571.82   26.31  6636.2   25.79
#Mann= 5 ,-1 , 0
    3916     .15       0 4912.23     .03       0 4935.72    .021       0
  5056.3     .03       0 5080.41     .15       0
#Block Obstruct= 3 ,-1
 4579.07 4794.08   22.68 4649.76 4791.96   22.91 5275.88  5972.7      23
Bank Sta=4935.72,5056.3
Exp/Cntr=0.3,0.1

Type RM Length L Ch R = 1 ,12631.77,243.15,307.77,369.93
XS GIS Cut Line= 4
     3167581.494    13819040.084      3169436.49    13819461.503
     3169698.643    13819469.407     3171093.755     13819561.31
#Sta/Elev= 30
  2976.4   25.42 2987.06   25.05 3040.48   26.24 3441.12    25.3 3541.32   24.16
 3759.66   24.85 3895.98   22.79  3941.2   24.03 4498.82   23.82 4710.34   23.05
 4809.86   20.28 4848.06   20.27 4923.32   18.75 4943.04   18.72 4954.31   18.01
 4989.01     4.8 5004.03    4.74 5032.57   17.18 5045.69   21.98 5070.28   22.66
  5234.4   22.28 5324.14   23.45 5719.62   25.02 5739.42   23.95 5985.08   24.72
 6085.16   23.84  6190.4   24.02 6266.98   25.53 6402.02    24.8 6539.08   25.69
#Mann= 5 ,-1 , 0
  2976.4     .15       0 4923.32     .03       0 4943.04    .019       0
 5045.69     .03       0 5070.28     .15       0
Bank Sta=4943.04,5045.69
Exp/Cntr=0.3,0.1

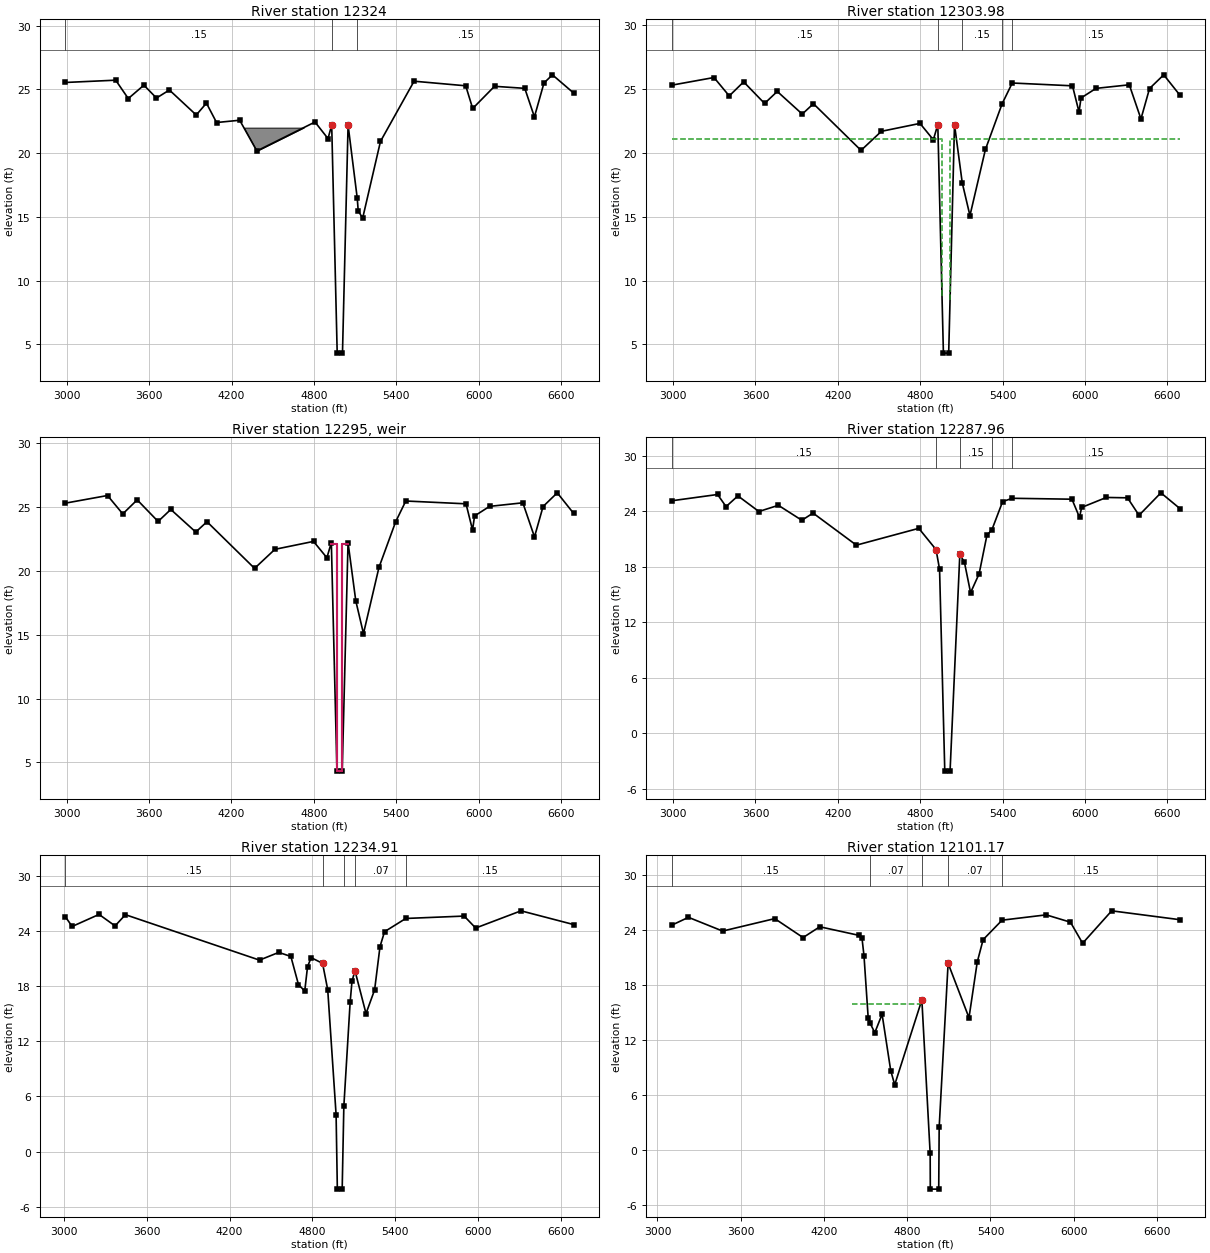
Type RM Length L Ch R = 1 ,12324   ,20.1,20.02,20.32
BEGIN DESCRIPTION:
Obstruction
END DESCRIPTION:
XS GIS Cut Line= 4
     3167554.132     13819161.68     3169376.684    13819721.256
      3169546.99    13819788.186     3171101.136    13820215.586
#Sta/Elev= 30
 2988.32   25.54 3355.87   25.72 3447.58   24.28 3561.36   25.33 3652.78   24.32
  3746.9   24.95 3942.52   22.99 4016.62   23.92 4090.42    22.4 4258.89   22.58
 4383.68   20.17 4807.27   22.44  4901.9   21.14 4928.76    22.2  4968.8    4.32
 5007.25    4.32 5048.04    22.2 5114.91   16.45 5121.81   15.47  5154.4   14.91
 5283.91   20.92 5528.55   25.64 5904.64   25.28 5955.35    23.5  6114.3   25.24
 6334.75   25.08 6404.83   22.84 6474.44    25.5    6536   26.14 6689.67   24.72
#Mann= 3 ,-1 , 0
 2988.32     .15       0 4928.76    .015       0 5114.91     .15       0
#XS Ineff= 1 ,-1
 5052.56  5317.8    21.2
Permanent Ineff=
       T
#Block Obstruct= 1 ,-1
    4250    4800      22
Bank Sta=4928.76,5048.04
Exp/Cntr=0.8,0.6

Type RM Length L Ch R = 1 ,12303.98,16.08,16.01,16.26
BEGIN DESCRIPTION:
Obstruction
END DESCRIPTION:
XS GIS Cut Line= 4
     3167548.262    13819180.799     3169370.081    13819740.151
     3169540.663    13819807.188     3171095.832     13820234.87
#Sta/Elev= 30
 2989.85   25.28    3298   25.88 3409.05   24.44 3514.03   25.54 3666.38   23.85
 3758.79   24.79  3940.7   23.02 4022.32   23.83 4368.87   20.18 4517.01   21.67
  4798.2   22.29  4895.6   21.01 4927.96    22.2  4968.8    4.32 5007.25    4.32
 5049.56    22.2    5106   17.64 5162.03   15.08 5274.66   20.25 5396.11   23.82
 5470.15   25.45 5908.83   25.23  5956.4   23.18 5970.98   24.28  6080.2   25.03
 6322.59   25.31 6407.42   22.64 6469.95   25.02 6573.29   26.09 6691.79   24.49
#Mann= 5 ,-1 , 0
 2989.85     .15       0 4927.96    .015       0    5106     .15       0
 5396.11     .07       0 5470.15     .15       0
#XS Ineff= 2 , 0
       0    4959    21.1    5017       0    21.1
Permanent Ineff=
       F       T
Bank Sta=4927.96,5049.56
Exp/Cntr=0.8,0.6

Type RM Length L Ch R = 5 ,12295   ,,,
BEGIN DESCRIPTION:
Weir
END DESCRIPTION:
IW Pilot Flow=0
#Inline Weir SE= 6
    4927    22.1  4968.8    22.1  4968.8    4.33 5007.25    4.33 5007.25    22.1
    5050    22.1
IW Dist,WD,Coef,Skew,MaxSub,Min_El,Is_Ogee,SpillHt,DesHd
4,3,3.2,0,0.95,, 0 ,,,0,0,

Type RM Length L Ch R = 1 ,12287.96,61.83,53.05,51.65
BEGIN DESCRIPTION:
Obstruction
END DESCRIPTION:
XS GIS Cut Line= 4
     3167543.565    13819196.095     3169364.799    13819755.266
     3169535.601    13819822.391      3171091.59    13820250.297
#Sta/Elev= 30
 2989.59   25.15 3323.81   25.83 3385.79   24.52 3472.05   25.68  3624.9   23.99
 3766.81   24.66 3937.77   23.04 4019.38   23.82  4334.9   20.35 4789.46   22.17
 4915.15   19.87 4940.76   17.74  4978.8   -4.09 5017.25   -4.09 5088.35   19.35
 5121.96    18.5 5166.64   15.21 5228.87   17.25  5285.7   21.42 5322.11   22.02
 5399.97   25.06 5470.21   25.42 5905.11   25.32 5960.04   23.36  5975.6   24.43
 6155.62   25.51 6309.81   25.47 6393.61   23.58 6552.81   26.01 6692.01    24.3
#Mann= 5 ,-1 , 0
 2989.59     .15       0 4915.15     .03       0 5088.35     .15       0
 5322.11     .07       0 5470.21     .15       0
#XS Ineff= 1 ,-1
 5095.56  5264.5    18.7
Permanent Ineff=
       T
Bank Sta=4915.15,5088.35
Exp/Cntr=0.8,0.6

Type RM Length L Ch R = 1 ,12234.91,145.85,133.74,113.25
BEGIN DESCRIPTION:
Obstruction
END DESCRIPTION:
XS GIS Cut Line= 4
     3167532.616    13819276.203     3169368.261    13819816.493
     3169518.837    13819869.569     3171068.645     13820302.37
#Sta/Elev= 30
 3009.74   25.55    3060   24.47 3254.96   25.78  3370.9   24.53 3445.98   25.75
 4417.18   20.81 4556.64   21.65 4644.32   21.21 4699.52   18.15 4744.86   17.45
  4765.2    20.1 4791.18   21.08 4873.96   20.46  4911.4   17.59    4972    4.01
 4981.08   -4.09 5016.08   -4.09 5028.12    4.91  5073.8   16.24 5087.06   18.49
 5108.62   19.67 5188.78      15 5251.08   17.58 5289.98   22.27 5322.86    23.9
 5476.86   25.34  5899.8    25.6 5983.06    24.3 6311.52   26.17    6692   24.68
#Mann= 5 ,-1 , 0
 3009.74     .15       0 4873.96     .03       0 5028.12     .15       0
 5108.62     .07       0 5476.86     .15       0
#XS Ineff= 2 ,-1
 4615.47  4806.6   20.66 5106.94 5288.96   18.77
Permanent Ineff=
       F       F
Bank Sta=4873.96,5108.62
Exp/Cntr=0.3,0.1

Type RM Length L Ch R = 1 ,12101.17,813.51,744.04,671.14
XS GIS Cut Line= 6
     3167566.948    13819432.497     3169205.202    13819915.205
     3169297.556    13819939.722     3169479.919    13819990.025
     3169619.876    13820012.065     3171091.226     13820429.39
#Sta/Elev= 30
 3102.21   24.51 3223.03   25.37 3469.47   23.87 3845.13   25.23 4049.19   23.16
 4169.65   24.34 4455.67   23.39  4473.6   23.15  4488.4   21.16 4518.79   14.35
 4531.05   13.85 4566.25   12.78 4618.71   14.79 4680.96    8.64 4709.67    7.09
 4905.41   16.36 4965.26    -.41 4966.28    -4.3 5026.93    -4.3 5030.18    2.46
 5094.59   20.35 5245.07   14.41 5304.52   20.48 5346.76   22.93 5483.61   25.06
 5801.51   25.64  5976.3   24.84 6064.03   22.54 6273.52   26.08  6765.9   25.11
#Mann= 5 ,-1 , 0
 3102.21     .15       0 4531.05     .07       0 4905.41     .03       0
 5094.59     .07       0 5483.61     .15       0
#XS Ineff= 2 ,-1
 4401.59 4893.06    15.9 5116.04 5325.37   19.16
Permanent Ineff=
       F       F
Bank Sta=4905.41,5094.59
Exp/Cntr=0.3,0.1

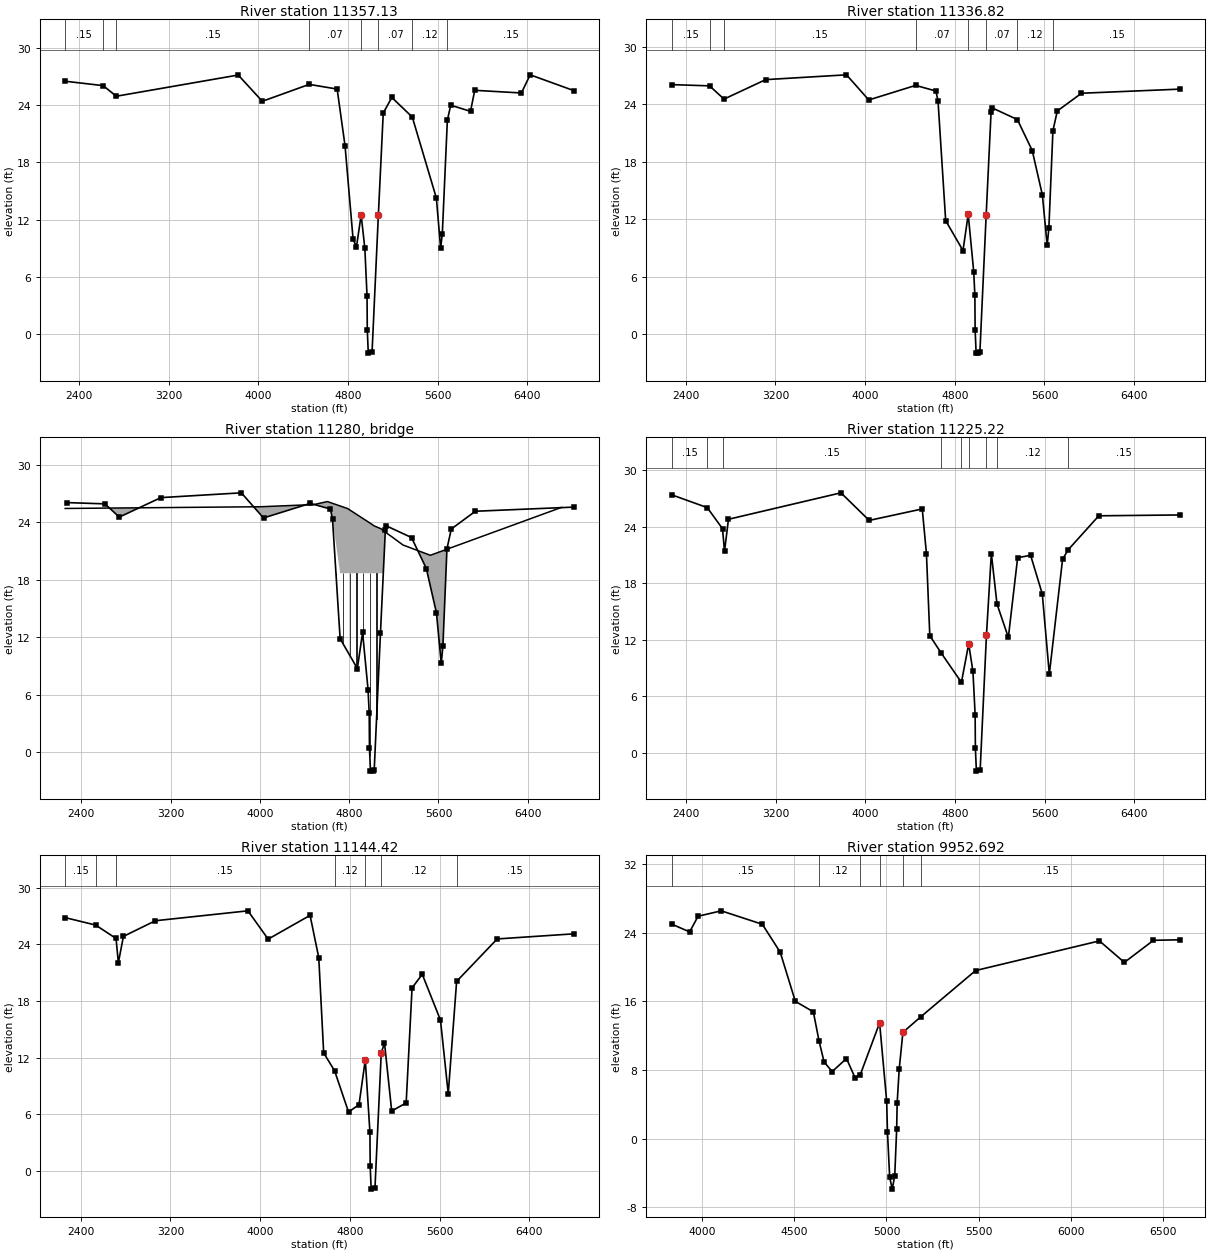
Type RM Length L Ch R = 1 ,11357.13,20.01,20.31,20.01
BEGIN DESCRIPTION:
Harris Road
END DESCRIPTION:
XS GIS Cut Line= 4
     3166619.484    13820590.047     3169187.983    13820682.561
     3169580.566    13820705.654     3171150.605    13820765.685
#Sta/Elev= 30
 2276.96    26.5 2615.14   26.04 2732.98   24.93 3820.44   27.15 4035.18    24.4
 4453.58   26.17 4702.88   25.68 4773.22   19.75 4844.98    9.98 4875.02    9.17
    4917    12.5    4950       9 4969.44    4.06 4971.67     .48 4980.65   -1.95
 5014.31   -1.84 5070.39   12.48 5114.03   23.17 5190.56    24.8  5373.2   22.75
  5588.1   14.27 5625.94    9.03 5640.94   10.53 5685.98   22.42    5716   23.99
  5892.7   23.35 5930.08   25.55 6346.36   25.27 6424.72   27.17 6811.58   25.53
#Mann= 8 ,-1 , 0
 2276.96     .15       0 2615.14     .07       0 2732.98     .15       0
 4453.58     .07       0    4917     .03       0 5070.39     .07       0
  5373.2     .12       0 5685.98     .15       0
#XS Ineff= 1 ,-1
 5339.02 5771.33   21.05
Permanent Ineff=
       F
Bank Sta=4917,5070.39
Exp/Cntr=0.5,0.3

Type RM Length L Ch R = 1 ,11336.82,110.07,111.6,110.08
BEGIN DESCRIPTION:
Harris Road
END DESCRIPTION:
XS GIS Cut Line= 4
     3166618.764    13820610.034     3169187.036     13820702.54
     3169579.597    13820725.632     3171149.841    13820785.671
#Sta/Elev= 30
 2274.72   26.03 2612.52    25.9 2741.66   24.52 3113.66   26.55 3834.18   27.05
 4032.92   24.43 4451.32   25.95 4632.06   25.36 4650.74   24.32    4719   11.85
  4873.5    8.73    4920    12.5 4969.23    6.53 4979.44    4.06 4981.67     .48
 4990.65   -1.95 5011.27   -1.96 5024.31   -1.84 5080.39   12.48 5124.03   23.17
    5134    23.6 5358.24   22.39 5491.06   19.16 5581.62   14.53 5624.42    9.27
 5639.42   11.05 5675.66   21.21 5714.48   23.28  5930.5   25.13  6809.3   25.56
#Mann= 8 ,-1 , 0
 2274.72     .15       0 2612.52     .07       0 2741.66     .15       0
 4451.32     .07       0    4920     .03       0 5080.39     .07       0
 5358.24     .12       0 5675.66     .15       0
#XS Ineff= 1 ,-1
 5445.58 5689.74   19.99
Permanent Ineff=
       F
Bank Sta=4920,5080.39
Exp/Cntr=0.5,0.3

Type RM Length L Ch R = 3 ,11280   ,,,
BEGIN DESCRIPTION:
Bridge at Harris Road
END DESCRIPTION:
Bridge Culvert--1,0,-1,-1, 0
Deck Dist Width WeirC Skew NumUp NumDn MinLoCord MaxHiCord MaxSubmerge Is_Ogee
25,50,2.6,0, 16, 16, , , 0.95, 0, 0,0,,
    2257    4010    4427    4475    4475    4605    4786    4965    5026    5084
    5105    5105    5183    5282    5527    6701
   25.42    25.6    25.8    25.8    25.8   26.14   25.41   24.06   23.59   23.31
    23.1    23.1   22.46   21.61   20.54   25.53
       0       0       0       0   18.67   18.67   18.67   18.67   18.67   18.67
   18.67       0       0       0       0       0
    2257    4010    4427    4475    4475    4605    4786    4965    5026    5084
    5105    5105    5183    5282    5527    6701
   25.42    25.6    25.8    25.8    25.8   26.14   25.41   24.06   23.59   23.31
    23.1    23.1   22.46   21.61   20.54   25.53
       0       0       0       0   18.67   18.67   18.67   18.67   18.67   18.67
   18.67       0       0       0       0       0
Pier Skew, UpSta & Num, DnSta & Num=  ,4565, 2 ,4565, 2 , 0 , 0 , 0 ,,
     2.5     2.5
      -5      19
     2.5     2.5
      -5      19
Pier Skew, UpSta & Num, DnSta & Num=  ,4625, 2 ,4625, 2 , 0 , 0 , 0 ,,
     2.5     2.5
      -5      19
     2.5     2.5
      -5      19
Pier Skew, UpSta & Num, DnSta & Num=  ,4685, 2 ,4685, 2 , 0 , 0 , 0 ,,
     2.5     2.5
      -5      19
     2.5     2.5
      -5      19
Pier Skew, UpSta & Num, DnSta & Num=  ,4745, 2 ,4745, 2 , 0 , 0 , 0 ,,
     2.5     2.5
      -5      19
     2.5     2.5
      -5      19
Pier Skew, UpSta & Num, DnSta & Num=  ,4805, 2 ,4805, 2 , 0 , 0 , 0 ,,
     2.5     2.5
      -5      19
     2.5     2.5
      -5      19
Pier Skew, UpSta & Num, DnSta & Num=  ,4865, 2 ,4865, 2 , 0 , 0 , 0 ,,
     2.5     2.5
      -5      19
     2.5     2.5
      -5      19
Pier Skew, UpSta & Num, DnSta & Num=  ,4925, 2 ,4925, 2 , 0 , 0 , 0 ,,
     2.5     2.5
      -5      19
     2.5     2.5
      -5      19
Pier Skew, UpSta & Num, DnSta & Num=  ,4985, 2 ,4985, 2 , 0 , 0 , 0 ,,
     2.5     2.5
      -5      19
     2.5     2.5
      -5      19
Pier Skew, UpSta & Num, DnSta & Num=  ,5045, 2 ,5045, 2 , 0 , 0 , 0 ,,
     2.5     2.5
      -5      19
     2.5     2.5
      -5      19
BR Coef=-1 , 1 , 1 ,1.25, 0 ,,,0.8,-1,2,0,
WSPro=,,,, 1 ,,,, 0 ,,,, 0 ,,,,-1 ,-1 ,-1 , 0 , 0 , 0 , 0 , 0
BC Design=,, 0 ,, 0 ,,,,,,
BC HTab HWMax=27.05

Type RM Length L Ch R = 1 ,11225.22,80.05,80.8,80.06
BEGIN DESCRIPTION:
Harris Road
END DESCRIPTION:
XS GIS Cut Line= 4
     3166614.804    13820719.963     3169181.826    13820812.424
     3169574.265    13820835.508     3171145.638     13820895.59
#Sta/Elev= 30
  2272.6    27.4    2590   26.04 2726.03    23.8 2743.93   21.39 2779.07    24.8
 3782.32   27.61 4034.76   24.68 4507.79    25.9  4545.1   21.15 4575.11   12.44
 4675.79   10.61 4857.16    7.48    4922   11.56    4960    8.64 4979.44    4.06
 4981.67     .48 4990.65   -1.95 5024.31   -1.84 5080.39   12.48 5124.03   21.16
 5174.57    15.8 5275.79   12.25 5358.61   20.72  5474.4   20.97 5578.52   16.87
 5641.26    8.36  5759.5   20.55 5809.37   21.56 6082.67   25.17 6806.92   25.26
#Mann= 9 ,-1 , 0
  2272.6     .15       0    2590     .07       0 2726.03     .15       0
 4675.79     .12       0 4857.16     .07       0    4922     .03       0
 5080.39     .07       0 5174.57     .12       0 5809.37     .15       0
#XS Ineff= 1 ,-1
 5133.12 5767.88      20
Permanent Ineff=
       F
Bank Sta=4922,5080.39
Exp/Cntr=0.5,0.3

Type RM Length L Ch R = 1 ,11144.42,1194.5,1191.73,1184.43
BEGIN DESCRIPTION:
Harris Road
END DESCRIPTION:
XS GIS Cut Line= 4
     3166611.925    13820799.911     3169178.037    13820892.339
     3169570.388    13820915.419     3171142.581    13820975.532
#Sta/Elev= 30
 2261.37   26.83 2533.42   26.04 2714.78   24.62 2735.58   22.05 2780.61   24.84
 3065.79    26.5 3891.33   27.55 4071.45   24.55 4445.45   27.07 4523.11   22.58
 4566.85   12.49 4664.47   10.59 4788.35    6.23 4882.03       7    4938   11.75
 4979.44    4.06 4981.67     .48 4990.65   -1.95 5024.31   -1.84 5080.39   12.48
 5109.37   13.55 5173.56    6.33 5302.67    7.19 5355.15   19.38 5446.21   20.82
 5608.73   15.96 5677.95    8.16 5752.66   20.07 6114.63   24.57 6795.52   25.11
#Mann= 7 ,-1 , 0
 2261.37     .15       0 2533.42     .07       0 2714.78     .15       0
 4664.47     .12       0    4938     .03       0 5080.39     .12       0
 5752.66     .15       0
#XS Ineff= 1 ,-1
 5441.41 5839.59   20.53
Permanent Ineff=
       F
Bank Sta=4938,5080.39
Exp/Cntr=0.3,0.1

Type RM Length L Ch R = 1 ,9952.692,1264.69,1277.96,1266.24
XS GIS Cut Line= 6
     3168256.472    13822063.648     3169311.556     13822081.92
     3169354.061    13822083.567     3169504.457    13822090.517
     3170009.234    13822123.318     3171007.645    13822179.081
#Sta/Elev= 30
 3836.38   25.03 3933.64   24.12 3979.44   25.95 4105.16   26.58 4327.56   25.01
  4424.5   21.75  4506.3   16.02 4603.92   14.79 4635.08   11.37 4662.04    8.95
 4705.86    7.82 4783.52    9.34    4830     7.1 4857.98    7.44    4963    13.5
 5001.35    4.33 5005.52     .75 5017.61   -4.53 5031.44    -5.9 5044.95   -4.34
 5055.37    1.07 5058.06    4.15  5069.1     8.1 5089.24    12.4  5185.9   14.21
 5483.14   19.61 6154.02   23.07 6289.08   20.56 6446.84   23.14 6590.52    23.2
#Mann= 6 ,-1 , 0
 3836.38     .15       0 4635.08     .12       0 4857.98     .07       0
    4963     .03       0 5089.24     .12       0  5185.9     .15       0
Bank Sta=4963,5089.24
Exp/Cntr=0.3,0.1

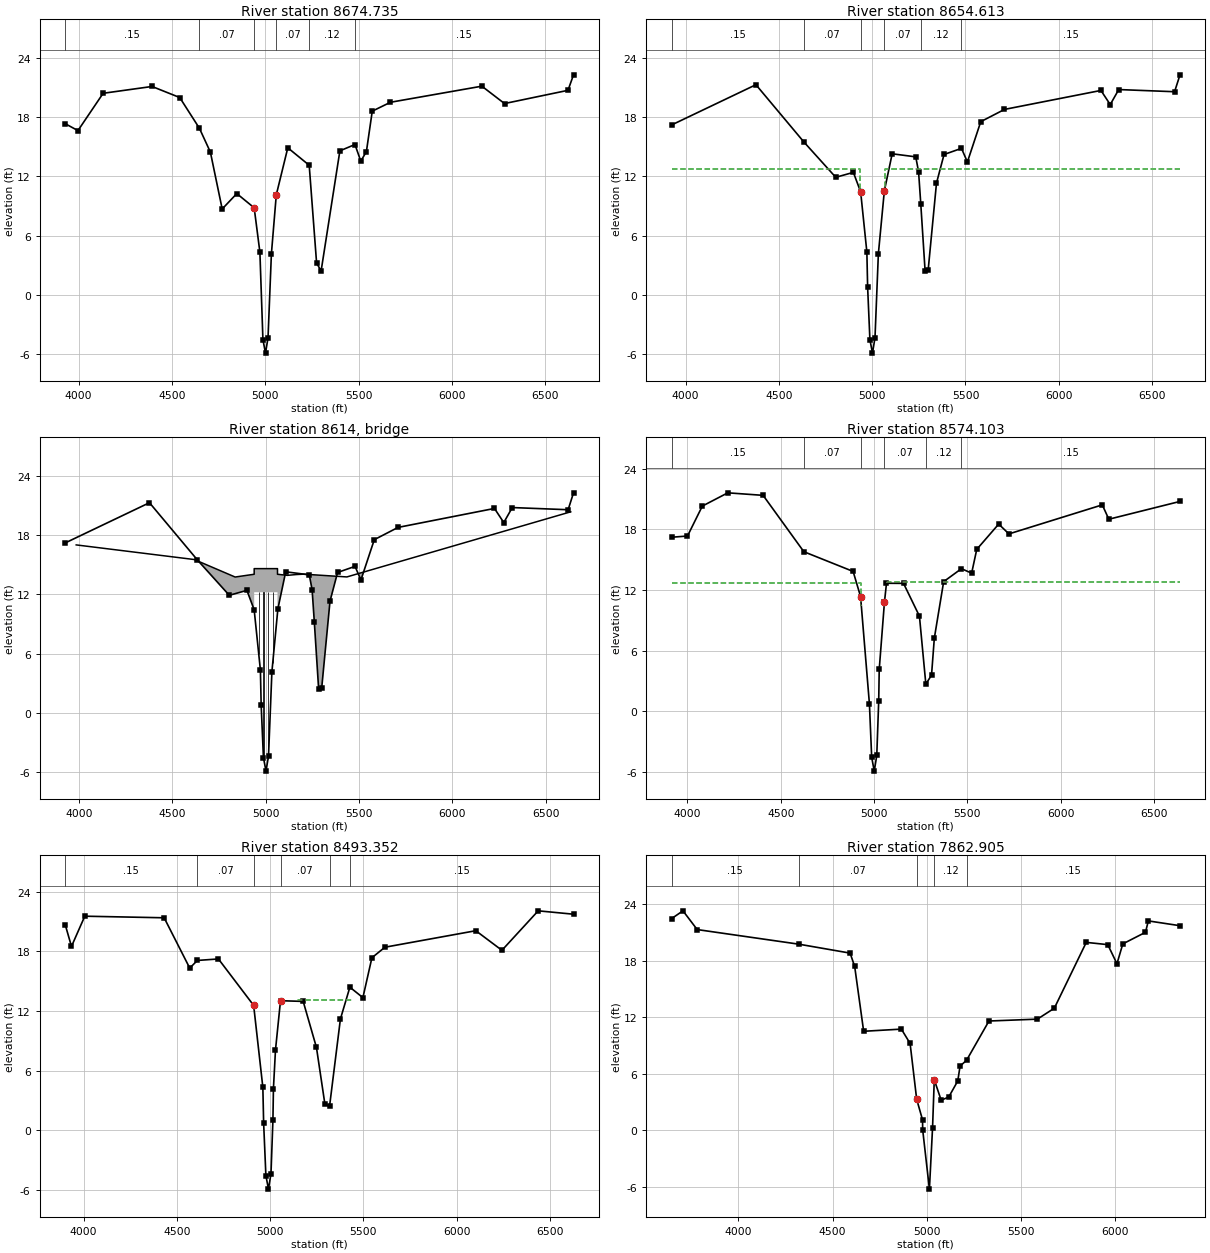
Type RM Length L Ch R = 1 ,8674.735,20.05,20.12,20.51
BEGIN DESCRIPTION:
Jackson Street
END DESCRIPTION:
XS GIS Cut Line= 6
     3168247.571    13823311.096     3169110.458    13823343.219
     3169207.471    13823349.476     3169436.756    13823359.858
     3169545.987    13823362.437     3170970.557    13823410.475
#Sta/Elev= 30
 3927.76   17.34 3996.06   16.64 4131.12   20.42  4393.3   21.11  4541.7   19.99
 4647.32   16.87 4705.98   14.46 4769.26     8.7 4847.58   10.26 4940.76    8.82
 4971.35    4.33 4987.61   -4.53 5001.44    -5.9 5014.95   -4.34    5033    4.15
 5059.24   10.13 5120.94    14.9  5235.7   13.13  5275.3    3.23 5299.52    2.42
 5400.14   14.59 5480.94   15.23 5512.24   13.55 5542.26   14.51  5573.7   18.61
  5671.3   19.51 6161.26   21.14  6282.6   19.38 6622.88   20.72 6652.62   22.29
#Mann= 6 ,-1 , 0
 3927.76     .15       0 4647.32     .07       0 4940.76     .03       0
 5059.24     .07       0  5235.7     .12       0 5480.94     .15       0
#XS Ineff= 1 ,-1
    5130    5550      14
Permanent Ineff=
       F
Bank Sta=4940.76,5059.24
Exp/Cntr=0.5,0.3

Type RM Length L Ch R = 1 ,8654.613,80.21,80.51,82.04
BEGIN DESCRIPTION:
Jackson Street
END DESCRIPTION:
XS GIS Cut Line= 6
     3168246.827    13823331.082     3169109.442    13823363.195
     3169206.375    13823369.447     3169436.067    13823379.847
     3169545.413    13823382.429     3170969.883    13823430.464
#Sta/Elev= 30
 3925.02   17.19 4376.68   21.26  4633.5   15.47 4804.64   11.89    4899   12.39
    4938   10.42 4971.35    4.33 4975.52     .75 4987.61   -4.53 5001.44    -5.9
 5014.95   -4.34    5033    4.15    5065   10.51    5107   14.27 5233.42   13.96
  5248.6   12.45 5260.24    9.23 5283.46    2.43 5300.12    2.54 5344.54    11.3
 5385.08    14.2 5478.58   14.82 5510.24   13.44  5581.9   17.52 5709.04   18.76
 6226.08   20.68    6276   19.25 6321.56   20.77 6620.88   20.55 6649.94   22.26
#Mann= 6 ,-1 , 0
 3925.02     .15       0  4633.5     .07       0    4938     .03       0
    5065     .07       0 5260.24     .12       0 5478.58     .15       0
#XS Ineff= 2 , 0
       0    4932    12.7    5069       0   12.76
Permanent Ineff=
       F       F
Bank Sta=4938,5065
Exp/Cntr=0.5,0.3

Type RM Length L Ch R = 3 ,8614    ,,,
BEGIN DESCRIPTION:
Bridge at Jackson Street
END DESCRIPTION:
Bridge Culvert--1,0,-1,-1, 0
Deck Dist Width WeirC Skew NumUp NumDn MinLoCord MaxHiCord MaxSubmerge Is_Ogee
6,48,2.6,0, 17, 17, , , 0.95, 0, 0,0,,
    3984    4617    4836    4883    4938    4938    4963    4988    5013    5038
    5063    5063    5116    5163    5204    5435    6635
   16.99   15.51   13.74   13.87   14.02   14.59   14.59   14.59   14.59   14.59
   14.59   14.02   13.91   13.99   14.03   13.75   20.34
       0       0       0       0       0    12.2    12.2    12.2    12.2    12.2
    12.2       0       0       0       0       0       0
    3984    4617    4836    4883    4938    4938    4963    4988    5013    5038
    5063    5063    5116    5163    5204    5435    6635
   16.99   15.51   13.74   13.87   14.02   14.59   14.59   14.59   14.59   14.59
   14.59   14.02   13.91   13.99   14.03   13.75   20.34
       0       0       0       0       0    12.2    12.2    12.2    12.2    12.2
    12.2       0       0       0       0       0       0
Pier Skew, UpSta & Num, DnSta & Num=  ,4962.5, 4 ,4962.5, 4 , 3 , 3 , 0 ,,
     1.2     1.2       2       2
     -10    10.2    10.2      13
     1.2     1.2       2       2
     -10    10.2    10.2      13
Pier Skew, UpSta & Num, DnSta & Num=  ,4987.5, 4 ,4987.5, 4 , 3 , 3 , 0 ,,
     1.2     1.2       2       2
     -10    10.2    10.2      13
     1.2     1.2       2       2
     -10    10.2    10.2      13
Pier Skew, UpSta & Num, DnSta & Num=  ,5012.5, 4 ,5012.5, 4 , 3 , 3 , 0 ,,
     1.2     1.2       2       2
     -10    10.2    10.2      13
     1.2     1.2       2       2
     -10    10.2    10.2      13
Pier Skew, UpSta & Num, DnSta & Num=  ,5037.5, 4 ,5037.5, 4 , 3 , 3 , 0 ,,
     1.2     1.2       2       2
     -10    10.2    10.2      13
     1.2     1.2       2       2
     -10    10.2    10.2      13
BR Coef=-1 , 1 , 1 ,1.25, 0 ,,,0.8,0,2,0,
WSPro=,,,, 1 ,,,, 0 ,,,, 0 ,,,,-1 ,-1 ,-1 , 0 , 0 , 0 , 0 , 0
BC Design=,, 0 ,, 0 ,,,,,,
BC HTab HWMax=22.26

Type RM Length L Ch R = 1 ,8574.103,80.24,80.75,82.04
BEGIN DESCRIPTION:
Jackson Street
END DESCRIPTION:
XS GIS Cut Line= 6
     3168243.851    13823411.027     3169105.379    13823443.099
      3169201.99    13823449.331     3169433.314    13823459.805
     3169543.121    13823462.397     3170967.187    13823510.418
#Sta/Elev= 30
 3915.36   17.22 4000.18   17.34  4079.7    20.3 4216.28   21.61 4405.62   21.36
 4623.92   15.79 4888.16   13.84    4928   11.36 4975.52     .75 4987.61   -4.53
 5001.44    -5.9 5014.95   -4.34 5025.37    1.07 5028.06    4.15    5056   10.79
    5067   12.67  5158.4   12.66 5243.64    9.42 5277.98     2.7 5308.46    3.59
 5323.46    7.24 5373.52   12.83 5468.74   14.11 5523.56   13.67 5550.92   16.02
  5668.6   18.52 5723.46   17.55 6223.98   20.42 6259.02      19 6640.58   20.76
#Mann= 6 ,-1 , 0
 3915.36     .15       0 4623.92     .07       0    4928     .03       0
    5056     .07       0 5277.98     .12       0 5468.74     .15       0
#XS Ineff= 2 , 0
       0    4932    12.7    5069       0   12.76
Permanent Ineff=
       F       F
Bank Sta=4928,5056
Exp/Cntr=0.5,0.3

Type RM Length L Ch R = 1 ,8493.352,671.22,630.45,531.29
BEGIN DESCRIPTION:
Jackson Street
END DESCRIPTION:
XS GIS Cut Line= 6
     3168240.875    13823490.971     3169101.315    13823523.003
     3169197.606    13823529.214      3169430.56    13823539.762
     3169540.829    13823542.366     3170964.491    13823590.373
#Sta/Elev= 30
 3901.63    20.7 3935.24   18.51 4006.65   21.55 4432.17   21.39 4569.34   16.33
 4610.26    17.1 4723.11   17.25    4912   12.58 4961.35    4.33 4965.52     .75
 4977.61   -4.53 4991.44    -5.9 5004.95   -4.34 5015.37    1.07 5018.06    4.21
  5029.1     8.1    5056   13.05 5177.64   12.98 5248.71    8.35 5294.07    2.64
 5318.89    2.42  5377.2   11.21  5427.9   14.41 5497.75   13.36 5546.04   17.37
 5615.74   18.43 6103.13   20.09 6243.24   18.12  6437.7   22.09 6627.12   21.75
#Mann= 6 ,-1 , 0
 3901.63     .15       0 4610.26     .07       0    4912     .03       0
    5056     .07       0 5318.89     .12       0  5427.9     .15       0
#XS Ineff= 1 ,-1
 5149.93 5441.87   13.15
Permanent Ineff=
       F
Bank Sta=4912,5056
Exp/Cntr=0.3,0.1

Type RM Length L Ch R = 1 ,7862.905,227.95,431.49,533.32
XS GIS Cut Line= 5
     3168241.001    13824230.328     3169351.545    13824170.429
     3169513.613    13824135.544     3169655.259    13824083.699
     3170912.356    13823913.861
#Sta/Elev= 30
 3645.96   22.46 3705.87   23.28 3781.36   21.29 4320.28   19.74 4592.83   18.79
 4617.03   17.37 4664.68   10.49 4864.79   10.72 4911.09     9.2    4946    3.27
 4977.15    1.08 4977.83     .04 5013.56   -6.27 5030.12     .19 5039.37    5.34
    5076    3.17 5116.13    3.51 5164.09    5.22 5176.22     6.8 5210.39     7.4
 5329.49   11.58 5586.54   11.78 5676.39   12.94 5845.87   19.93 5960.05   19.69
 6008.71   17.66 6039.79   19.77 6160.07      21 6175.21   22.21 6343.25    21.7
#Mann= 5 ,-1 , 0
 3645.96     .15       0 4320.28     .07       0    4946     .03       0
 5039.37     .12       0 5210.39     .15       0
Bank Sta=4946,5039.37
Exp/Cntr=0.3,0.1

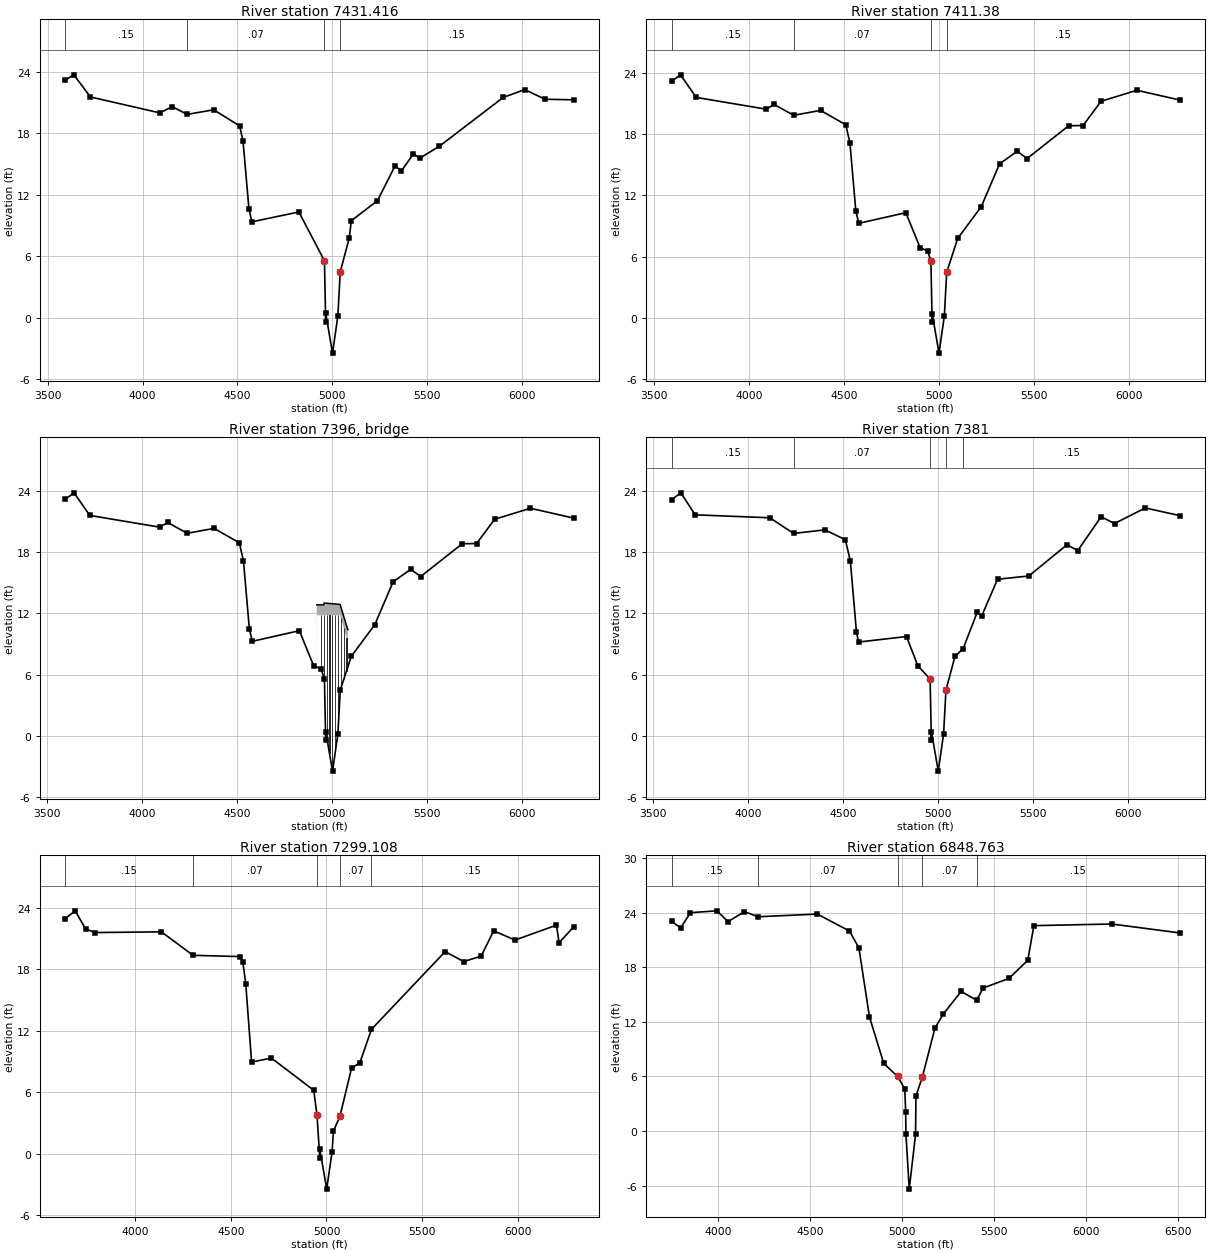
Type RM Length L Ch R = 1 ,7431.416,21.77,20.04,20
BEGIN DESCRIPTION:
Footbridge
END DESCRIPTION:
XS GIS Cut Line= 6
     3168255.428    13824335.277     3169016.119    13824376.186
      3169579.61    13824523.664     3169706.809    13824554.314
     3170002.157    13824618.921     3170885.354    13824795.375
#Sta/Elev= 30
 3592.64    23.2  3638.1   23.72  3725.8   21.56 4090.78   20.01 4156.84   20.61
  4235.4   19.86 4374.78   20.31 4511.32   18.74 4529.58   17.26 4560.54   10.65
 4576.02    9.38 4823.72   10.34  4958.4    5.58 4964.95    -.36  4965.3     .44
 5001.07   -3.43 5029.17      .2  5041.6    4.49    5089    7.79    5100    9.49
 5237.72   11.44 5330.78   14.85 5363.56   14.33 5427.46   16.02 5459.76   15.58
 5563.22   16.74 5899.82   21.51 6013.54   22.28 6120.26   21.34 6270.78   21.28
#Mann= 4 ,-1 , 0
 3592.64     .15       0  4235.4     .07       0  4958.4     .03       0
  5041.6     .15       0
Bank Sta=4958.4,5041.6
Exp/Cntr=0.5,0.3

Type RM Length L Ch R = 1 ,7411.38 ,32.46,30.38,30
BEGIN DESCRIPTION:
Footbridge
END DESCRIPTION:
XS GIS Cut Line= 6
     3168254.354    13824355.248     3169013.082    13824396.051
     3169574.487    13824543.002     3169702.329    13824573.807
     3169998.061    13824638.498     3170881.436    13824814.987
#Sta/Elev= 30
 3594.16   23.17  3640.7    23.8 3723.44   21.59 4091.34   20.44  4133.3    20.9
 4236.22   19.84 4377.46   20.32  4510.3   18.92 4532.26   17.14 4563.22    10.5
  4578.7    9.27 4826.44   10.31 4902.17    6.86 4940.72    6.59  4958.4    5.58
 4964.95    -.36  4965.3     .44 5001.07   -3.43 5029.17      .2  5041.6    4.49
 5099.42    7.79 5223.66   10.91 5319.92   15.09 5412.74   16.32 5465.04   15.61
 5683.68   18.82 5759.14   18.84 5853.92   21.21 6042.16   22.29  6269.4   21.33
#Mann= 4 ,-1 , 0
 3594.16     .15       0 4236.22     .07       0  4958.4     .03       0
  5041.6     .15       0
Bank Sta=4958.4,5041.6
Exp/Cntr=0.5,0.3

Type RM Length L Ch R = 3 ,7396    ,,,
BEGIN DESCRIPTION:
Footbridge
END DESCRIPTION:
Bridge Culvert--1,0,-1,-1, 0
Deck Dist Width WeirC Skew NumUp NumDn MinLoCord MaxHiCord MaxSubmerge Is_Ogee
10,10,2.6,0, 7, 7, , , 0.95, 0, 0,0,,
    4918    4919    4955    4957    5041    5081    5082
   12.84   12.84   12.84   13.02   12.88   10.42   10.42
       0   11.82   11.82   11.82   11.82    9.25       0
    4918    4919    4955    4957    5041    5081    5082
   12.84   12.84   12.84   13.02   12.88   10.42   10.42
       0   11.82   11.82   11.82   11.82    9.25       0
Pier Skew, UpSta & Num, DnSta & Num=  ,4940, 2 ,4940, 2 , 0 , 0 , 0 ,,
       1       1
      -5      12
       1       1
      -5      12
Pier Skew, UpSta & Num, DnSta & Num=  ,4955, 2 ,4955, 2 , 0 , 0 , 0 ,,
       1       1
      -5      12
       1       1
      -5      12
Pier Skew, UpSta & Num, DnSta & Num=  ,4970, 2 ,4970, 2 , 0 , 0 , 0 ,,
       1       1
      -5      12
       1       1
      -5      12
Pier Skew, UpSta & Num, DnSta & Num=  ,4985, 2 ,4985, 2 , 0 , 0 , 0 ,,
       1       1
      -5      12
       1       1
      -5      12
Pier Skew, UpSta & Num, DnSta & Num=  ,5000, 2 ,5000, 2 , 0 , 0 , 0 ,,
       1       1
      -5      12
       1       1
      -5      12
Pier Skew, UpSta & Num, DnSta & Num=  ,5015, 2 ,5015, 2 , 0 , 0 , 0 ,,
       1       1
      -5      12
       1       1
      -5      12
Pier Skew, UpSta & Num, DnSta & Num=  ,5030, 2 ,5030, 2 , 0 , 0 , 0 ,,
       1       1
      -5      12
       1       1
      -5      12
Pier Skew, UpSta & Num, DnSta & Num=  ,5045, 2 ,5045, 2 , 0 , 0 , 0 ,,
       1       1
      -5      12
       1       1
      -5      12
Pier Skew, UpSta & Num, DnSta & Num=  ,5060, 2 ,5060, 2 , 0 , 0 , 0 ,,
       1       1
      -5      12
       1       1
      -5      12
Pier Skew, UpSta & Num, DnSta & Num=  ,5075, 2 ,5075, 2 , 0 , 0 , 0 ,,
       1       1
      -5      12
       1       1
      -5      12
BR Coef=-1 , 1 , 1 ,0.9, 0 ,,,0.8,-1,1.2,0,
WSPro=,,,, 1 ,,,, 0 ,,,, 0 ,,,,-1 ,-1 ,-1 , 0 , 0 , 0 , 0 , 0
BC Design=,, 0 ,, 0 ,,,,,,
BC HTab HWMax=23.8

Type RM Length L Ch R = 1 ,7381    ,81.27,81.89,80.01
BEGIN DESCRIPTION:
Footbridge
END DESCRIPTION:
XS GIS Cut Line= 6
     3168252.743    13824385.205     3169008.527    13824425.849
     3169566.803    13824572.009     3169695.609    13824603.046
     3169991.916    13824667.864     3170875.558    13824844.406
#Sta/Elev= 30
 3600.44   23.12 3648.58   23.78 3723.92   21.63  4115.8   21.34 4241.46   19.81
 4405.16   20.16 4512.78    19.2 4539.22   17.12 4571.24   10.19 4582.48    9.19
 4834.54    9.73    4894    6.86  4958.4    5.58 4964.95    -.36  4965.3     .44
 5001.07   -3.43 5029.17      .2  5041.6    4.49    5089    7.79    5132    8.55
 5205.44   12.08 5229.84   11.76 5312.84   15.33    5477   15.65 5677.44    18.7
 5734.26   18.14 5856.84   21.44 5927.28   20.78  6089.1    22.3 6271.36   21.55
#Mann= 5 ,-1 , 0
 3600.44     .15       0 4241.46     .07       0  4958.4     .03       0
  5041.6     .07       0    5132     .15       0
Bank Sta=4958.4,5041.6
Exp/Cntr=0.5,0.3

Type RM Length L Ch R = 1 ,7299.108,409.87,450.35,422.11
BEGIN DESCRIPTION:
Footbridge
END DESCRIPTION:
XS GIS Cut Line= 6
     3168248.447    13824465.089      3168996.38    13824505.312
     3169546.311    13824649.361     3169677.689    13824681.018
      3169975.53    13824746.171     3170859.885    13824922.856
#Sta/Elev= 30
 3633.06   22.97 3685.52   23.72 3739.56   21.95 3790.88    21.6 4136.18   21.67
 4301.78   19.38 4545.14   19.26  4562.1   18.77 4577.58   16.62 4608.18    8.96
 4711.82    9.36 4933.32    6.21    4950    3.84 4964.95    -.36  4965.3     .44
 5001.07   -3.43 5029.17      .2 5036.42    2.23    5070    3.66    5131    8.36
    5175    8.91 5235.28   12.16 5620.76   19.74 5718.06   18.77 5809.18    19.3
  5874.7   21.77 5986.26   20.87 6203.14   22.32 6217.14   20.61 6292.46   22.14
#Mann= 5 ,-1 , 0
 3633.06     .15       0 4301.78     .07       0    4950     .03       0
    5070     .07       0 5235.28     .15       0
Bank Sta=4950,5070
Exp/Cntr=0.3,0.1

Type RM Length L Ch R = 1 ,6848.763,10.04,10.03,10
BEGIN DESCRIPTION:
Footbridge
END DESCRIPTION:
XS GIS Cut Line= 5
     3168206.922    13824591.057     3169194.915    13825012.758
     3169539.893    13825099.071      3169906.95    13825147.013
     3170857.626     13825300.46
#Sta/Elev= 30
 3746.98   23.06 3796.02   22.34 3849.08   24.02 3992.72   24.22 4053.48   23.03
 4142.65   24.13 4216.69   23.57 4538.66   23.86 4713.37      22  4764.7   20.14
 4822.12   12.54 4899.79    7.44 4974.88       6 5013.91    4.64 5018.94     2.1
  5020.3     -.3  5038.2   -6.39 5072.69    -.37 5074.73    3.84 5110.21    5.98
 5177.88   11.32 5224.26   12.89 5320.27   15.35 5404.78   14.39 5439.97   15.73
 5580.47   16.79  5682.6   18.78 5715.78   22.59 6138.43   22.77 6509.97   21.79
#Mann= 5 ,-1 , 0
 3746.98     .15       0 4216.69     .07       0 4974.88     .03       0
 5110.21     .07       0 5404.78     .15       0
Bank Sta=4974.88,5110.21
Exp/Cntr=0.5,0.3