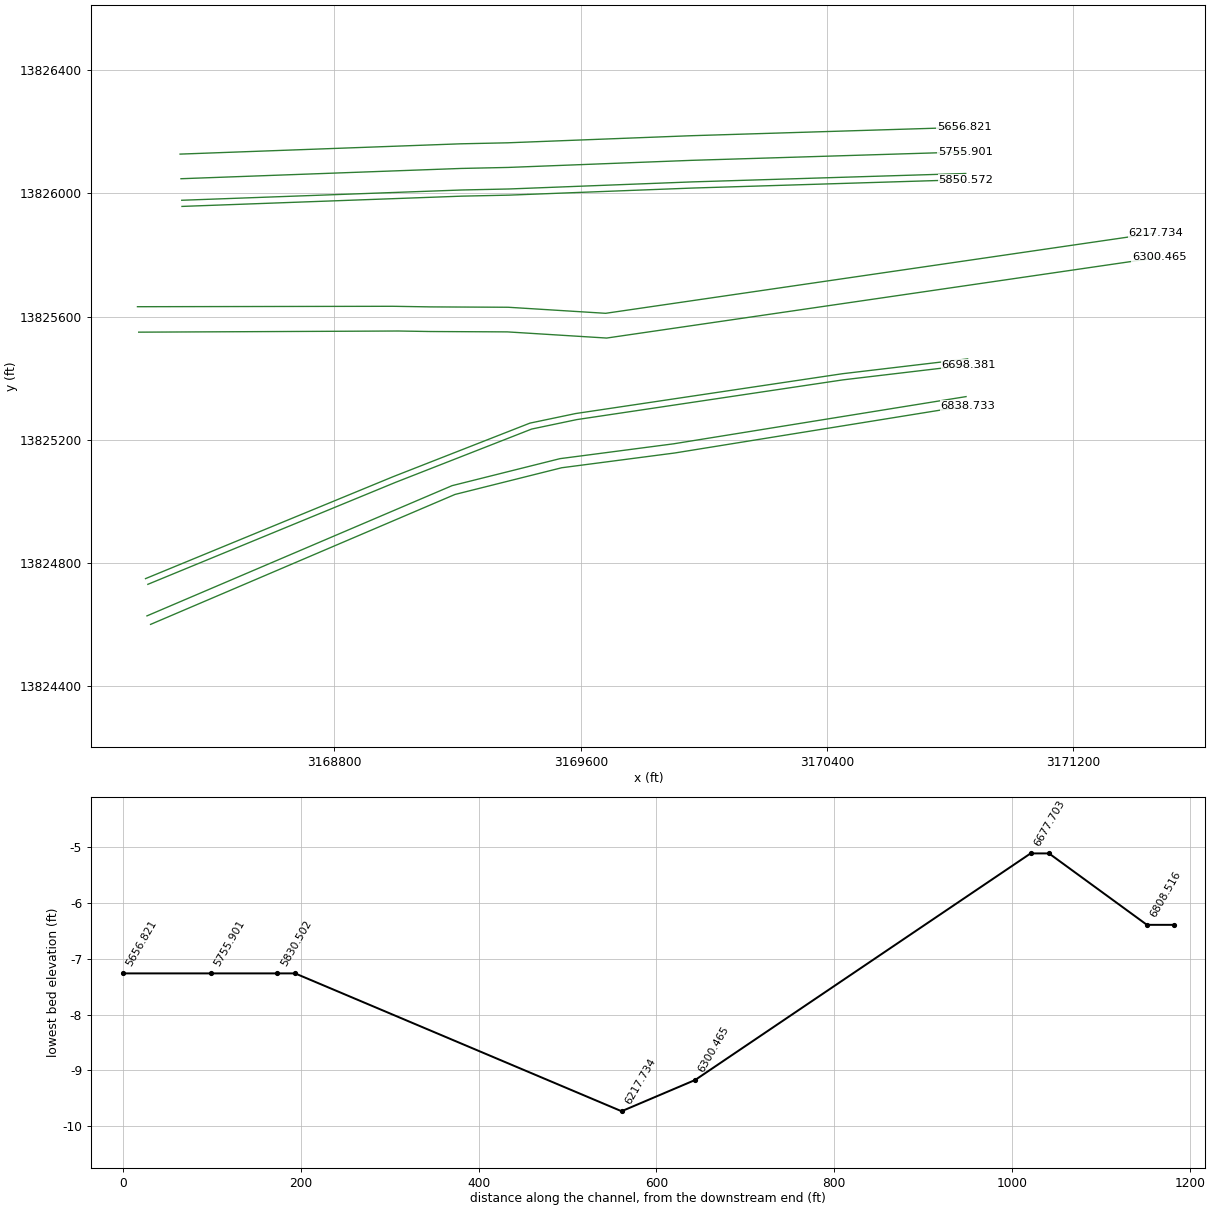
HEC-RAS study I100-00-00.prj: I100-00-00

--- I100-00-00.g01 (geometry) --- (continued)

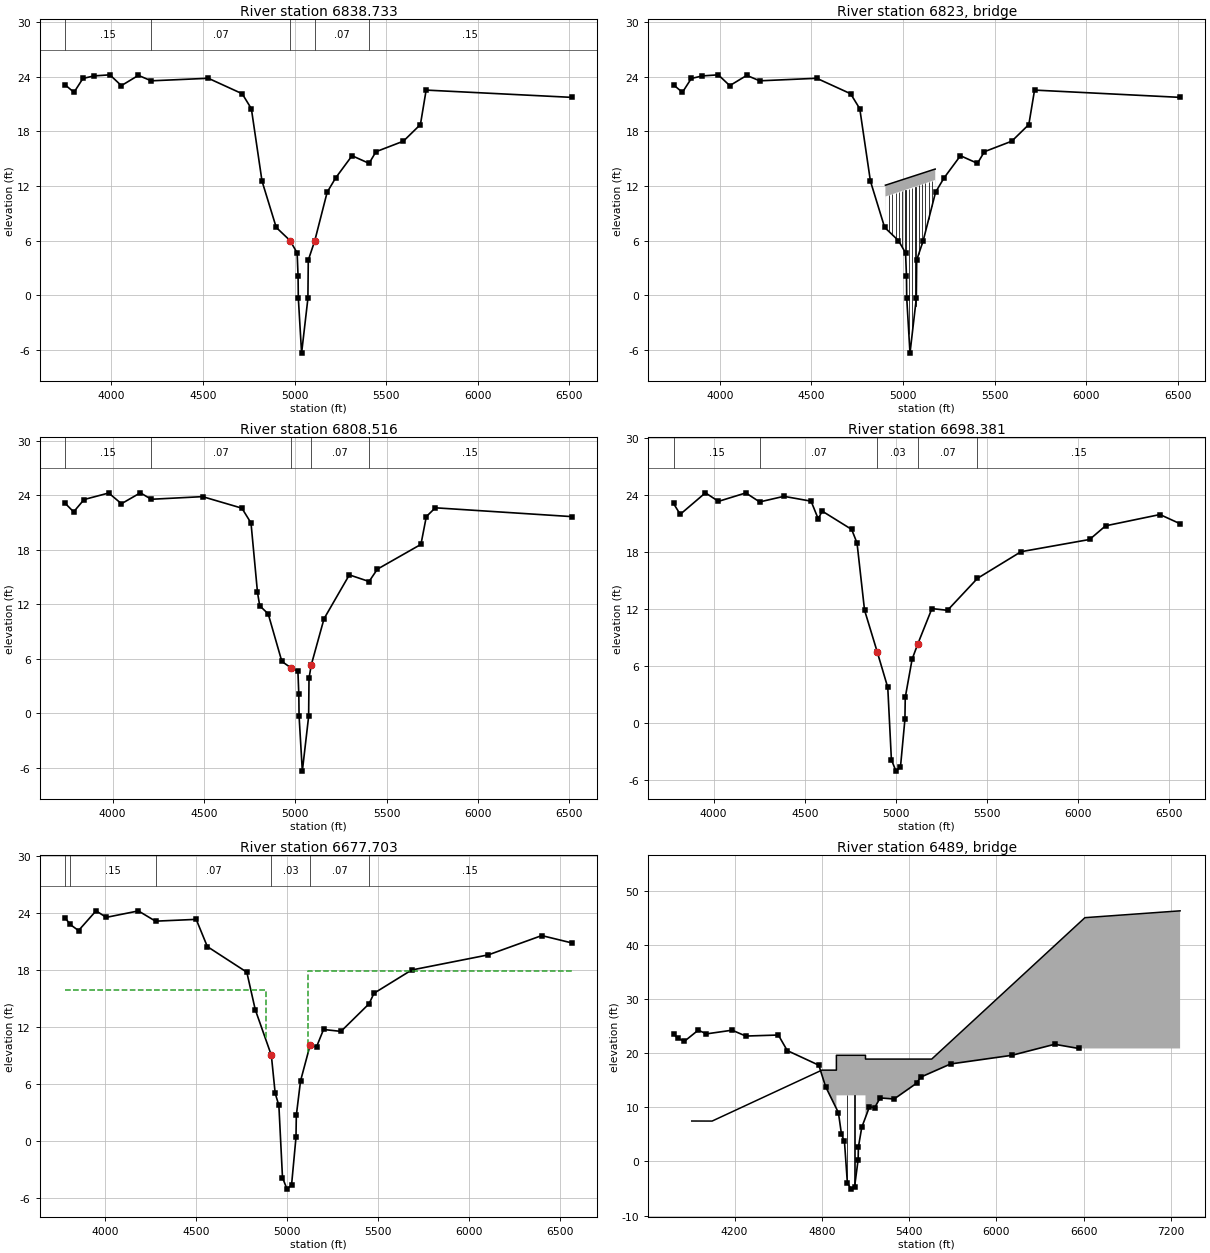
Type RM Length L Ch R = 1 ,6838.733,30.03,30.22,30.01
BEGIN DESCRIPTION:
Footbridge
END DESCRIPTION:
XS GIS Cut Line= 5
     3168202.996    13824600.255     3169191.718    13825022.266
     3169538.026    13825108.912     3169905.506     13825156.91
     3170856.033    13825310.332
#Sta/Elev= 30
 3747.26   23.13 3795.69    22.3 3844.37   23.83 3904.72   24.11 3991.62   24.23
 4054.21   23.04  4147.2   24.17 4217.38   23.57 4529.11   23.85 4713.88   22.15
 4764.03    20.5 4822.12   12.54 4899.79    7.44 4974.88       6 5013.91    4.64
 5018.94     2.1  5020.3     -.3  5038.2   -6.39 5072.69    -.37 5074.73    3.84
 5110.21    5.98 5177.88   11.32 5224.26   12.89 5313.67   15.33 5406.52   14.49
 5444.29   15.77 5593.93   16.93 5686.94   18.76 5718.13   22.55 6512.69   21.75
#Mann= 5 ,-1 , 0
 3747.26     .15       0 4217.38     .07       0 4974.88     .03       0
 5110.21     .07       0 5406.52     .15       0
Bank Sta=4974.88,5110.21
Exp/Cntr=0.5,0.3

Type RM Length L Ch R = 3 ,6823    ,,,
BEGIN DESCRIPTION:
Footbridge
END DESCRIPTION:
Bridge Culvert--1,0,-1,-1, 0
Deck Dist Width WeirC Skew NumUp NumDn MinLoCord MaxHiCord MaxSubmerge Is_Ogee
10,10,2.6,0, 4, 4, , , 0.95, 0, 0,0,,
    4904    4905    5175    5176
   12.09   12.09   13.86   13.86
       0   10.85   12.66       0
    4904    4905    5175    5176
   12.09   12.09   13.86   13.86
       0   10.85   12.66       0
Pier Skew, UpSta & Num, DnSta & Num=  ,4924, 2 ,4924, 2 , 0 , 0 , 0 ,,
       1       1
     -10      13
       1       1
     -10      13
Pier Skew, UpSta & Num, DnSta & Num=  ,4942, 2 ,4942, 2 , 0 , 0 , 0 ,,
       1       1
     -10      13
       1       1
     -10      13
Pier Skew, UpSta & Num, DnSta & Num=  ,4960, 2 ,4960, 2 , 0 , 0 , 0 ,,
       1       1
     -10      13
       1       1
     -10      13
Pier Skew, UpSta & Num, DnSta & Num=  ,4978, 2 ,4978, 2 , 0 , 0 , 0 ,,
       1       1
     -10      13
       1       1
     -10      13
Pier Skew, UpSta & Num, DnSta & Num=  ,4996, 2 ,4996, 2 , 0 , 0 , 0 ,,
       1       1
     -10      13
       1       1
     -10      13
Pier Skew, UpSta & Num, DnSta & Num=  ,5014, 2 ,5014, 2 , 0 , 0 , 0 ,,
       1       1
     -10      13
       1       1
     -10      13
Pier Skew, UpSta & Num, DnSta & Num=  ,5032, 2 ,5032, 2 , 0 , 0 , 0 ,,
       1       1
     -10      13
       1       1
     -10      13
Pier Skew, UpSta & Num, DnSta & Num=  ,5050, 2 ,5050, 2 , 0 , 0 , 0 ,,
       1       1
     -10      13
       1       1
     -10      13
Pier Skew, UpSta & Num, DnSta & Num=  ,5068, 2 ,5068, 2 , 0 , 0 , 0 ,,
       1       1
     -10      13
       1       1
     -10      13
Pier Skew, UpSta & Num, DnSta & Num=  ,5086, 2 ,5086, 2 , 0 , 0 , 0 ,,
       1       1
     -10      13
       1       1
     -10      13
Pier Skew, UpSta & Num, DnSta & Num=  ,5104, 2 ,5104, 2 , 0 , 0 , 0 ,,
       1       1
     -10      13
       1       1
     -10      13
Pier Skew, UpSta & Num, DnSta & Num=  ,5122, 2 ,5122, 2 , 0 , 0 , 0 ,,
       1       1
     -10      13
       1       1
     -10      13
Pier Skew, UpSta & Num, DnSta & Num=  ,5140, 2 ,5140, 2 , 0 , 0 , 0 ,,
       1       1
     -10      13
       1       1
     -10      13
Pier Skew, UpSta & Num, DnSta & Num=  ,5158, 2 ,5158, 2 , 0 , 0 , 0 ,,
       1       1
     -10      13
       1       1
     -10      13
BR Coef=-1 , 1 , 1 ,0.9, 0 ,,,0.8,-1,1.2,0,
WSPro=,,,, 1 ,,,, 0 ,,,, 0 ,,,,-1 ,-1 ,-1 , 0 , 0 , 0 , 0 , 0
BC Design=,, 0 ,, 0 ,,,,,,
BC HTab HWMax=24.23

Type RM Length L Ch R = 1 ,6808.516,82.79,110.14,120.81
BEGIN DESCRIPTION:
Footbridge
END DESCRIPTION:
XS GIS Cut Line= 5
     3168191.219    13824627.846     3169182.129    13825050.792
     3169532.424    13825138.435     3169901.172    13825186.598
     3170851.253    13825339.949
#Sta/Elev= 30
 3739.78   23.12 3786.42   22.17 3843.38   23.53 3978.48   24.25 4048.08   23.07
 4151.78   24.27 4211.16   23.56 4492.16   23.85 4707.28   22.58 4757.24   20.95
 4792.76    13.3  4804.9   11.83 4851.48   10.93    4926     5.7 4974.88       5
 5013.91    4.64 5018.94     2.1  5020.3     -.3  5038.2   -6.39 5072.69    -.37
 5074.73    3.84    5087     5.3    5157    10.4 5295.48   15.23 5403.44    14.5
 5448.96   15.86 5687.42   18.59 5716.84   21.65 5766.14   22.62 6512.54   21.65
#Mann= 5 ,-1 , 0
 3739.78     .15       0 4211.16     .07       0 4974.88     .03       0
    5087     .07       0 5403.44     .15       0
Bank Sta=4974.88,5087
Exp/Cntr=0.5,0.3

Type RM Length L Ch R = 1 ,6698.381,20.01,20.68,20
BEGIN DESCRIPTION:
Hwy 225
END DESCRIPTION:
XS GIS Cut Line= 6
     3168194.161    13824730.359     3168998.724     13825061.59
     3169440.639    13825234.618     3169586.968    13825265.285
     3170452.101    13825394.421     3170858.714    13825442.546
#Sta/Elev= 30
 3780.31   23.12 3816.93   21.97 3955.24   24.24  4026.8   23.34 4176.98   24.23
 4252.63   23.28 4385.54   23.87 4534.74   23.36 4573.76    21.5 4595.86   22.31
 4757.37   20.38 4786.74   18.95 4827.95   11.87    4897     7.5 4955.38    3.71
 4975.28    -3.9 5000.27   -5.11 5025.13   -4.66 5049.45     .35 5051.26    2.66
    5089     6.7    5120     8.3  5197.5   12.03 5283.15   11.85 5447.31   15.22
 5686.17   18.03 6062.45   19.32 6150.05   20.76  6448.2   21.95 6558.65   20.98
#Mann= 5 ,-1 , 0
 3780.31     .15       0 4252.63     .07       0    4897     .03       0
    5120     .07       0 5447.31     .15       0
Bank Sta=4897,5120
Exp/Cntr=0.5,0.3

Type RM Length L Ch R = 1 ,6677.703,505.99,377.24,231.02
BEGIN DESCRIPTION:
Hwy 225
END DESCRIPTION:
XS GIS Cut Line= 6
     3168186.547    13824748.853     3168991.296    13825080.161
     3169434.878    13825253.845     3169583.437     13825284.98
     3170449.449    13825414.246     3170856.363    13825462.408
#Sta/Elev= 30
  3780.7   23.49 3808.54   22.79  3854.4   22.15 3950.76   24.23  4006.6   23.54
 4183.34   24.22 4277.38   23.14 4501.06   23.33 4562.24   20.46  4779.2   17.76
 4825.46   13.82    4914       9    4935       5 4955.38    3.71 4975.28    -3.9
 5000.27   -5.11 5025.13   -4.66 5049.45     .35 5051.26    2.66 5074.34    6.29
 5127.14   10.08 5162.38    9.89  5200.8   11.72 5296.68   11.52 5450.98   14.43
 5478.14   15.54 5684.88   17.99 6106.86   19.59    6400   21.62  6564.5   20.85
#Mann= 6 ,-1 , 0
  3780.7     .07       0 3808.54     .15       0 4277.38     .07       0
    4914     .03       0 5127.14     .07       0 5450.98     .15       0
#XS Ineff= 2 , 0
       0    4884   15.85    5116       0   17.89
Permanent Ineff=
       F       F
Bank Sta=4914,5127.14
Exp/Cntr=0.5,0.3

Type RM Length L Ch R = 3 ,6489    ,,,
BEGIN DESCRIPTION:
Bridge at Hwy 225
END DESCRIPTION:
Bridge Culvert--1,0,-1,-1, 0
Deck Dist Width WeirC Skew NumUp NumDn MinLoCord MaxHiCord MaxSubmerge Is_Ogee
16,340,2.6,0, 10, 10, , , 0.95, 0, 0,0,,
    3906    4046    4800    4900    4900    5100    5100    5555    6608    7262
    7.46    7.45   16.85   16.85   19.59   19.59   18.89   18.89   44.99   46.25
       0       0       0       0    12.2    12.2       0       0       0       0
    3906    4046    4800    4900    4900    5100    5100    5555    6608    7262
    7.46    7.45   16.85   16.85   19.59   19.59   18.89   18.89   44.99   46.25
       0       0       0       0    12.2    12.2       0       0       0       0
Pier Skew, UpSta & Num, DnSta & Num=  ,4975, 4 ,4955, 4 , 3 , 3 , 0 ,,
       1       1     1.7     1.7
     -10    10.5    10.5      13
       1       1     1.7     1.7
     -10    10.5    10.5      13
Pier Skew, UpSta & Num, DnSta & Num=  ,5025, 4 ,5005, 4 , 3 , 3 , 0 ,,
       1       1     1.7     1.7
     -10    10.5    10.5      13
       1       1     1.7     1.7
     -10    10.5    10.5      13
BR Coef=-1 , 1 , 0 ,, 0 ,,,0.8,0,2,0,
WSPro=,,,, 1 ,,,, 0 ,,,, 0 ,,,,-1 ,-1 ,-1 , 0 , 0 , 0 , 0 , 0
BC Design=,, 0 ,, 0 ,,,,,,
BC HTab HWMax=24.23

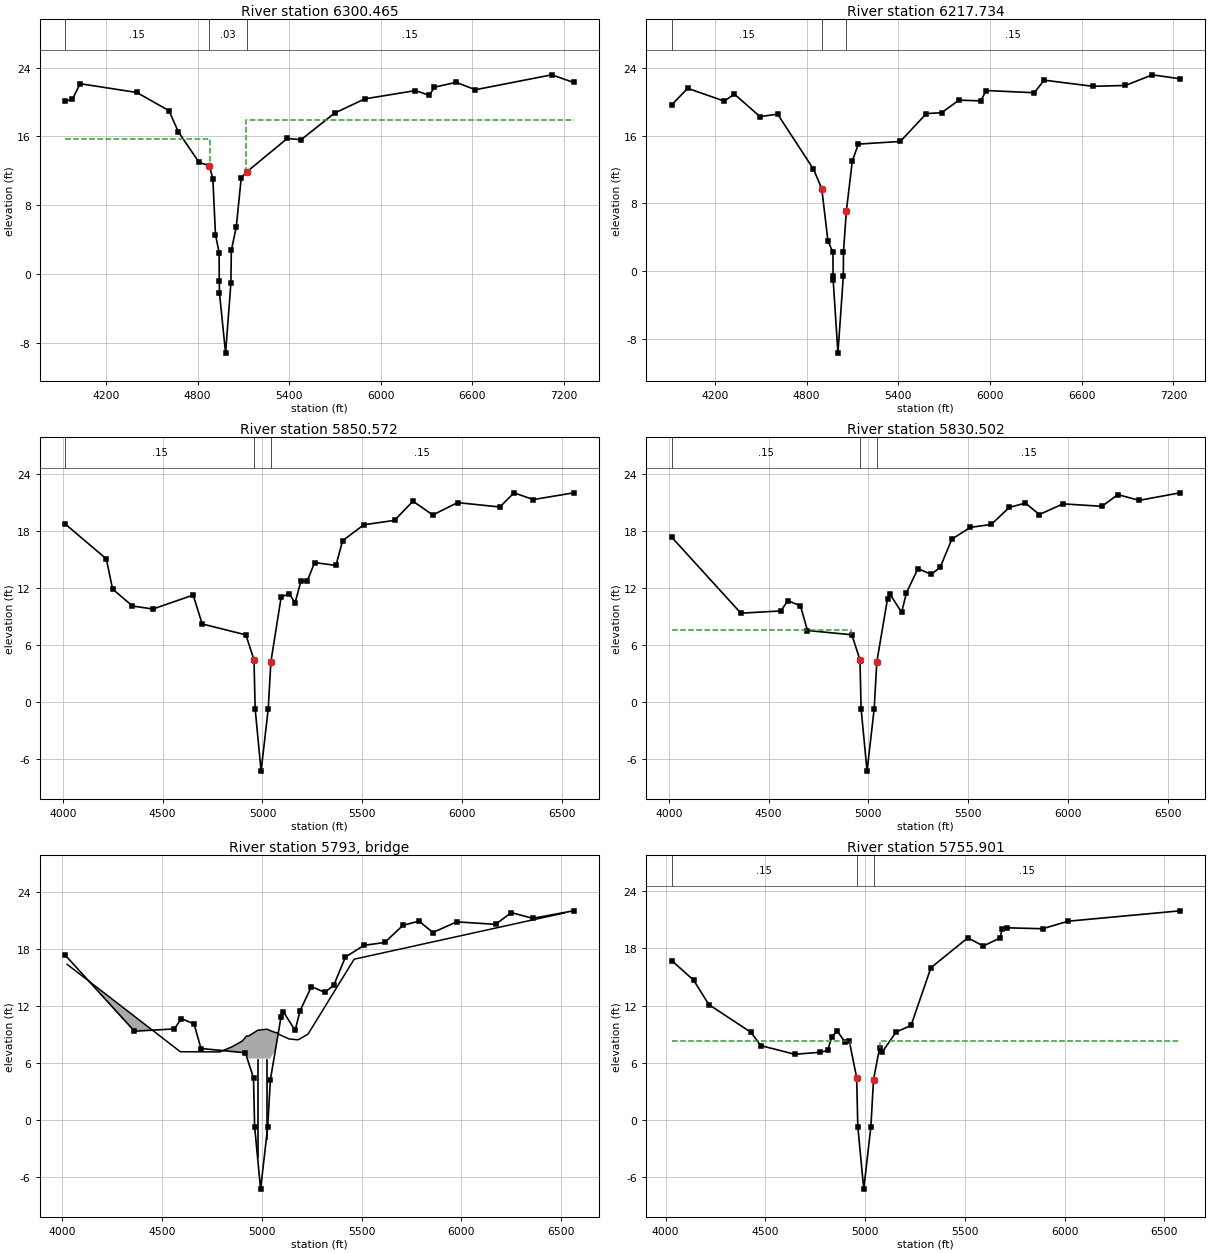
Type RM Length L Ch R = 1 ,6300.465,80.79,82.73,82.05
BEGIN DESCRIPTION:
Hwy 225
END DESCRIPTION:
XS GIS Cut Line= 6
     3168164.414    13825549.275     3169007.328    13825552.987
      3169111.66    13825551.305     3169361.659    13825550.153
     3169684.106    13825530.119     3171478.364    13825791.915
#Sta/Elev= 30
 3931.58    20.1 3978.68    20.3 4029.08   22.12 4400.96    21.1 4611.84   18.99
 4673.08   16.54 4809.32   12.98  4876.3    12.6 4899.79    11.1 4917.07     4.6
 4940.67    2.51 4942.02    -.83 4943.24   -2.19 4983.31   -9.17 5018.06   -1.07
 5021.06    2.77 5053.71    5.51    5086    11.2  5123.7    11.9  5387.7   15.76
 5478.92   15.62 5698.44   18.71    5897   20.36 6228.28   21.32 6319.56   20.77
 6352.26   21.71 6495.06   22.28 6621.78   21.42  7122.1   23.15 7265.18   22.27
#Mann= 3 ,-1 , 0
 3931.58     .15       0  4876.3     .03       0  5123.7     .15       0
#XS Ineff= 2 , 0
       0    4884   15.75    5116       0   17.89
Permanent Ineff=
       F       F
Bank Sta=4876.3,5123.7
Exp/Cntr=0.5,0.3

Type RM Length L Ch R = 1 ,6217.734,348.71,367.16,395.85
BEGIN DESCRIPTION:
Hwy 225
END DESCRIPTION:
XS GIS Cut Line= 6
      3168160.42    13825631.929     3168990.729    13825633.266
      3169112.49    13825631.302     3169364.306    13825630.141
     3169680.797    13825610.483     3171466.814    13825871.077
#Sta/Elev= 30
  3917.4   19.68 4022.22   21.64 4260.64   20.13 4328.28   20.95 4495.44   18.29
 4610.62   18.58  4845.3   12.06 4899.46    9.76 4939.81    3.56 4972.45    2.21
  4973.5    -.64 4974.08   -1.08  5005.2   -9.73 5040.49    -.61 5041.39    2.24
 5060.19    7.07    5099      13 5138.46   15.03 5413.66   15.35 5583.88   18.65
 5683.48   18.75  5796.7   20.24 5940.34   20.15 5974.52   21.38 6289.68   21.12
 6354.18   22.61 6671.96   21.88 6886.46   21.98  7062.3   23.24 7243.34   22.77
#Mann= 3 ,-1 , 0
  3917.4     .15       0 4899.46     .03       0 5060.19     .15       0
Bank Sta=4899.46,5060.19
Exp/Cntr=0.3,0.1

Type RM Length L Ch R = 1 ,5850.572,20.11,20.07,20.11
BEGIN DESCRIPTION:
Shaw Road
END DESCRIPTION:
XS GIS Cut Line= 5
     3168304.983    13825957.608     3169214.063    13825990.974
     3169367.665    13825994.263     3169961.791    13826017.241
     3170850.844     13826044.54
#Sta/Elev= 30
 4011.62   18.75  4217.6   15.08 4249.01    11.9  4348.7   10.12 4451.01     9.8
  4652.9   11.27  4697.9    8.23 4917.08    7.08 4957.76    4.44 4963.45    -.69
 4993.28   -7.26 5029.02     -.7 5042.24    4.23    5094   11.08 5135.36    11.4
 5163.18   10.43  5193.2   12.76 5224.39   12.75 5261.67   14.69 5368.58   14.39
 5401.52   16.99 5508.44   18.67 5661.87   19.13 5754.31   21.15 5853.64    19.7
  5977.7      21 6189.87   20.54 6260.66   22.03 6357.46   21.32 6558.99   22.03
#Mann= 3 ,-1 , 0
 4011.62     .15       0 4957.76     .03       0 5042.24     .15       0
Bank Sta=4957.76,5042.24
Exp/Cntr=0.5,0.3

Type RM Length L Ch R = 1 ,5830.502,71.1,74.6,70.38
BEGIN DESCRIPTION:
Shaw Road
END DESCRIPTION:
XS GIS Cut Line= 5
      3168304.25    13825977.595     3169213.482    13826010.966
     3169367.065    13826014.255     3169961.098    13826037.229
      3170850.23     13826064.53
#Sta/Elev= 30
 4014.12   17.35 4360.98    9.35    4561    9.59 4596.72   10.67  4659.7   10.12
 4694.54    7.53 4917.08    7.08 4957.76    4.44 4963.45    -.69 4993.28   -7.26
 5029.02     -.7 5042.24    4.23    5096   10.89 5107.74   11.38 5166.42    9.43
 5190.52   11.48 5248.32   14.04 5315.24   13.43 5360.08   14.19  5418.5   17.15
 5511.68   18.38 5615.32   18.68 5706.46   20.48 5787.06   20.93 5856.88   19.73
 5975.98   20.85 6170.56   20.59  6249.8   21.82 6357.24   21.22 6561.62   22.01
#Mann= 3 ,-1 , 0
 4014.12     .15       0 4957.76     .03       0 5042.24     .15       0
#XS Ineff= 2 , 0
       0    4914     7.6    5073       0    7.75
Permanent Ineff=
       F       F
Bank Sta=4957.76,5042.24
Exp/Cntr=0.5,0.3

Type RM Length L Ch R = 3 ,5793    ,,,
BEGIN DESCRIPTION:
Bridge at Shaw Road
END DESCRIPTION:
Bridge Culvert--1,0,-1,-1, 0
Deck Dist Width WeirC Skew NumUp NumDn MinLoCord MaxHiCord MaxSubmerge Is_Ogee
13,40,2.6,0, 19, 19, , , 0.95, 0, 0,0,,
    4024    4591    4789    4850    4902    4923    4923    4934    4979    5024
    5068    5077    5077    5088    5135    5181    5231    5462    6516
   16.38    7.19    7.17    7.71    8.32    8.85    8.85    8.85    9.45    9.56
     9.2     9.2     9.2    8.99    8.54    8.44    9.04   16.92   21.79
       0       0       0       0       0       0    6.47    6.47    6.47    6.47
    6.47    6.47       0       0       0       0       0       0       0
    4024    4591    4789    4850    4902    4923    4923    4934    4979    5024
    5068    5077    5077    5088    5135    5181    5231    5462    6516
   16.38    7.19    7.17    7.71    8.32    8.85    8.85    8.85    9.45    9.56
     9.2     9.2     9.2    8.99    8.54    8.44    9.04   16.92   21.79
       0       0       0       0       0       0    6.47    6.47    6.47    6.47
    6.47    6.47       0       0       0       0       0       0       0
Pier Skew, UpSta & Num, DnSta & Num=  ,4978, 4 ,4978, 4 , 3 , 3 , 0 ,,
     1.5     1.5     2.5     2.5
     -10    4.02    4.02       7
     1.5     1.5     2.5     2.5
     -10    4.02    4.02       7
Pier Skew, UpSta & Num, DnSta & Num=  ,5022, 4 ,5022, 4 , 3 , 3 , 0 ,,
     1.5     1.5     2.5     2.5
     -10    4.02    4.02       7
     1.5     1.5     2.5     2.5
     -10    4.02    4.02       7
BR Coef=-1 , 1 , 0 ,, 0 ,,,0.8,-1,2,0,
WSPro=,,,, 1 ,,,, 0 ,,,, 0 ,,,,-1 ,-1 ,-1 , 0 , 0 , 0 , 0 , 0
BC Design=,, 0 ,, 0 ,,,,,,
BC HTab HWMax=22.01

Type RM Length L Ch R = 1 ,5755.901,97.39,99.08,87.97
BEGIN DESCRIPTION:
Shaw Road
END DESCRIPTION:
XS GIS Cut Line= 5
     3168301.682    13826047.547     3169211.449    13826080.938
     3169364.962    13826084.226     3169958.671    13826107.187
     3170848.081    13826134.497
#Sta/Elev= 30
 4030.52   16.72 4140.84   14.66 4216.92    12.1 4428.28    9.19 4477.18     7.8
 4647.16    6.89 4775.95     7.1  4812.4    7.29 4833.77    8.75 4860.51    9.32
    4900    8.16    4921    8.25 4957.76    4.44 4963.45    -.69 4993.28   -7.26
 5029.02     -.7 5042.24    4.23    5073    7.59    5086    7.12 5154.98    9.22
 5230.41    9.91 5329.86   15.97 5514.88   19.11 5592.21   18.25 5676.72   19.09
 5686.06      20 5710.31   20.16 5889.77   20.06 6017.36   20.85 6578.43   21.94
#Mann= 3 ,-1 , 0
 4030.52     .15       0 4957.76     .03       0 5042.24     .15       0
#XS Ineff= 2 , 0
       0    4926    8.25    5073       0    8.25
Permanent Ineff=
       F       F
Bank Sta=4957.76,5042.24
Exp/Cntr=0.5,0.3

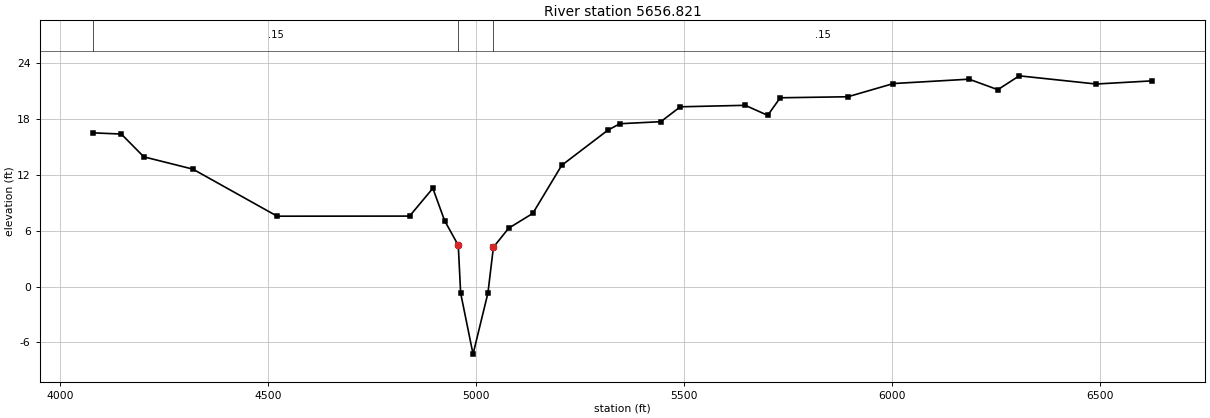
Type RM Length L Ch R = 1 ,5656.821,586.24,840.56,980.8
BEGIN DESCRIPTION:
Shaw Road
END DESCRIPTION:
XS GIS Cut Line= 5
     3168298.748    13826127.494     3169209.125    13826160.907
      3169362.56    13826164.193     3169955.897     13826187.14
     3170845.626     13826214.46
#Sta/Elev= 30
 4078.76   16.53 4147.42    16.4 4201.52   13.95 4319.45   12.63 4522.21    7.57
 4840.67    7.58  4896.6   10.57    4925    7.08 4957.76    4.44 4963.45    -.69
 4993.28   -7.26 5029.02     -.7 5042.24    4.23    5079    6.28 5136.94    7.87
 5206.53   13.04 5316.99    16.8 5346.31   17.51 5444.86   17.73 5491.69   19.33
 5647.86   19.49  5701.9   18.41 5731.93    20.3 5894.73   20.41 6004.23   21.83
 6186.17    22.3 6255.35   21.17 6306.73   22.66 6491.69   21.78 6627.15   22.12
#Mann= 3 ,-1 , 0
 4078.76     .15       0 4957.76     .03       0 5042.24     .15       0
Bank Sta=4957.76,5042.24
Exp/Cntr=0.3,0.1