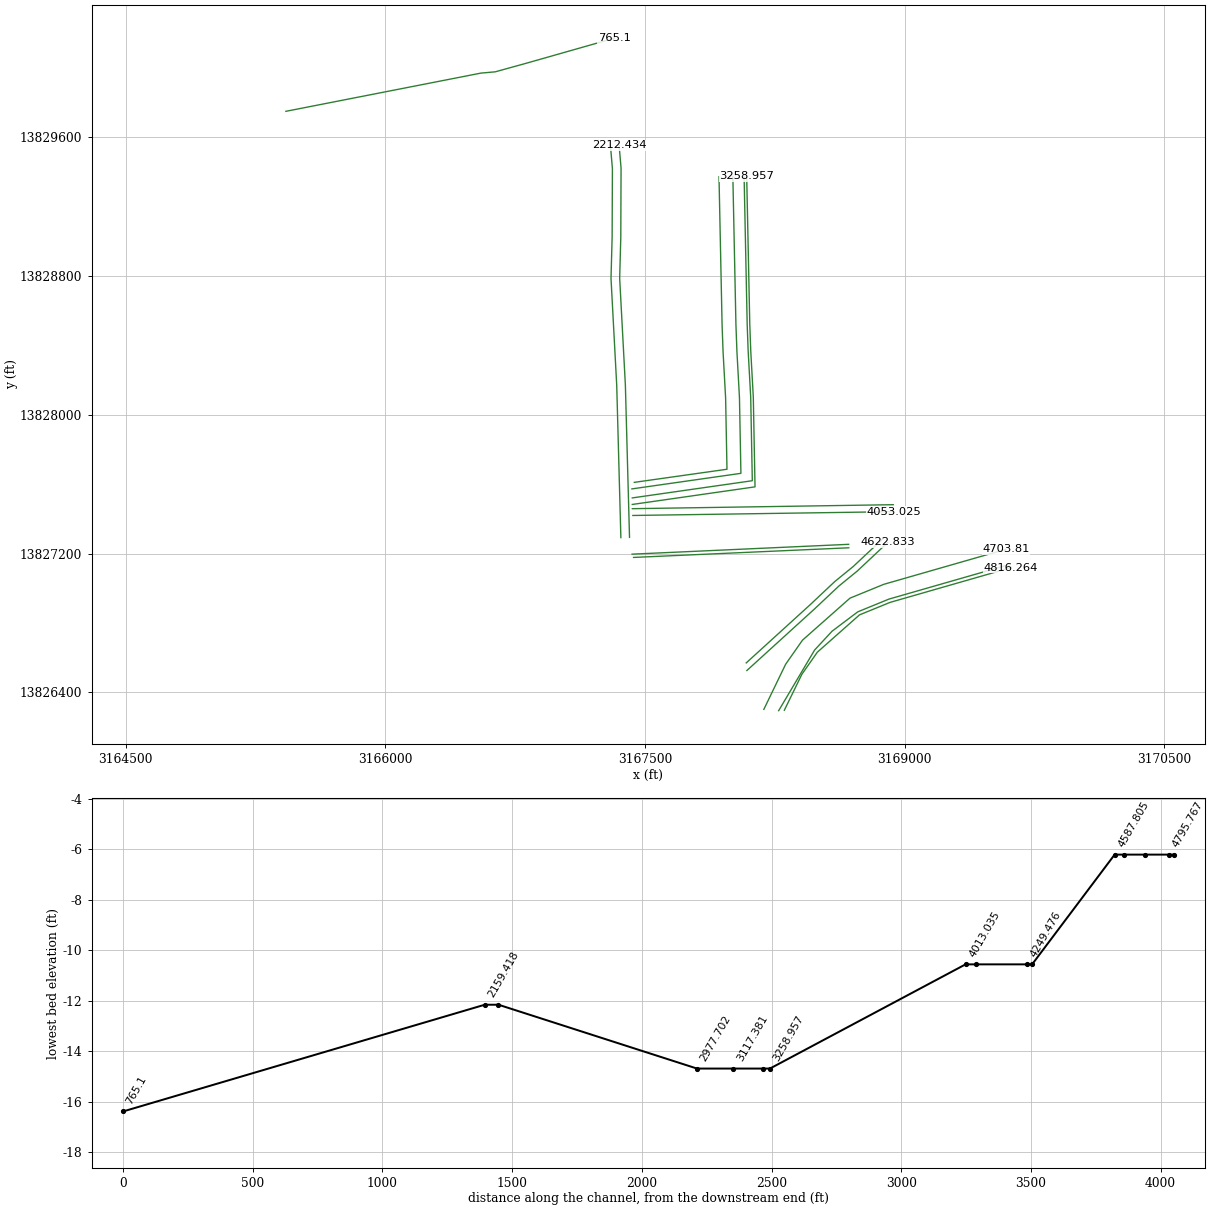
HEC-RAS study I100-00-00.prj: I100-00-00

--- I100-00-00.g01 (geometry) --- (continued)

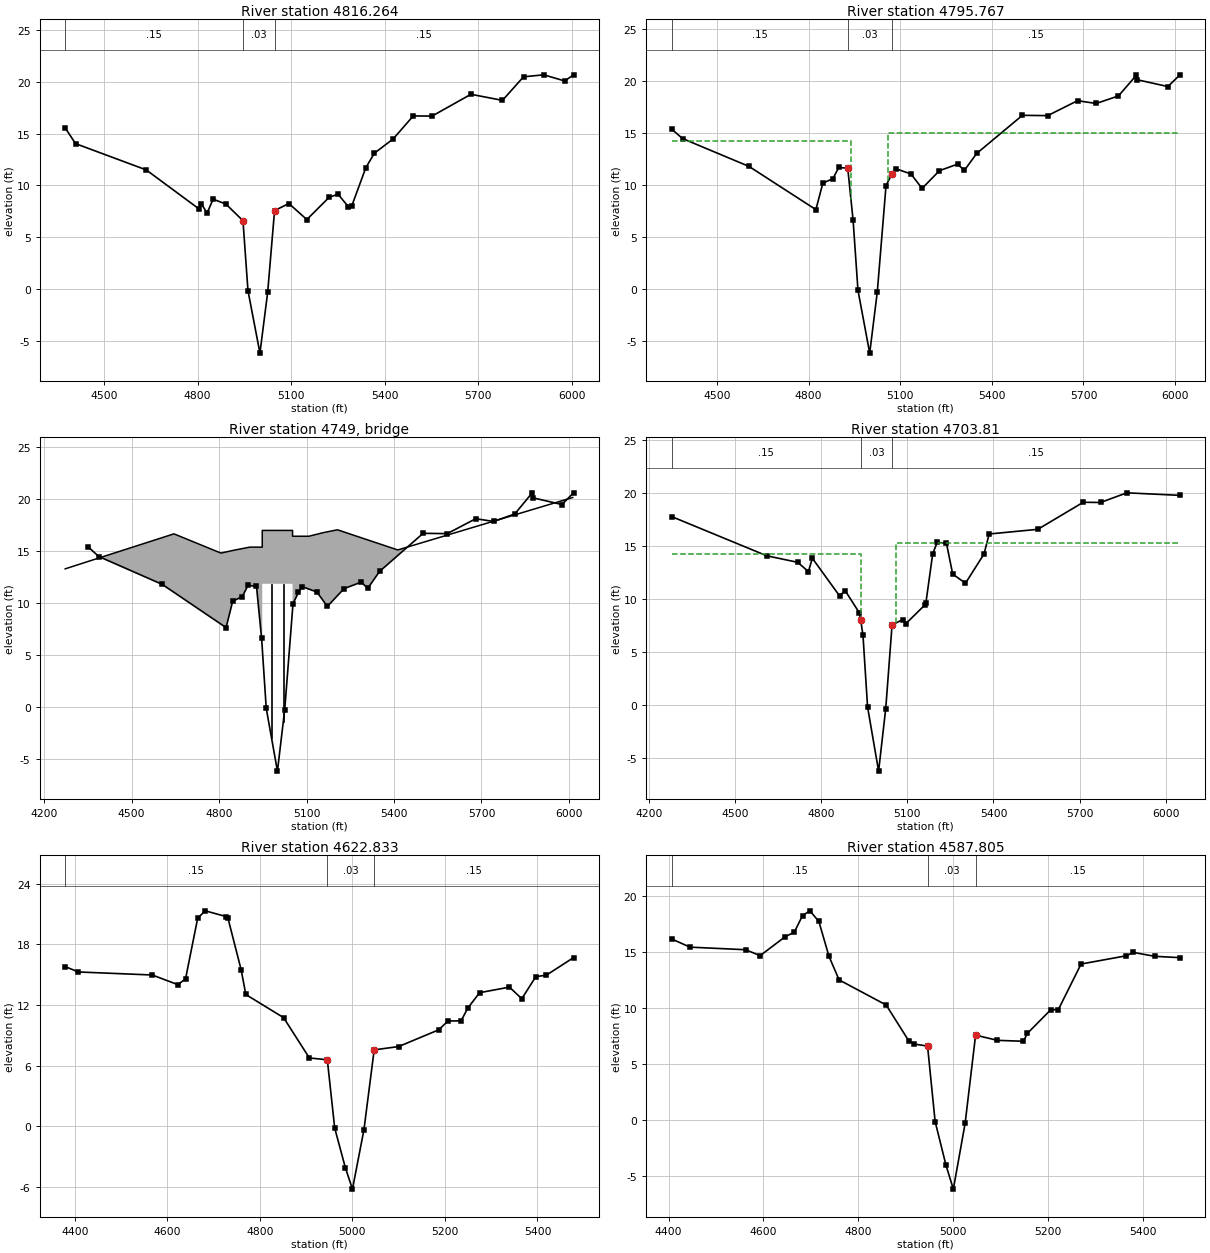
Type RM Length L Ch R = 1 ,4816.264,20.3,20.5,23.17
BEGIN DESCRIPTION:
Richey Road
END DESCRIPTION:
XS GIS Cut Line= 6
     3168305.107    13826297.539     3168406.755     13826505.06
      3168495.76    13826631.826     3168739.177    13826846.746
     3168915.914    13826918.815     3169614.983    13827118.959
#Sta/Elev= 30
 4375.68   15.56 4408.76   14.04  4635.5    11.5 4804.68    7.73 4811.96    8.24
 4830.62    7.33    4850    8.67 4890.88     8.2 4945.76    6.59 4961.71    -.16
 5000.13   -6.21 5024.99    -.31 5047.02    7.57 5093.02    8.25  5150.5     6.7
 5221.96    8.85  5250.6    9.15 5283.76    7.94 5295.02    8.05 5339.92   11.73
  5367.3   13.12 5427.28   14.49 5491.84   16.72    5552    16.7 5676.76   18.81
  5777.8   18.22  5845.5    20.5 5910.36   20.69 5977.12    20.1 6005.76   20.68
#Mann= 3 ,-1 , 0
 4375.68     .15       0 4945.76     .03       0 5047.02     .15       0
Bank Sta=4945.76,5047.02
Exp/Cntr=0.5,0.3

Type RM Length L Ch R = 1 ,4795.767,92.33,91.96,103.86
BEGIN DESCRIPTION:
Richey Road
END DESCRIPTION:
XS GIS Cut Line= 6
      3168272.38    13826295.022     3168480.178    13826644.438
     3168580.545    13826752.445     3168729.225    13826864.287
     3168909.366    13826937.744     3169609.478    13827138.187
#Sta/Elev= 30
 4351.82   15.36 4387.55   14.45 4605.02   11.77 4823.94    7.61 4846.69   10.16
 4879.48   10.59    4899   11.67 4928.23   11.59 4945.76    6.59 4961.71    -.16
 5000.13   -6.21 5024.99    -.31 5053.54    9.92 5072.29      11  5085.6   11.55
 5135.38   11.04 5171.51    9.65 5228.46   11.36 5287.72   11.99 5310.04   11.39
 5350.45   13.02 5499.99   16.69 5582.71   16.66 5680.57    18.1  5741.7   17.83
 5814.59   18.56 5873.36   20.56 5875.25   20.12 5976.22   19.46 6015.96   20.59
#Mann= 3 ,-1 , 0
 4351.82     .15       0 4928.23     .03       0 5072.29     .15       0
#XS Ineff= 2 , 0
       0    4939   14.25    5061       0      15
Permanent Ineff=
       F       F
Bank Sta=4928.23,5072.29
Exp/Cntr=0.5,0.3

Type RM Length L Ch R = 3 ,4749    ,,,
BEGIN DESCRIPTION:
Bridge at Richey Road
END DESCRIPTION:
Bridge Culvert--1,0,-1,-1, 0
Deck Dist Width WeirC Skew NumUp NumDn MinLoCord MaxHiCord MaxSubmerge Is_Ogee
9,55,2.6,0, 14, 14, , , 0.95, 0, 0,0,,
    4272    4645    4806    4854    4905    4948    4948    5052    5052    5108
    5158    5206    5413    6013
   13.27   16.64   14.79   15.08   15.36   15.36   16.97   16.97   16.41   16.41
   16.76   17.03   15.09   20.14
       0       0       0       0       0       0   11.83   11.83       0       0
       0       0       0       0
    4272    4645    4806    4854    4905    4948    4948    5052    5052    5108
    5158    5206    5413    6013
   13.27   16.64   14.79   15.08   15.36   15.36   16.97   16.97   16.41   16.41
   16.76   17.03   15.09   20.14
       0       0       0       0       0       0   11.83   11.83       0       0
       0       0       0       0
Pier Skew, UpSta & Num, DnSta & Num=  ,4980, 2 ,4980, 2 , 0 , 0 , 0 ,,
       2       2
     -10      12
       2       2
     -10      12
Pier Skew, UpSta & Num, DnSta & Num=  ,5020, 2 ,5020, 2 , 0 , 0 , 0 ,,
       2       2
     -10      12
       2       2
     -10      12
BR Coef=-1 , 1 , 0 ,, 0 ,,,0.8,-1,2,0,
WSPro=,,,, 1 ,,,, 0 ,,,, 0 ,,,,-1 ,-1 ,-1 , 0 , 0 , 0 , 0 , 0
BC Design=,, 0 ,, 0 ,,,,,,
BC HTab HWMax=20.61

Type RM Length L Ch R = 1 ,4703.81 ,90.4,80.98,136.73
BEGIN DESCRIPTION:
Richey Road
END DESCRIPTION:
XS GIS Cut Line= 6
     3168186.788    13826302.574     3168312.775    13826562.638
     3168410.059    13826701.194     3168684.442    13826943.221
     3168879.902    13827022.925     3169584.706     13827224.71
#Sta/Elev= 30
  4279.6   17.78 4610.24   14.09  4718.4   13.47  4755.7    12.6 4769.48   13.85
 4864.12   10.31 4883.52   10.81  4932.8    8.72    4938       8 4945.76    6.59
 4961.71    -.16 5000.13   -6.21 5024.99    -.31 5047.02    7.57  5083.4    8.06
    5094    7.66  5160.9    9.44 5164.72    9.63  5188.6   14.29 5204.38   15.36
 5236.48   15.26  5258.1   12.36 5302.66    11.5 5367.28   14.26 5385.06   16.14
 5554.48   16.58 5712.72   19.13  5772.8   19.11 5864.56   20.02 6049.62   19.78
#Mann= 3 ,-1 , 0
  4279.6     .15       0    4938     .03       0 5047.02     .15       0
#XS Ineff= 2 , 0
       0    4939   14.25    5061       0    15.3
Permanent Ineff=
       F       F
Bank Sta=4938,5047.02
Exp/Cntr=0.5,0.3

Type RM Length L Ch R = 1 ,4622.833,35.21,35.03,35
BEGIN DESCRIPTION:
Richey Road
END DESCRIPTION:
XS GIS Cut Line= 5
     3168088.854    13826526.354     3168479.005    13826880.488
     3168619.217    13827012.115     3168726.521     13827099.39
     3168902.501     13827264.11
#Sta/Elev= 30
  4379.3   15.81  4407.7   15.28 4567.46   14.98  4622.5   14.03  4639.3   14.58
 4665.58    20.6 4681.84   21.33 4727.42   20.76 4730.96   20.62 4759.62   15.48
 4769.58   13.05 4851.26   10.76 4906.98    6.77 4945.76    6.59 4961.71    -.16
 4984.61   -4.07 5000.13   -6.21 5024.99    -.31 5047.02    7.57    5100     7.9
 5186.28    9.55 5206.72   10.43 5234.84   10.44 5249.58   11.72 5274.88   13.23
 5339.44   13.78 5366.04   12.63  5396.4   14.82 5419.08   14.96 5477.88    16.7
#Mann= 3 ,-1 , 0
  4379.3     .15       0 4945.76     .03       0 5047.02     .15       0
Bank Sta=4945.76,5047.02
Exp/Cntr=0.3,0.1

Type RM Length L Ch R = 1 ,4587.805,454.56,318.12,125.59
XS GIS Cut Line= 5
     3168085.121    13826570.233     3168455.264    13826906.207
     3168596.168    13827038.484     3168703.493    13827125.775
     3168878.584    13827289.663
#Sta/Elev= 30
 4406.49   16.17 4445.21   15.44 4562.31   15.21 4592.92   14.68 4646.18   16.39
 4664.83   16.77 4682.33   18.27  4697.8   18.69 4716.69   17.74 4737.93   14.63
 4759.37   12.51 4858.69   10.26 4906.37    7.04  4917.3    6.77 4945.76    6.59
 4961.71    -.16 4984.61   -4.07 5000.13   -6.21 5024.99    -.31 5047.02    7.57
 5093.02     7.1 5147.78    7.02 5156.29    7.73 5205.47    9.84 5221.39    9.85
 5269.29   13.93  5364.8   14.67 5379.52   14.97 5424.45   14.62 5477.81    14.5
#Mann= 3 ,-1 , 0
 4406.49     .15       0 4945.76     .03       0 5047.02     .15       0
Bank Sta=4945.76,5047.02
Exp/Cntr=0.3,0.1

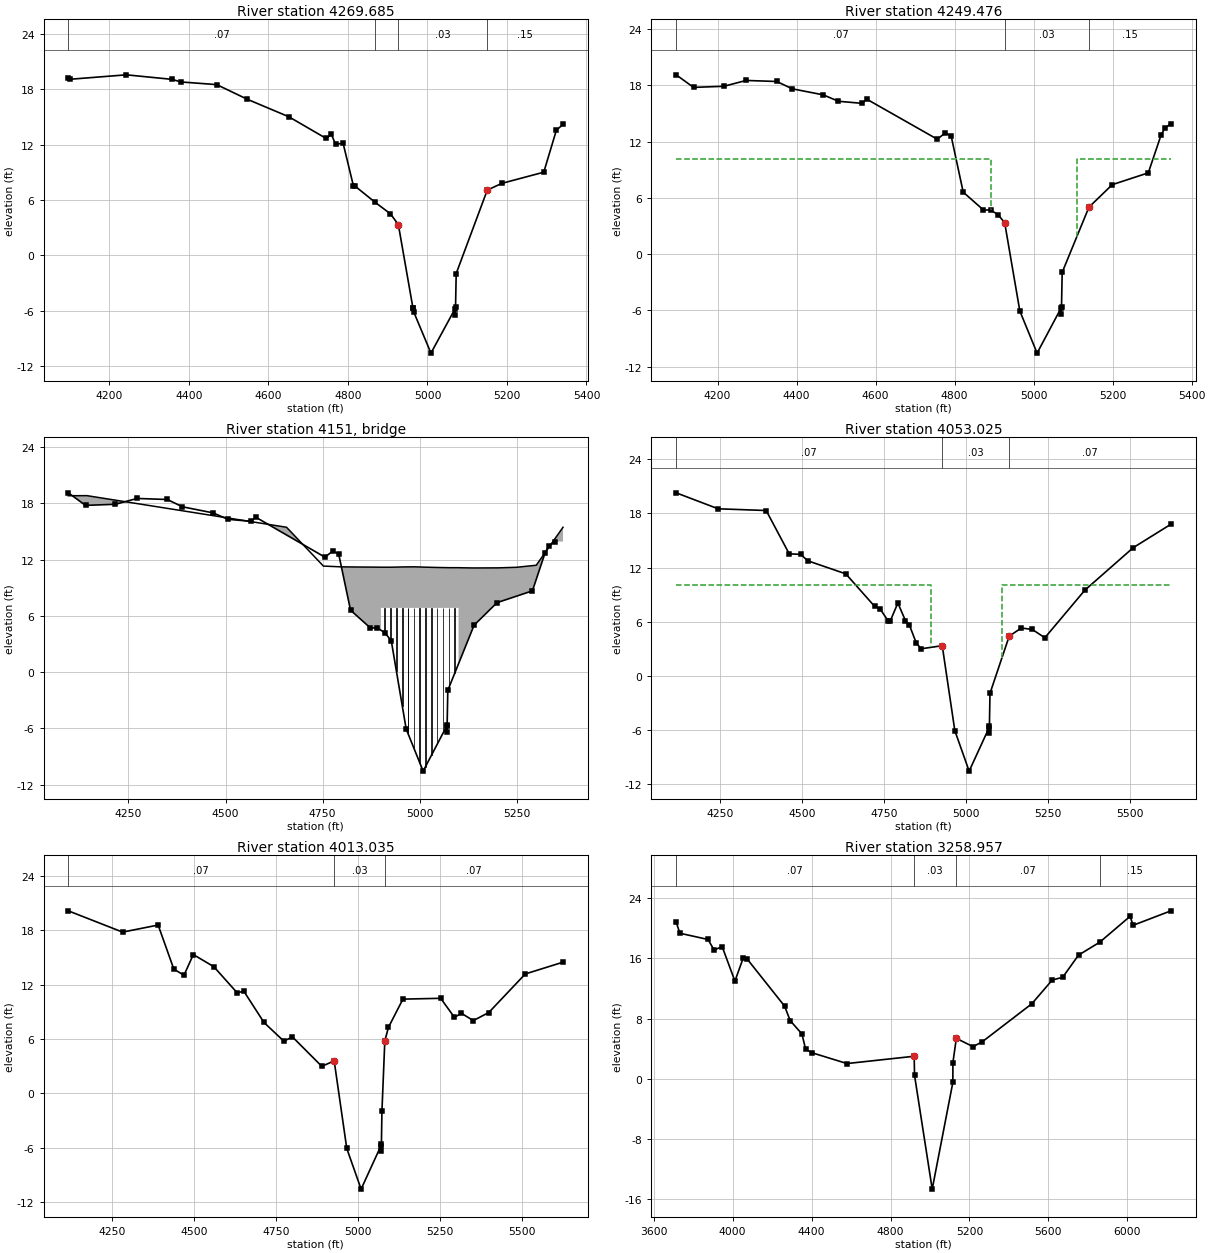
Type RM Length L Ch R = 1 ,4269.685,19.72,20.21,21.55
XS GIS Cut Line= 2
     3167434.302    13827177.782     3168677.507    13827233.296
#Sta/Elev= 30
 4096.54   19.23 4100.98   19.06 4242.58   19.54 4357.48   19.05 4379.74   18.77
 4470.06   18.48 4546.64    16.9 4651.52      15  4745.2   12.66 4758.52   13.09
 4768.72   12.03 4787.82   12.14 4813.78    7.52 4817.88     7.5  4868.1    5.76
    4907     4.5 4926.75    3.34 4963.68   -5.73 4964.26   -5.72  4965.1   -6.07
 5008.78  -10.56 5069.32   -5.77 5069.52   -6.39 5070.59    -5.6 5072.28   -1.95
 5150.39    7.07    5187     7.8 5292.54    9.01 5324.28   13.56 5340.98   14.17
#Mann= 4 ,-1 , 0
 4096.54     .07       0  4868.1     .15       0 4926.75     .03       0
 5150.39     .15       0
Bank Sta=4926.75,5150.39
Exp/Cntr=0.5,0.3

Type RM Length L Ch R = 1 ,4249.476,201.25,196.44,195.28
XS GIS Cut Line= 2
     3167425.617      13827196.6     3168676.576    13827253.274
#Sta/Elev= 30
 4095.26   19.11 4139.36   17.77 4216.22   17.89 4272.16   18.51 4349.88    18.4
 4389.06   17.62 4467.96   16.97 4505.88   16.29 4565.94   16.07  4577.4   16.52
 4755.94   12.25 4776.02    12.9 4791.18   12.61  4821.8     6.6    4873     4.7
    4891     4.7    4910     4.2 4926.75    3.34  4965.1   -6.07 5008.78  -10.56
 5069.32   -5.77 5069.52   -6.39 5070.59    -5.6 5072.28   -1.95    5140       5
    5199     7.4  5290.2    8.66 5322.28   12.65 5331.74   13.41  5347.5   13.91
#Mann= 3 ,-1 , 0
 4095.26     .07       0 4926.75     .03       0    5140     .15       0
#XS Ineff= 2 , 0
       0    4891    10.1    5109       0    10.1
Permanent Ineff=
       F       F
Bank Sta=4926.75,5140
Exp/Cntr=0.5,0.3

Type RM Length L Ch R = 3 ,4151    ,,,
BEGIN DESCRIPTION:
Pipe and Railroad Bridge Crossing
END DESCRIPTION:
Bridge Culvert--1,0,-1,-1, 0
Deck Dist Width WeirC Skew NumUp NumDn MinLoCord MaxHiCord MaxSubmerge Is_Ogee
9,175,2.6,0, 23, 24, , , 0.95, 0, 0,0,,
    4095    4143    4657    4752    4797    4844    4882    4900    4900    4927
    4958    4988    5017    5047    5077    5100    5100    5107    5138    5201
    5249    5300    5369
    18.8   18.81   15.44    11.3   11.22    11.2   11.19   11.18   11.18   11.18
   11.21   11.22   11.18   11.15   11.13   11.13   11.13   11.12    11.1   11.11
   11.17   11.39   15.44
       0       0       0       0       0       0       0       0    6.84    6.84
    6.84    6.84    6.84    6.84    6.84    6.84       0       0       0       0
       0       0       0
    4143    4657    4752    4797    4844    4882    4900    4900    4927    4958
    4988    5017    5047    5077    5100    5100    5107    5138    5201    5249
    5300    5369    5395    5645
   18.81   15.44    11.3   11.22    11.2   11.19   11.18   11.18   11.18   11.21
   11.22   11.18   11.15   11.13   11.13   11.13   11.12    11.1   11.11   11.17
   11.39   15.44    15.5    17.2
       0       0       0       0       0       0       0    6.84    6.84    6.84
    6.84    6.84    6.84    6.84    6.84       0       0       0       0       0
       0       0       0       0
Pier Skew, UpSta & Num, DnSta & Num=  ,4910, 2 ,4910, 2 , 0 , 0 , 0 ,,
     1.5     1.5
     -15       7
     1.5     1.5
     -15       7
Pier Skew, UpSta & Num, DnSta & Num=  ,4925, 2 ,4925, 2 , 0 , 0 , 0 ,,
     1.5     1.5
     -15       7
     1.5     1.5
     -15       7
Pier Skew, UpSta & Num, DnSta & Num=  ,4940, 2 ,4940, 2 , 0 , 0 , 0 ,,
     1.5     1.5
     -15       7
     1.5     1.5
     -15       7
Pier Skew, UpSta & Num, DnSta & Num=  ,4955, 2 ,4955, 2 , 0 , 0 , 0 ,,
     1.5     1.5
     -15       7
     1.5     1.5
     -15       7
Pier Skew, UpSta & Num, DnSta & Num=  ,4970, 2 ,4970, 2 , 0 , 0 , 0 ,,
     1.5     1.5
     -15       7
     1.5     1.5
     -15       7
Pier Skew, UpSta & Num, DnSta & Num=  ,4970, 2 ,4970, 2 , 0 , 0 , 0 ,,
     1.5     1.5
     -15       7
     1.5     1.5
     -15       7
Pier Skew, UpSta & Num, DnSta & Num=  ,4985, 2 ,4985, 2 , 0 , 0 , 0 ,,
     1.5     1.5
     -15       7
     1.5     1.5
     -15       7
Pier Skew, UpSta & Num, DnSta & Num=  ,5000, 2 ,5000, 2 , 0 , 0 , 0 ,,
     1.5     1.5
     -15       7
     1.5     1.5
     -15       7
Pier Skew, UpSta & Num, DnSta & Num=  ,5015, 2 ,5015, 2 , 0 , 0 , 0 ,,
     1.5     1.5
     -15       7
     1.5     1.5
     -15       7
Pier Skew, UpSta & Num, DnSta & Num=  ,5030, 2 ,5030, 2 , 0 , 0 , 0 ,,
     1.5     1.5
     -15       7
     1.5     1.5
     -15       7
Pier Skew, UpSta & Num, DnSta & Num=  ,5045, 2 ,5045, 2 , 0 , 0 , 0 ,,
     1.5     1.5
     -15       7
     1.5     1.5
     -15       7
Pier Skew, UpSta & Num, DnSta & Num=  ,5060, 2 ,5060, 2 , 0 , 0 , 0 ,,
     1.5     1.5
     -15       7
     1.5     1.5
     -15       7
Pier Skew, UpSta & Num, DnSta & Num=  ,5075, 2 ,5075, 2 , 0 , 0 , 0 ,,
     1.5     1.5
     -15       7
     1.5     1.5
     -15       7
Pier Skew, UpSta & Num, DnSta & Num=  ,5090, 2 ,5090, 2 , 0 , 0 , 0 ,,
     1.5     1.5
     -15       7
     1.5     1.5
     -15       7
BR Coef=-1 , 1 , 1 ,1.25, 0 ,,,0.8,0,2,0,
WSPro=,,,, 1 ,,,, 0 ,,,, 0 ,,,,-1 ,-1 ,-1 , 0 , 0 , 0 , 0 , 0
BC Design=,, 0 ,, 0 ,,,,,,
BC HTab HWMax=19.11

Type RM Length L Ch R = 1 ,4053.025,39.86,39.99,40.83
XS GIS Cut Line= 3
     3167429.959     13827419.51     3168708.931    13827438.163
 3168938.306509113827441.5082971
#Sta/Elev= 30
  4115.5   20.28 4243.52   18.51 4389.94   18.32 4460.18   13.52 4494.84   13.46
  4517.4   12.74 4632.72    11.3 4720.56     7.7  4737.3    7.41 4761.44    6.11
 4767.76    6.03 4791.44    8.07 4814.44    6.13 4826.22    5.66    4848     3.6
    4863       3 4926.75    3.34  4965.1   -6.07 5008.78  -10.56 5069.32   -5.77
 5069.52   -6.39 5070.59    -5.6 5072.28   -1.95    5131     4.4    5168     5.3
  5201.2    5.14 5239.68    4.22 5361.52    9.49    5509    14.2    5624    16.8
#Mann= 3 ,-1 , 0
  4115.5     .07       0 4926.75     .03       0    5131     .07       0
#XS Ineff= 2 , 0
       0    4891    10.1    5109       0    10.1
Permanent Ineff=
       F       F
Bank Sta=4926.75,5131
Exp/Cntr=0.5,0.3

Type RM Length L Ch R = 1 ,4013.035,151.2,754.08,1178.04
XS GIS Cut Line= 3
     3167427.064    13827458.591     3168708.143    13827478.155
 3168934.296805713827481.6087082
#Sta/Elev= 30
 4116.59   20.17 4282.08   17.82 4390.38    18.6 4438.19   13.73 4469.12   13.06
 4497.59   15.34 4560.08      14 4630.83   11.13 4651.71   11.28 4712.92    7.84
 4773.39    5.78 4799.51    6.25    4889       3 4926.75     3.6  4965.1   -6.07
 5008.78  -10.56 5069.32   -5.77 5069.52   -6.39 5070.59    -5.6 5072.28   -1.95
    5081     5.8    5092     7.3  5136.2   10.42 5251.29   10.51 5293.21     8.4
 5314.22    8.86  5350.5    8.05 5397.82    8.94    5509    13.2    5624    14.5
#Mann= 3 ,-1 , 0
 4116.59     .07       0 4926.75     .03       0    5081     .07       0
#XS Ineff= 1 ,-1
    5250    5450   10.15
Permanent Ineff=
       F
Bank Sta=4926.75,5081
Exp/Cntr=0.3,0.1

Type RM Length L Ch R = 1 ,3258.957,58.11,26.55,27.15
BEGIN DESCRIPTION:
Richey Road
END DESCRIPTION:
XS GIS Cut Line= 6
     3167426.803    13827482.935     3168135.855    13827584.385
     3168125.918    13828101.292     3168111.157     13828368.09
     3168105.491    13828522.751     3168087.728    13829374.075
#Sta/Elev= 30
 3714.04   20.82 3732.76   19.34 3875.36   18.51 3906.22   17.11  3947.1   17.56
 4011.76   12.97 4053.16   16.01  4075.3   15.86  4263.6    9.64  4291.7    7.72
  4351.2    5.95 4369.66    3.94 4400.26    3.46 4579.42    2.01 4919.88    2.98
 4921.82     .44 5011.32  -14.69  5115.9     -.5 5116.23    2.13 5133.51    5.36
    5218    4.26 5263.68    4.88 5515.96    9.96 5619.28   13.11 5672.64   13.49
 5752.64   16.43 5860.24   18.15 6013.56   21.58 6029.66    20.4  6220.8   22.32
#Mann= 4 ,-1 , 0
 3714.04     .07       0 4919.88     .03       0 5133.51     .07       0
 5860.24     .15       0
Bank Sta=4919.88,5133.51
Exp/Cntr=0.5,0.3

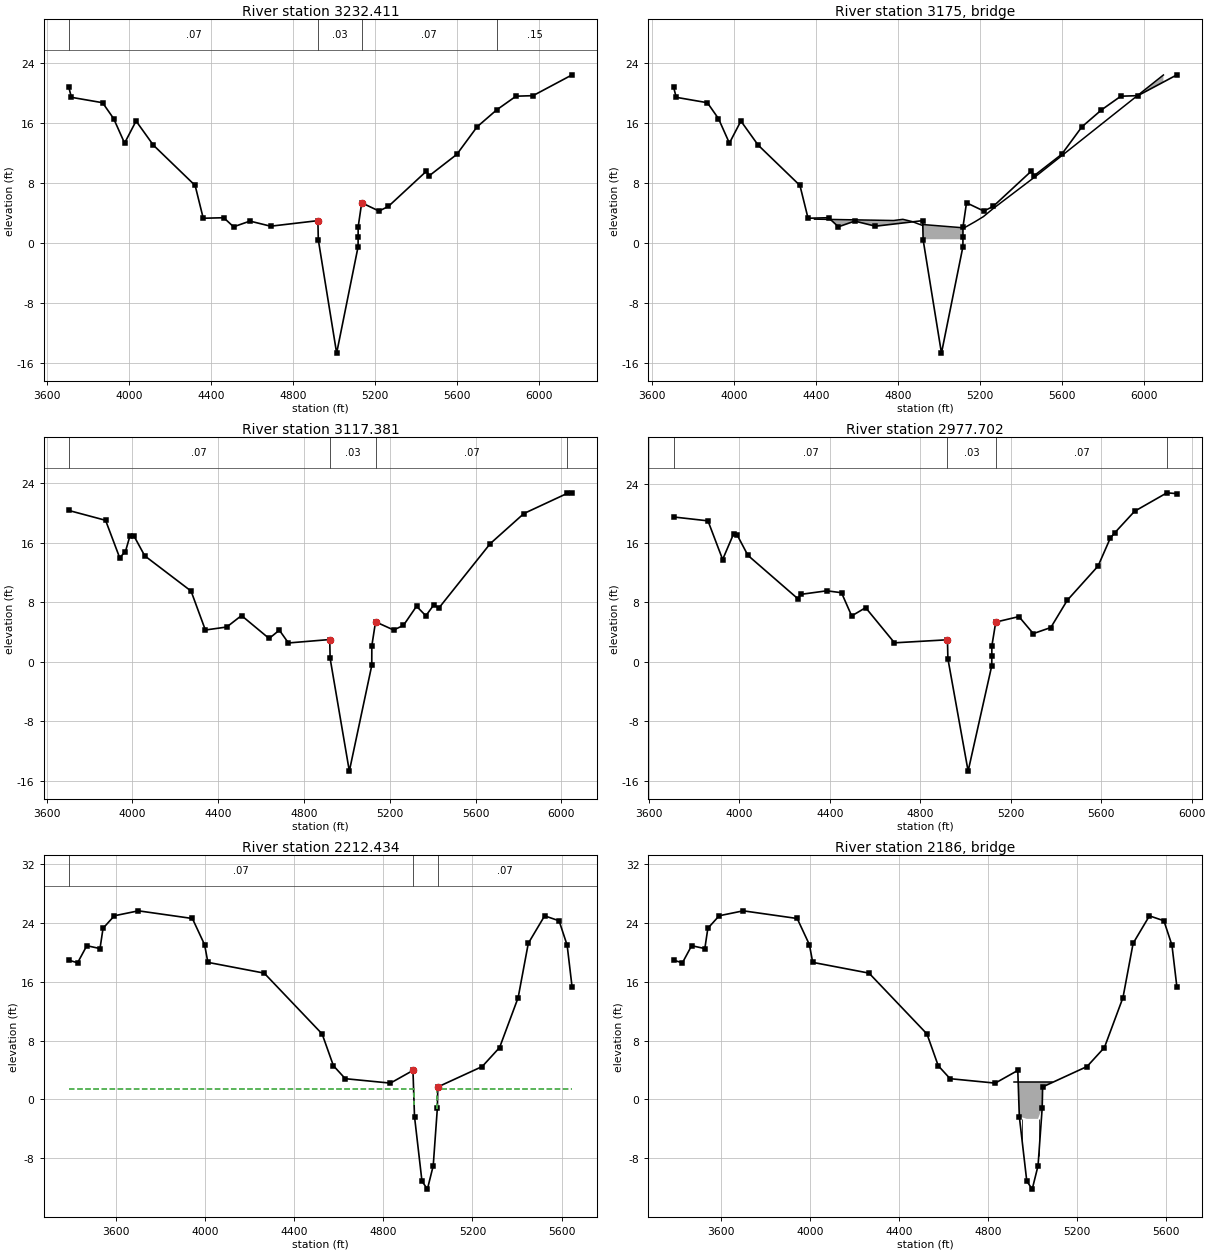
Type RM Length L Ch R = 1 ,3232.411,239.41,115.03,116.17
BEGIN DESCRIPTION:
Richey Road
END DESCRIPTION:
XS GIS Cut Line= 6
     3167426.803    13827520.673     3168120.155    13827619.734
     3168110.925    13828100.741     3168096.173    13828367.401
     3168090.497     13828522.32     3168072.731    13829373.763
#Sta/Elev= 30
 3704.88   20.76 3717.41   19.43 3869.41   18.71 3923.54   16.59 3976.81   13.32
 4032.84   16.27 4116.95   13.06 4321.03    7.67 4360.49     3.3  4460.6    3.37
 4508.47    2.16 4588.36    2.92 4689.25    2.24 4919.88    2.98 4921.82     .44
 5011.32  -14.69  5115.9     -.5 5116.13     .76 5116.23    2.13 5133.51    5.36
    5218    4.26 5263.68    4.88  5449.3    9.58 5463.15    8.97 5597.54   11.82
 5696.29   15.49 5791.81   17.75 5886.35   19.58 5969.29   19.65 6160.09   22.43
#Mann= 4 ,-1 , 0
 3704.88     .07       0 4919.88     .03       0 5133.51     .07       0
 5791.81     .15       0
#XS Ineff= 2 , 0
       0    4906     2.4    5129       0       2
Permanent Ineff=
       F       F
Bank Sta=4919.88,5133.51
Exp/Cntr=0.5,0.3

Type RM Length L Ch R = 3 ,3175    ,,,
BEGIN DESCRIPTION:
Bridge at Richey Road
END DESCRIPTION:
Bridge Culvert--1,0,-1,-1, 0
Deck Dist Width WeirC Skew NumUp NumDn MinLoCord MaxHiCord MaxSubmerge Is_Ogee
14,40,2.6,0, 13, 13, , , 0.95, 0, 0,0,,
    4392    4778    4823    4868    4919    4922    5121    5132    5177    5216
    5262    5487    6094
    3.18       3    3.16    2.86    2.34    2.46    2.02    2.17    2.87    3.52
    4.56    9.23   22.41
      .5      .5      .5      .5      .5      .5      .5      .5      .5      .5
      .5      .5      .5
    4392    4778    4823    4868    4919    4922    5121    5132    5177    5216
    5262    5487    6094
    3.18       3    3.16    2.86    2.34    2.46    2.02    2.17    2.87    3.52
    4.56    9.23   22.41
      .5      .5      .5      .5      .5      .5      .5      .5      .5      .5
      .5      .5      .5
BR Coef=-1 , 1 , 0 ,, 0 ,,,0.8,-1,2,0,
WSPro=,,,, 1 ,,,, 0 ,,,, 0 ,,,,-1 ,-1 ,-1 , 0 , 0 , 0 , 0 , 0
BC Design=,, 0 ,, 0 ,,,,,,
BC HTab HWMax=22.44

Type RM Length L Ch R = 1 ,3117.381,151.63,139.68,139.71
BEGIN DESCRIPTION:
Richey Road
END DESCRIPTION:
XS GIS Cut Line= 6
     3167424.444    13827572.563     3168054.303     13827662.24
     3168045.958    13828098.355     3168031.238    13828364.416
     3168025.522    13828520.452     3168007.745    13829372.407
#Sta/Elev= 30
  3703.2   20.31 3874.54   18.99 3940.22   13.97 3967.22    14.8 3987.48   16.82
  4006.3   16.92  4057.2   14.22 4273.14    9.49 4339.86    4.26 4439.64    4.66
 4508.46     6.2 4637.28    3.12 4684.94    4.24 4727.18    2.52 4919.88    2.98
 4921.82     .44 5011.32  -14.69  5115.9     -.5 5116.23    2.13 5133.51    5.36
    5218    4.26 5263.68    4.88 5324.74    7.45 5368.18    6.17 5405.72    7.65
 5428.88    7.21 5668.22   15.85 5825.44    19.9 6026.88    22.6 6050.36   22.68
#Mann= 4 ,-1 , 0
  3703.2     .07       0 4919.88     .03       0 5133.51     .07       0
 6026.88     .15       0
#XS Ineff= 2 , 0
       0    4906     2.4    5129       0       2
Permanent Ineff=
       F       F
Bank Sta=4919.88,5133.51
Exp/Cntr=0.5,0.3

Type RM Length L Ch R = 1 ,2977.702,868.48,765.27,696.14
BEGIN DESCRIPTION:
Richey Road
END DESCRIPTION:
XS GIS Cut Line= 6
     3167438.596    13827610.301     3167973.823    13827685.774
     3167965.998    13828095.418     3167951.319    13828360.742
     3167945.553    13828518.153     3167927.763    13829370.738
#Sta/Elev= 30
 3708.77    19.5 3860.59   18.98  3925.5   13.78  3973.6   17.21 3988.74   17.14
 4037.15   14.34 4257.85    8.51 4271.22    9.09 4386.44    9.57 4451.26    9.31
 4496.27    6.19 4557.99     7.3 4685.59    2.57 4919.88    2.98 4921.82     .44
 5011.32  -14.69  5115.9     -.5 5116.13     .76 5116.23    2.13 5133.51    5.36
    5236     6.1 5299.45    3.81 5377.13    4.63 5449.73    8.29 5586.13    12.9
 5640.38   16.67 5659.49   17.36 5747.68   20.27  5890.5   22.75 5935.03   22.64
#Mann= 4 ,-1 , 0
 3708.77     .07       0 4919.88     .03       0 5133.51     .07       0
  5890.5     .15       0
Bank Sta=4919.88,5133.51
Exp/Cntr=0.3,0.1

Type RM Length L Ch R = 1 ,2212.434,54.28,53.02,61.55
BEGIN DESCRIPTION:
Pipe crossing
END DESCRIPTION:
XS GIS Cut Line= 6
     3167410.828    13827293.385     3167386.929    13828170.103
     3167353.961    13828785.807     3167360.409    13829023.114
     3167362.009    13829420.128     3167350.842    13829551.033
#Sta/Elev= 30
  3387.9   18.89 3427.23   18.54 3468.64   20.86 3527.86   20.47 3541.46   23.22
 3592.29   24.92 3700.31   25.59 3942.53   24.55 3997.44   20.99 4012.12    18.6
 4264.94   17.14 4524.98    8.89 4575.64    4.58 4628.91    2.82 4831.58    2.22
 4932.78    3.94 4939.67   -2.31 4973.18  -11.08 4997.62  -12.16  5023.7   -8.99
 5042.35   -1.14 5044.23     1.7 5243.64    4.47 5321.71    7.05 5404.98   13.82
 5450.49   21.18  5523.8   24.91 5588.68   24.24 5624.87   20.93 5647.32   15.19
#Mann= 3 ,-1 , 0
  3387.9     .07       0 4932.78     .03       0 5044.23     .07       0
#XS Ineff= 2 , 0
       0    4938    1.37    5042       0    1.37
Permanent Ineff=
       F       F
Bank Sta=4932.78,5044.23
Exp/Cntr=0.3,0.1

Type RM Length L Ch R = 3 ,2186    ,,,
BEGIN DESCRIPTION:
Pipe crossing
END DESCRIPTION:
Bridge Culvert--1,0,-1,-1, 0
Deck Dist Width WeirC Skew NumUp NumDn MinLoCord MaxHiCord MaxSubmerge Is_Ogee
10,20,2.6,0, 4, 4, , , 0.95, 0, 0,0,,
    4915    4915    5085    5085
    2.37    2.37    2.37    2.37
       0   -2.63   -2.63       0
    4915    4915    5085    5085
    2.37    2.37    2.37    2.37
       0   -2.63   -2.63       0
Pier Skew, UpSta & Num, DnSta & Num=  ,4953, 4 ,4953, 4 , 3 , 3 , 0 ,,
     1.2     1.2     1.5     1.5
     -15   -4.13   -4.13       0
     1.2     1.2     1.5     1.5
     -15   -4.13   -4.13       0
Pier Skew, UpSta & Num, DnSta & Num=  ,5027, 4 ,5027, 4 , 3 , 3 , 0 ,,
     1.2     1.2     1.5     1.5
     -15   -4.13   -4.13       0
     1.2     1.2     1.5     1.5
     -15   -4.13   -4.13       0
BR Coef=-1 , 1 , 0 ,, 0 ,,,0.8,-1,1.2,0,
WSPro=,,,, 1 ,,,, 0 ,,,, 0 ,,,,-1 ,-1 ,-1 , 0 , 0 , 0 , 0 , 0
BC Design=,, 0 ,, 0 ,,,,,,
BC HTab HWMax=25.59

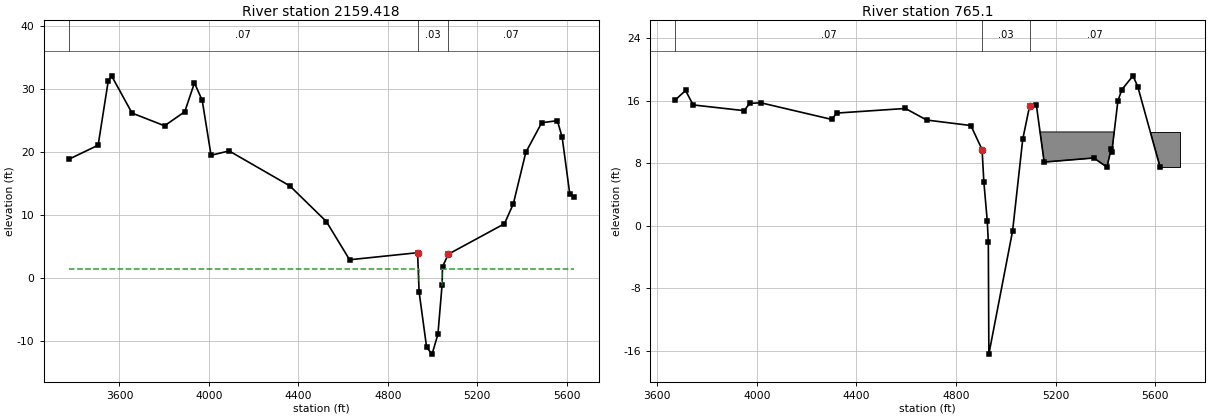
Type RM Length L Ch R = 1 ,2159.418,1768.54,1394.32,1006.17
BEGIN DESCRIPTION:
Pipe crossing
END DESCRIPTION:
XS GIS Cut Line= 6
     3167360.847    13827292.022     3167336.965    13828168.085
     3167303.925    13828785.148     3167310.412    13829023.894
        3167312.      13829418.1     3167301.023    13829546.783
#Sta/Elev= 30
 3374.17   18.78  3504.9   21.01 3549.68   31.14 3564.92   32.02 3656.29   26.11
 3801.69   24.09 3892.01   26.32 3935.33    30.9 3970.07   28.12 4009.62   19.41
 4090.28    20.1 4361.64   14.55 4524.98    8.89 4628.91    2.82 4932.78    3.94
 4939.67   -2.31 4973.18  -11.08 4997.62  -12.16  5023.7   -8.99 5042.35   -1.14
 5044.23     1.7    5070     3.7 5321.15    8.54 5360.94   11.72  5416.7   19.88
 5487.64   24.57 5557.75    24.9 5579.14   22.25 5613.23   13.23  5630.7   12.86
#Mann= 3 ,-1 , 0
 3374.17     .07       0 4932.78     .03       0    5070     .07       0
#XS Ineff= 2 , 0
       0    4938    1.37    5042       0    1.37
Permanent Ineff=
       F       F
Bank Sta=4932.78,5070
Exp/Cntr=0.3,0.1

Type RM Length L Ch R = 1 ,765.1   ,398.15,765.1,176.69
XS GIS Cut Line= 5
     3165425.764    13829747.788     3166552.152    13829967.851
     3166635.221    13829975.278     3166819.073    13830025.998
     3167322.938     13830168.96
#Sta/Elev= 30
 3673.13    16.1 3713.95    17.3 3744.52   15.45 3949.23   14.72 3971.27   15.64
  4015.5   15.73 4300.94    13.6 4320.94   14.41 4596.65      15 4682.35   13.52
 4859.64   12.82 4904.64    9.74 4911.72    5.62 4925.41     .62 4929.66   -2.08
 4931.83  -16.39 5027.23    -.63 5067.91   11.07 5095.36    15.3 5122.74    15.4
 5153.93    8.15 5353.07    8.67 5406.14    7.51 5422.75    9.83 5425.67    9.46
 5449.83   15.95 5465.77   17.41 5510.69   19.17    5530   17.76 5618.69    7.55
#Mann= 3 ,-1 , 0
 3673.13     .07       0 4904.64     .03       0 5095.36     .07       0
#Block Obstruct= 1 ,-1
    5100    5700      12
Bank Sta=4904.64,5095.36
Exp/Cntr=0.3,0.1

Chan Stop Cuts=-1
Use User Specified Reach Order=0
User Specified Reach Order=I100-00-00      ,I100-00-00_0008

--- I100-00-00.g03 (geometry) ---

Geom Title=I-100-00 June 2007
Program Version=3.13

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
River Reach=I100-00-00      ,I100-00-00_0008

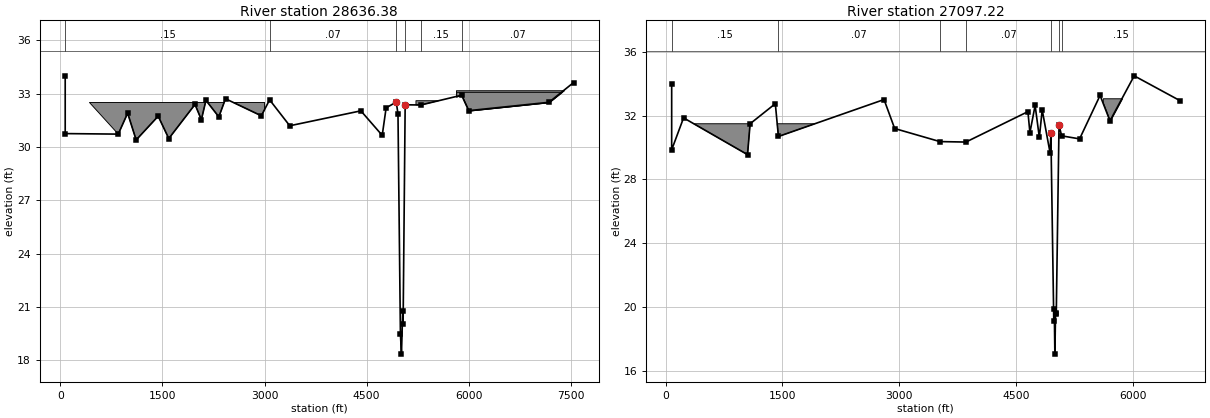
Type RM Length L Ch R = 1 ,28636.38,100.01,103.38,101.5
BEGIN DESCRIPTION:
Vista Road
END DESCRIPTION:
XS GIS Cut Line= 6
      3171723.23    13806476.748     3177626.991    13806776.045
     3177757.969    13806747.028     3177965.337    13806655.193
     3178187.517    13806622.607     3179156.222     13806664.08
#Sta/Elev= 30
   71.78      34   71.78   30.75  850.96   30.72  988.96    31.9 1113.87   30.39
 1437.71   31.73 1593.27   30.47 1978.49   32.39 2071.93   31.53 2139.21   32.62
 2328.58   31.69  2426.5   32.71 2952.86   31.75 3074.23   32.65 3370.17   31.19
 4414.94   32.03 4728.42   30.65 4785.95    32.2 4934.47   32.52 4960.01   31.86
 4995.73    19.5 5011.08   18.34 5029.51   20.78 5035.28   20.03 5065.53   32.37
  5296.9   32.36 5894.93   32.91 5999.64   32.04 7177.88   32.51 7538.78   33.62
#Mann= 6 ,-1 , 0
   71.78     .15       0 3074.23     .07       0 4934.47     .03       0
 5065.53     .07       0  5296.9     .15       0 5894.93     .07       0
#XS Ineff= 2 ,-1
                            1941    4954   30.75
Permanent Ineff=
       F       F
#Block Obstruct= 6 ,-1
   65.27    3000    32.5
 5224.12 7335.61    32.6 5811.77 7546.61   33.19  5815.7 7572.24    33.1
Bank Sta=4934.47,5065.53
Exp/Cntr=0.5,0.3

Type RM Length L Ch R = 1 ,27097.22,369.03,346.19,333.03
XS GIS Cut Line= 6
      3171513.09    13806777.759     3174220.406    13806864.265
     3174330.801    13806962.717     3175994.892    13808098.102
     3176284.253    13808284.116     3177385.203    13808998.471
#Sta/Elev= 30
   78.24      34   78.24   29.86  230.88   31.87 1052.11   29.56 1085.48    31.5
  1409.1   32.76 1449.02    30.7 2805.28   33.02 2941.75    31.2 3522.33   30.38
 3856.48   30.35 4652.75   32.26 4678.36   30.94 4745.28   32.65 4799.73   30.64
 4836.14   32.37  4937.4   29.67 4947.82   30.89 4984.93   19.09 4991.17   19.88
 4998.99   17.03 5007.51   19.54 5017.07   19.59 5052.18   31.41 5086.09   30.74
 5316.45   30.55  5579.6   33.28 5706.48   31.68 6017.75   34.51 6605.78   32.95
#Mann= 7 ,-1 , 0
   78.24     .15       0 1449.02     .07       0 3522.33     .15       0
 3856.48     .07       0 4947.82     .03       0 5052.18     .07       0
 5086.09     .15       0
#Block Obstruct= 2 ,-1
    65.2    2500    31.5 5614.33 5908.99    33.1
Bank Sta=4947.82,5052.18
Exp/Cntr=0.3,0.1